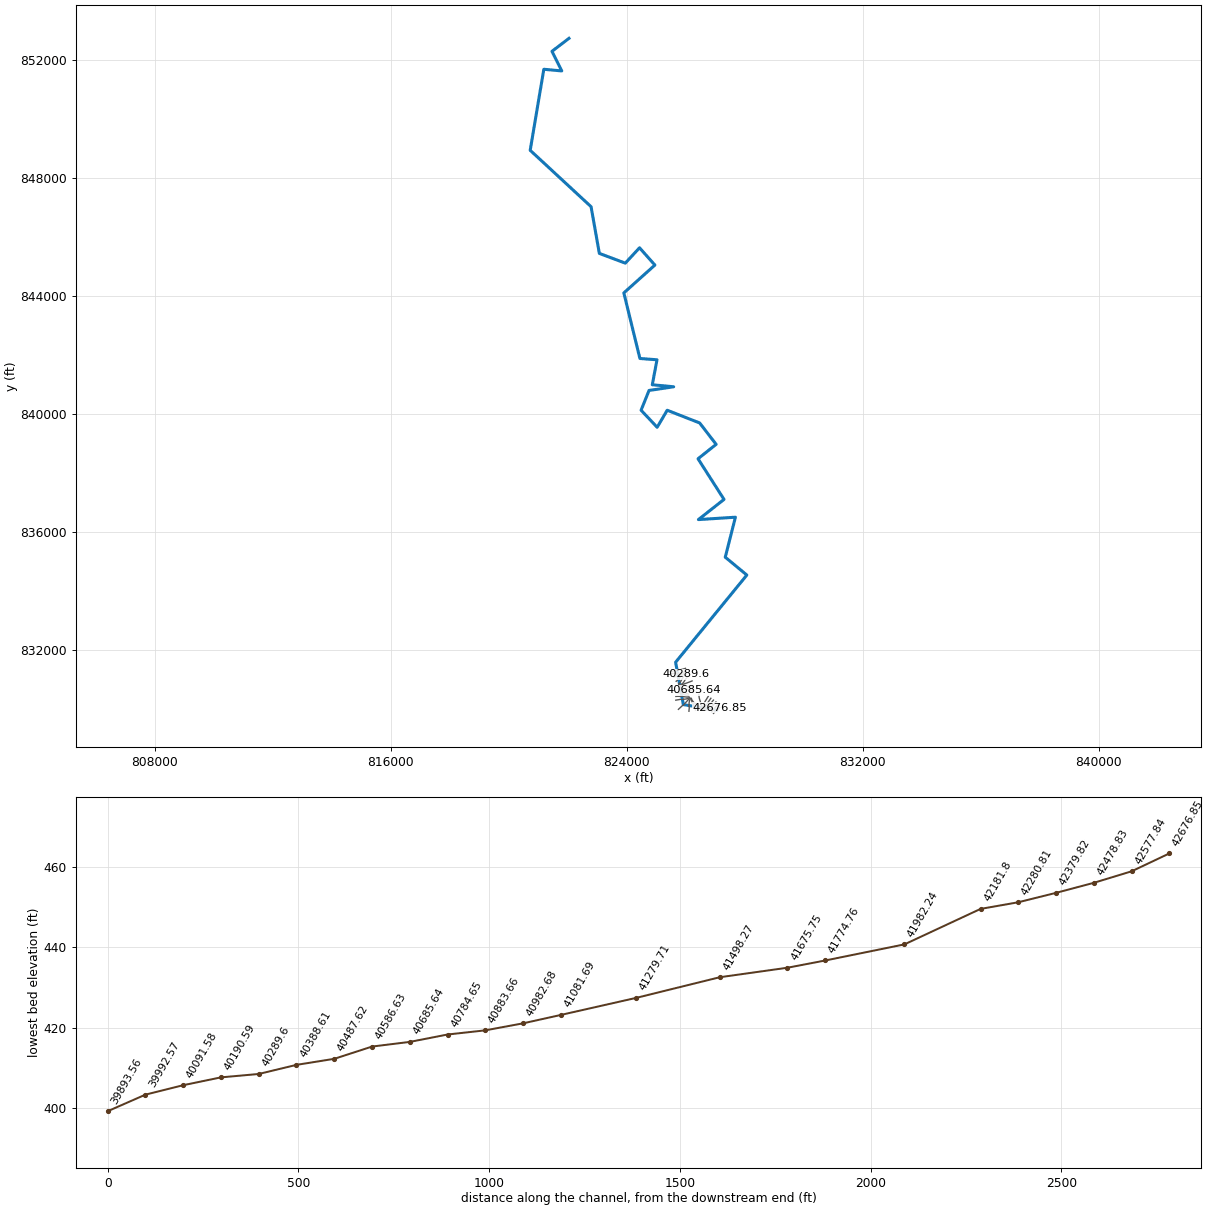
--- 18370_ras.prj (project) ---

Proj Title=18370
Current Plan=p01
Default Exp/Contr=0.3,0.1
English Units
Geom File=g01
Flow File=f01
Plan File=p01
Y Axis Title=Elevation
X Axis Title(PF)=Main Channel Distance
X Axis Title(XS)=Station
BEGIN DESCRIPTION:
RFD model 18370 exported to HEC-RAS
END DESCRIPTION:

--- 18370_ras.p01 (plan) ---

Plan Title=Plan 01
Program Version=4.10
Short Identifier=Plan 01
Geom File=g01
Flow File=f01
Subcritical Flow
Calc Critical at every XS
Secant Critical Depth

--- 18370_ras.f01 (steady flow) ---

Flow Title=Flow 01
Program Version=5.01
Number of Profiles= 6
Profile Names=10yr,25yr,50yr,100yr,100plus,500yr
River Rch & RM=18370,205,42676.85
  2943.3 4403.37 5703.45 6760.78 9870.7410610.57
River Rch & RM=18370,205,42577.84
 2953.26 4418.68 5723.65 6785.08 9906.2210644.53
River Rch & RM=18370,205,42478.83
 2955.05 4421.41 5727.25 6789.39 9912.5210650.52
River Rch & RM=18370,205,42379.82
 2960.57 4429.92 5738.48 6802.92 9932.2710669.47
River Rch & RM=18370,205,42280.81
 2974.85 4451.89 5767.48 6837.84 9983.2510718.29
River Rch & RM=18370,205, 42181.8
 2978.62  4457.7 5775.15 6847.08 9996.7410731.23
River Rch & RM=18370,205,41982.24
 2980.06 4459.93  5778.1 6850.6310001.9210736.21
River Rch & RM=18370,205,41774.76
 2985.62 4468.47 5789.36 6864.1910021.71 10755.1
River Rch & RM=18370,205,41675.75
 2990.68 4476.21 5799.53 6876.3810039.52   10772
River Rch & RM=18370,205,41498.27
 2995.62 4483.81 5809.57 6888.4710057.1610788.88
River Rch & RM=18370,205,41279.71
 3063.01 4587.85 5947.18 7054.4310299.4711021.23
River Rch & RM=18370,205,41081.69
 3068.66 4596.61 5958.78 7068.4510319.9411040.91
River Rch & RM=18370,205,40982.68
  3072.3 4602.26 5966.29 7077.53 10333.2 11053.7
River Rch & RM=18370,205,40883.66
 3087.76 4626.36 5998.36 7116.4210389.9811108.72
River Rch & RM=18370,205,40784.65
 3089.43 4628.96 6001.81  7120.610396.0811114.61
River Rch & RM=18370,205,40685.64
 3091.68 4632.44 6006.43 7126.1910404.2311122.46
River Rch & RM=18370,205,40586.63
 3092.51 4633.74 6008.15 7128.2810407.29 11125.4
River Rch & RM=18370,205,40388.61
    3107 4656.14  6037.8 7164.0510459.5211175.39
River Rch & RM=18370,205, 40289.6
 3108.38 4658.28 6040.65 7167.5110464.5711180.28
River Rch & RM=18370,205,40190.59
 3110.57 4661.71 6045.21 7173.0510472.6511188.11
River Rch & RM=18370,205,40091.58
 3115.51 4669.41 6055.47  7185.510490.8311205.73
River Rch & RM=18370,205,39992.57
 3117.97 4673.26  6060.6 7191.7210499.9211214.53
River Rch & RM=18370,205,39893.56
 3124.13 4682.82 6073.28 7207.05 10522.311236.04
River Rch & RM=18370,205,39695.54
  3126.6 4686.67  6078.4 7213.2710531.3811244.83
River Rch & RM=18370,205,39596.53
 3201.34 4804.62 6236.53 7406.2510813.1311520.93
River Rch & RM=18370,205,39497.52
 3202.97 4807.16 6239.92 7410.3710819.1411526.74
River Rch & RM=18370,205,39398.51
 3205.09  4810.5 6244.39 7415.8110827.0911534.48
River Rch & RM=18370,205, 39299.5
 3210.24 4818.55 6255.11 7428.83 10846.111552.85
River Rch & RM=18370,205,39200.49
 3212.08 4821.45    6259 7433.5810853.0311559.61
River Rch & RM=18370,205,39101.48
 3213.14 4823.11 6261.23  7436.310856.9911563.48
River Rch & RM=18370,205,39002.47
 3215.51 4826.85 6266.23  7442.4 10865.911572.17
River Rch & RM=18370,205,38903.46
 3216.03 4827.68 6267.35 7443.7510867.88 11574.1
River Rch & RM=18370,205,38804.45
 3228.43 4846.95 6292.96 7474.7710913.1711617.54
River Rch & RM=18370,205,38705.44
 3285.04 4936.71 6413.61 7622.3811128.6811828.96
River Rch & RM=18370,205,38606.43
 3309.09 4974.61 6464.41 7684.3511219.1511916.93
River Rch & RM=18370,205,38405.53
 3313.34 4981.28 6473.32 7695.1811234.97 11932.2
River Rch & RM=18370,205,38284.47
 3316.29  4985.9 6479.47 7702.6611245.88 11942.7
River Rch & RM=18370,205,38185.22
 3331.85  5010.1 6511.65 7741.6411302.7911997.03
River Rch & RM=18370,205,38085.97
  3351.9 5041.83 6554.27 7793.7411378.8612071.22
River Rch & RM=18370,205,37887.48
 3354.59 5046.03 6559.86 7800.5311388.7812080.72
River Rch & RM=18370,205,37788.24
 3355.93 5048.13 6562.66 7803.9311393.7412085.47
River Rch & RM=18370,205,37688.99
  3358.6 5052.31 6568.23  7810.711403.6212094.97
River Rch & RM=18370,205,37589.75
 3381.68 5088.59 6616.78 7869.8511489.9812178.39
River Rch & RM=18370,205,37395.51
 3384.33 5092.75 6622.33 7876.5911499.8312187.86
River Rch & RM=18370,205,37247.19
 3387.71 5098.08 6629.47  7885.311512.5412200.16
River Rch & RM=18370,205,37154.66
 3388.25 5098.92 6630.58 7886.6511514.5112202.05
River Rch & RM=18370,205,37062.13
 3405.19 5125.34 6665.77 7929.3511576.8512261.59
River Rch & RM=18370,205, 36969.6
 3764.26 5674.21 7387.41 8794.9212840.5813425.29
River Rch & RM=18370,205,36877.07
 3766.28 5677.41  7391.7 8800.1512848.2213432.58
River Rch & RM=18370,205,36784.54
 3767.55 5679.41 7394.38 8803.42   1285313437.13
River Rch & RM=18370,205,36599.48
 3768.58 5681.02 7396.54 8806.0512856.8313440.78
River Rch & RM=18370,205,36414.42
 3780.45 5699.76 7421.68 8836.7512901.6513483.56
River Rch & RM=18370,205,36321.89
 3782.21 5702.55 7425.42 8841.3112908.3113489.92
River Rch & RM=18370,205,36136.83
 3784.73 5706.52 7430.75 8847.8312917.8313499.02
River Rch & RM=18370,205, 36044.3
    3787 5710.11 7435.57  8853.712926.41 13507.2
River Rch & RM=18370,205,35711.19
 3796.64 5725.19 7455.68 8878.1312962.0813540.82
River Rch & RM=18370,205, 35552.3
 3797.69 5726.82 7457.85 8880.7812965.9413544.45
River Rch & RM=18370,205,35356.82
  3799.5 5729.66 7461.64 8885.3912972.67 13550.8
River Rch & RM=18370,205,35259.07
 3802.81 5734.87 7468.62 8893.8912985.08 13562.6
River Rch & RM=18370,205,35161.33
 3803.33 5735.69 7469.71 8895.2112987.0113564.42
River Rch & RM=18370,205,35063.59
 4010.79 6056.01  7893.6 9406.5713733.5914252.77
River Rch & RM=18370,205,34965.85
 4012.82 6059.21 7897.87 9411.7613741.1714259.89
River Rch & RM=18370,205, 34868.1
 4016.36 6064.77 7905.31 9420.8313754.4214272.35
River Rch & RM=18370,205,34672.62
 4017.88 6067.15 7908.51 9424.7213760.0914277.68
River Rch & RM=18370,205,34477.13
  4019.9 6070.33 7912.76  9429.913767.66 14284.8
River Rch & RM=18370,205,34281.65
  4022.4 6074.27 7918.04 9436.3513777.0714293.69
River Rch & RM=18370,205,34086.16
 4025.58 6079.32 7924.83 9444.6613789.2114305.24
River Rch & RM=18370,205,33695.19
 4118.75 6227.63 8124.82 9689.9314147.2914646.71
River Rch & RM=18370,205,33597.45
 4121.14 6231.44 8129.96 9696.2414156.5114655.51
River Rch & RM=18370,205,33499.71
 4122.81  6234.1 8133.56 9700.6614162.9614661.67
River Rch & RM=18370,205,33401.97
 4123.76 6235.62 8135.61 9703.1814166.6514665.19
River Rch & RM=18370,205,33304.22
 4124.74 6237.17  8137.7 9705.7314170.3714668.71
River Rch & RM=18370,205, 33109.9
 4129.27  6244.4 8147.46 9717.7314187.8814685.43
River Rch & RM=18370,205,32956.22
 4130.46  6246.3 8150.03 9720.8814192.4914689.83
River Rch & RM=18370,205, 32811.4
 4149.44 6276.18 8190.04 9769.6714263.7114756.61
River Rch & RM=18370,205,32666.58
 4150.91  6278.5 8193.17 9773.4814269.2914761.88
River Rch & RM=18370,205,32376.93
 4156.04 6286.63 8204.09 9786.85 14288.814780.31
River Rch & RM=18370,205,32087.28
 4158.16 6290.03 8208.68  9792.514297.05 14788.2
River Rch & RM=18370,205,31942.45
 4160.75 6294.18  8214.3  9799.414307.1314797.85
River Rch & RM=18370,205,31797.63
 4162.87 6297.57 8218.89 9805.0514315.3814805.75
River Rch & RM=18370,205,31652.81
 4163.58  6298.7 8220.42 9806.9414318.1314808.37
River Rch & RM=18370,205,31507.98
 4164.99 6300.96 8223.48  9810.714323.6314813.64
River Rch & RM=18370,205, 31285.5
 4206.38 6367.23 8313.15    992114484.6614967.61
River Rch & RM=18370,205,31027.98
 4220.61 6390.04 8344.06 9959.0714540.2415020.83
River Rch & RM=18370,205,30807.22
 4224.81 6396.79 8353.19  9970.314556.6515036.52
River Rch & RM=18370,205,30582.26
 4226.93 6400.17 8357.76 9975.9314564.8615044.36
River Rch & RM=18370,205,30433.68
 4229.27 6403.92 8362.85 9982.1814573.9915053.08
River Rch & RM=18370,205,30285.11
 4231.85 6408.06 8368.44 9989.0614584.0315062.66
River Rch & RM=18370,205,29999.04
 4233.97 6411.44 8373.01 9994.6914592.2415070.49
River Rch & RM=18370,205,29690.81
 4666.81 7081.26 9260.8511067.12   1615816489.29
River Rch & RM=18370,205,29393.66
 4668.88 7084.57 9265.3311072.6316166.0416496.86
River Rch & RM=18370,205,29245.08
 4671.41 7088.62  9270.811079.3616175.87 16506.1
River Rch & RM=18370,205,29096.51
 4676.22 7096.32 9281.23 11092.216194.6116523.74
River Rch & RM=18370,205,28947.94
  4676.9 7097.42 9282.7211094.0316197.2816526.26
River Rch & RM=18370,205,28696.53
 4680.31 7102.89 9290.1311103.1716210.6216538.85
River Rch & RM=18370,205,28419.94
 4809.15 7310.27 9571.7511450.6316717.9217018.02
River Rch & RM=18370,205,28121.91
 4812.54 7315.71 9579.1211459.7116731.1817030.47
River Rch & RM=18370,205,27823.89
 4815.68 7320.76 9585.9711468.1616743.5217042.09
River Rch & RM=18370,205,27525.86
  4825.7  7336.9 9607.9111495.2516783.0717079.41
River Rch & RM=18370,205, 27228.4
 4827.28 7339.44 9611.3511499.4916789.2517085.21
River Rch & RM=18370,205,26916.98
 4985.28 7590.52 9949.7311914.2517394.8117645.26
River Rch & RM=18370,205,26482.77
 4989.75 7597.69 9959.4611926.2517412.3217661.63
River Rch & RM=18370,205,26333.76
 5009.24 7629.17 10002.3 11979.217489.6417734.38
River Rch & RM=18370,205,26184.75
 5010.12 7630.5910004.2311981.5917493.1217737.65
River Rch & RM=18370,205,26035.74
 5013.43 7635.9210011.4811990.5417506.19 17749.9
River Rch & RM=18370,205,25737.71
 5024.02 7652.9910034.6612019.1617547.9817789.07
River Rch & RM=18370,205, 25588.7
 5025.57 7655.4710038.0412023.3417554.0717794.78
River Rch & RM=18370,205,25439.69
 5031.19 7664.5810050.4712038.7217576.5417815.99
River Rch & RM=18370,205,25245.93
 5031.61 7665.2810051.42 12039.917578.2617817.62
River Rch & RM=18370,205,24843.64
 5049.37 7694.0410090.6212088.4317649.1217884.42
River Rch & RM=18370,205, 24396.6
 5054.48 7702.3510101.9912102.5517669.7217903.96
River Rch & RM=18370,205,23800.55
 5076.17 7737.5510150.04 12162.117756.6717986.08
River Rch & RM=18370,205,23235.57
 5082.76 7748.2810164.7112180.3117783.2518011.25
River Rch & RM=18370,205,23055.49
 5084.46 7751.0510168.49   12185 17790.118017.74
River Rch & RM=18370,205,22906.47
 5085.09 7752.0910169.9112186.7617792.6818020.18
River Rch & RM=18370,205,22757.46
 5087.21 7755.5410174.6312192.6317801.2418028.29
River Rch & RM=18370,205,22608.45
 5253.96 8025.2410542.0612647.2518464.9918650.63
River Rch & RM=18370,205,22459.44
 5255.21 8027.2810544.8612650.7318470.0718655.43
River Rch & RM=18370,205,22310.42
 5256.47 8029.3310547.6712654.2218475.1618660.23
River Rch & RM=18370,205,22161.41
 5258.99 8033.4410553.2812661.1918485.3418669.84
River Rch & RM=18370,205, 22012.4
 5260.03 8035.1410555.6112664.0918489.5718673.84
River Rch & RM=18370,205,21863.39
 5260.44 8035.8110556.5412665.2518491.2618675.45
River Rch & RM=18370,205,21678.13
 5262.31 8038.8710560.7312670.4618498.8718682.65
River Rch & RM=18370,205,21565.36
 5262.52 8039.2110561.1912671.0418499.7118683.45
River Rch & RM=18370,205,21416.35
 5264.63 8042.6410565.8812676.8618508.2118691.45
River Rch & RM=18370,205,21267.34
 5266.52 8045.72 10570.112682.0918515.8618698.65
River Rch & RM=18370,205,20969.31
  5270.1 8051.5510578.0712691.98 18530.318712.25
River Rch & RM=18370,205,20522.28
 5294.11 8090.6110631.4812758.2818627.0818803.34
River Rch & RM=18370,205,20224.25
 5297.22  8095.710638.4512766.9518639.7418815.31
River Rch & RM=18370,205,19729.22
 5326.78 8144.0410704.7612849.4718760.2218929.29
River Rch & RM=18370,205,19330.18
 5329.26  8148.110710.3212856.3918770.3318938.85
River Rch & RM=18370,205,19181.16
 5330.92  8150.810714.0312861.0118777.0718945.21
River Rch & RM=18370,205,19032.15
 5332.57 8153.5110717.7412865.6318783.8118951.58
River Rch & RM=18370,205,18883.14
 5344.36 8172.7910744.17 12898.518831.8118996.92
River Rch & RM=18370,205,18585.11
 5353.02 8186.95 10763.612922.6918867.12 19030.3
River Rch & RM=18370,205,18287.09
 5355.71 8191.3410769.6212930.1718878.0619040.63
River Rch & RM=18370,205,17989.06
 5359.39 8197.3810777.9212940.5118893.1519054.92
River Rch & RM=18370,205,17691.04
 5363.07 8203.42 10786.212950.8418908.2319069.21
River Rch & RM=18370,205,17542.03
 5363.88 8204.7510788.0312953.1318911.5719072.39
River Rch & RM=18370,205,17393.01
 5372.64 8219.13 10807.812977.7718947.5519106.51
River Rch & RM=18370,205,   17244
 5498.54 8425.67 11091.613331.5419464.0519595.09
River Rch & RM=18370,205,17094.99
 5500.16 8428.3211095.2613336.09 19470.719601.38
River Rch & RM=18370,205,16945.98
 5501.36  8430.311097.98 13339.519475.6619606.09
River Rch & RM=18370,205,16796.96
 5513.65  8450.511125.7613374.1619526.2819653.96
River Rch & RM=18370,205,16647.95
 5521.36 8463.1411143.1313395.8119557.8819683.77
River Rch & RM=18370,205,16498.94
 5523.97 8467.4311149.0313403.1819568.6419693.96
River Rch & RM=18370,205,16349.93
 5525.78 8470.4111153.1313408.29 19576.119701.01
River Rch & RM=18370,205,16200.91
  5535.5 8486.4611175.2713435.9719616.51 19739.4
River Rch & RM=18370,205, 16051.9
 5538.05 8490.68 11181.113443.2819627.1819749.58
River Rch & RM=18370,205,15902.89
 5540.95  8495.511187.7813451.6719639.4319761.33
River Rch & RM=18370,205,15753.88
 5545.05 8502.31 11197.213463.4619656.6519777.76
River Rch & RM=18370,205,15617.19
 5566.99 8538.8611247.8713527.1219749.59 19866.9
River Rch & RM=18370,205,15306.84
 5576.54  8554.8   1127013554.9519790.2219905.94
River Rch & RM=18370,205,15008.81
 5580.16 8560.84 11278.413565.5119805.6519920.77
River Rch & RM=18370,205,14710.79
 5586.89 8572.0511293.9413585.0319834.1419948.07
River Rch & RM=18370,205,14561.78
 5591.25 8579.2511303.8613597.4319852.2519965.23
River Rch & RM=18370,205,14273.94
 5595.24 8585.81 11312.913608.7219868.7319980.82
River Rch & RM=18370,205,13965.73
 5928.57  9120.512038.0314502.4821173.6221171.28
River Rch & RM=18370,205, 13667.7
 5932.18 9126.4112046.1414512.5721188.3621184.99
River Rch & RM=18370,205,13395.04
 5935.71 9132.2112054.1514522.5821202.97 21198.7
River Rch & RM=18370,205,13220.66
 5937.57 9135.3312058.4814528.0421210.9421206.32
River Rch & RM=18370,205,13071.65
 5938.34 9136.6112060.2514530.2521214.1721209.36
River Rch & RM=18370,205,12936.91
 6129.23  9445.612481.6815052.2421976.2721907.63
River Rch & RM=18370,205,12773.63
 6134.03 9453.6412492.8615066.3321996.8421927.17
River Rch & RM=18370,205,12624.61
 6135.69 9456.4312496.73 15071.222003.9621933.93
River Rch & RM=18370,205,12365.88
 6137.17  9458.912500.1715075.5422010.2921939.95
River Rch & RM=18370,205,12177.58
 6138.66 9461.3812503.6215079.8822016.6221945.95
River Rch & RM=18370,205,12028.56
 6140.89 9465.11 12508.8 15086.422026.1421954.97
River Rch & RM=18370,205,11879.55
 6144.24  9470.712516.5715096.17 22040.421968.49
River Rch & RM=18370,205,11730.54
 6146.29 9474.1212521.3215102.1422049.1321976.75
River Rch & RM=18370,205,11581.53
 6147.58 9476.2912524.3315105.9422054.67   21982
River Rch & RM=18370,205,11432.51
 6150.18 9480.6312530.3615113.5322065.7521992.51
River Rch & RM=18370,205,11215.73
  6160.9 9498.5712555.3115144.9422111.6122036.03
River Rch & RM=18370,205,10966.02
 6194.03 9554.3312633.1415243.2622255.1622173.12
River Rch & RM=18370,205,10758.06
 6195.26 9556.4312636.0815246.99 22260.622178.36
River Rch & RM=18370,205,10499.53
 6203.75 9570.7312656.04 15272.222297.4222213.51
River Rch & RM=18370,205,10266.29
 6207.04 9576.2412663.72 15281.922311.5722226.96
River Rch & RM=18370,205,10033.04
 6210.51 9582.0712671.8315292.12 22326.522241.16
River Rch & RM=18370,205,9799.796
 6214.92 9589.5612682.3315305.4322345.9322259.84
River Rch & RM=18370,205,9566.551
 6219.33 9597.0412692.8215318.7322365.3422278.52
River Rch & RM=18370,205,9333.305
 6222.49  9602.412700.3515328.2822379.2922291.96
River Rch & RM=18370,205, 9100.06
 6253.92 9655.2112773.9615421.1822514.9222420.98
River Rch & RM=18370,205,8866.814
 6262.74 9670.1612794.9115447.7322553.6922458.22
River Rch & RM=18370,205,8633.569
 6270.18 9682.8612812.7715470.4322586.8322490.22
River Rch & RM=18370,205,8069.732
 6276.59 9693.7812828.1215489.9522615.3322517.74
River Rch & RM=18370,205,7945.807
 6277.63 9695.5512830.6115493.1222619.95 22522.2
River Rch & RM=18370,205,7602.332
 6307.75 9746.81 12902.615584.52 22753.422650.71
River Rch & RM=18370,205, 7227.75
 6475.5310027.0413292.0416074.7623469.1523324.95
River Rch & RM=18370,205,6784.575
 6478.52 10032.213299.3416084.0823482.7523338.15
River Rch & RM=18370,205,6341.401
 6511.9810089.5113380.1416187.0123633.0423483.17
River Rch & RM=18370,205,5779.389
  6528.910118.6613421.3616239.6723709.9223557.74
River Rch & RM=18370,205,5101.476
 7715.4412051.8616070.1319533.8628519.4427885.67
River Rch & RM=18370,205,4798.995
 7724.6212067.6816092.5419562.5328561.2927925.32
River Rch & RM=18370,205,4508.904
 7728.6912074.7216102.5319575.3328579.9827943.09
River Rch & RM=18370,205,4114.895
 7732.4412081.2116111.7519587.1328597.2127959.48
River Rch & RM=18370,205,3848.302
  7735.112085.8116118.27 19595.528609.43 27971.1
Boundary for River Rch & Prof#=18370,205,1
Up Type= 0
Dn Type= 2
Boundary for River Rch & Prof#=18370,205,2
Up Type= 0
Dn Type= 2
Boundary for River Rch & Prof#=18370,205,2
Up Type= 0
Dn Type= 2
Boundary for River Rch & Prof#=18370,205,2
Up Type= 0
Dn Type= 2
Boundary for River Rch & Prof#=18370,205,2
Up Type= 0
Dn Type= 2
Boundary for River Rch & Prof#=18370,205,2
Up Type= 0
Dn Type= 2

--- 18370_ras.g01 (geometry) ---

Geom Title=18370
Program Version=4.10

River Reach=18370,205
Reach XY= 30
827048.391789436829973.291807443825914.639274836830163.406671077
825653.545084924831598.345400035828067.515238702834553.455918208
 827336.34425053835159.117020994827680.485106647 836514.31181699
826426.146536291836433.436285704827294.007872671837117.744539157
826412.869781524838495.322634354 827027.20505777838984.003170103
826468.753146976839708.654277354825368.708436608840140.359392673
825027.102469534839563.163103476824482.526378781840141.265509322
824752.549132556840810.885694131825588.894776136840935.929788172
824863.347501397841004.148528725 825021.76414454841850.899028823
824442.914321125841895.138712004  823898.0022012844118.238289356
824950.988673121845061.478775263824429.892325461845647.388107195
823947.775871336845126.893759236823067.943243057845457.268483579
822787.316904753847039.797897786 820723.97824353848951.575337425
821185.688945442851699.110035881821793.894142091851642.356535509
 821461.89922291852306.605407149  822038.0644916852747.347638264

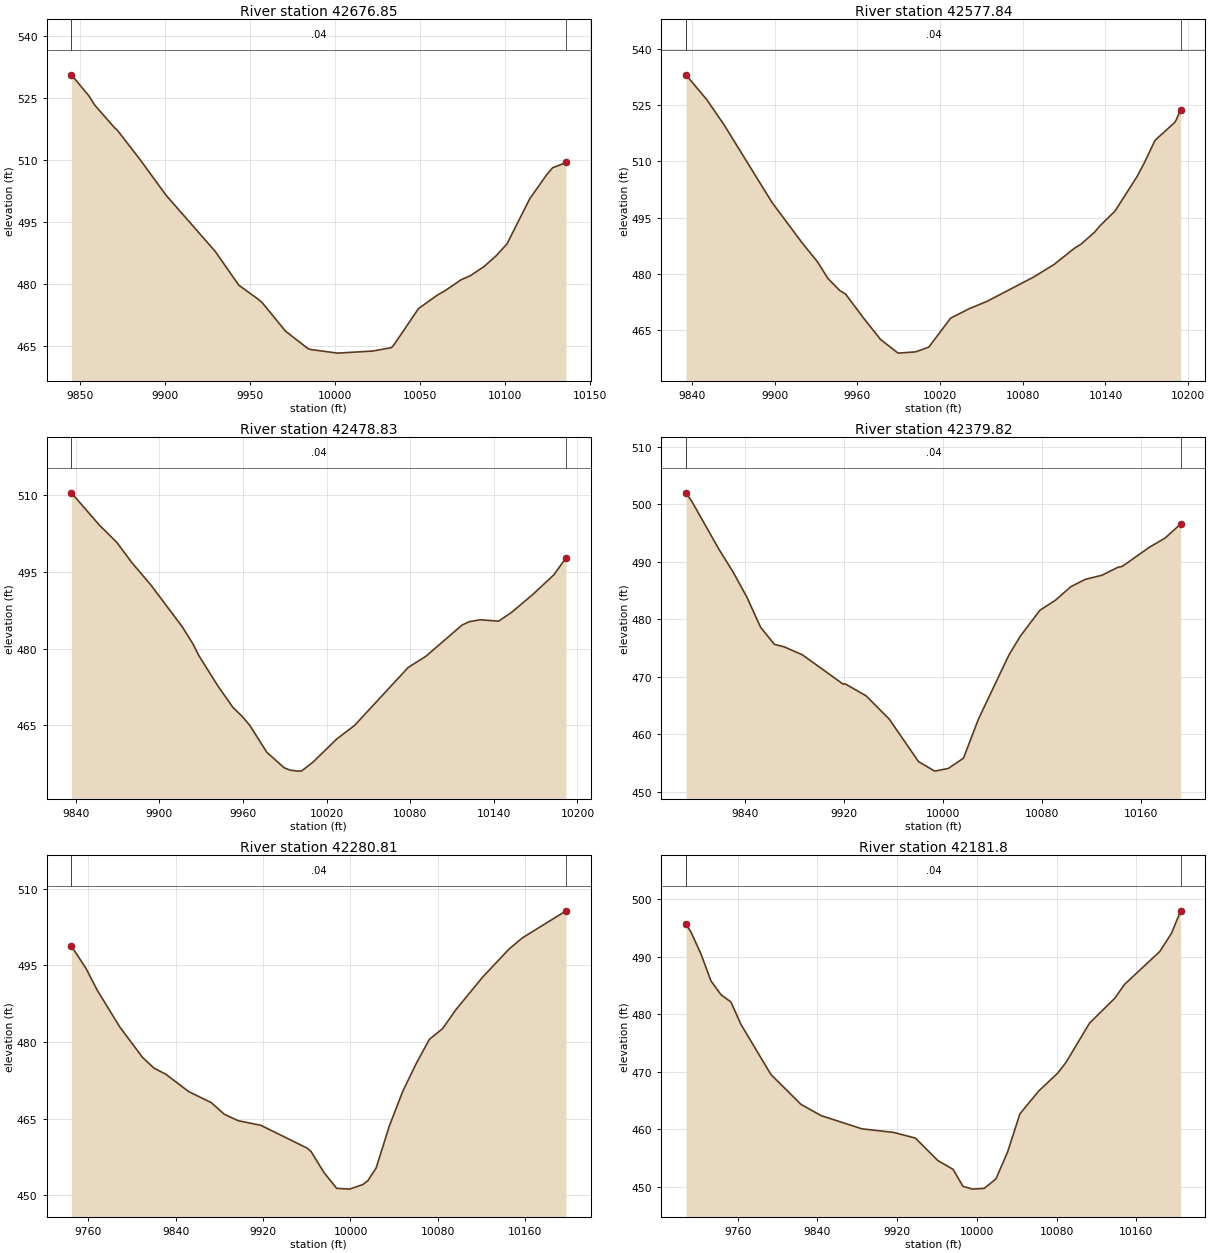
Type RM Length L Ch R = 1 ,42676.85,99.010200,99.010200,99.010200
XS GIS Cut Line= 6
826938.246026238829864.629492312826982.682344313829915.308101669
827020.892981923829952.556475726827048.619602326829974.687551412
827094.653069089830012.045556264827150.899400248830062.680862842
#Sta/Elev= 30
9844.757530.61139855.027 525.5539858.533523.27489870.189517.81479871.837517.2202
9885.141510.14019900.512 501.5069929.361487.97379943.326479.76919954.696 476.401
9957.292475.45779970.789468.67879983.614 464.5889985.394464.2393 10001.5463.3585
 10022.1 463.86210033.23464.688510034.97465.5626 10049.1474.126210060.28477.4049
 10064.7  478.4310074.21481.096510079.65482.077210087.66484.274310094.59486.8049
10101.12489.703510114.57500.638810124.49 506.44310128.03 508.13810135.97509.4274
#Mann= 3 , 0 , 0
9844.757    0.04       09844.757    0.04       010135.97    0.04       0
#XS Ineff= 2 , 0
       0                               0
Bank Sta=9844.757,10135.97
Exp/Cntr=0.3,0.1

Type RM Length L Ch R = 1 ,42577.84,99.010100,99.010100,99.010100
XS GIS Cut Line= 6
826877.748186421829912.610537684826928.241443864829980.334903503
826978.184333424830044.072962259827006.371474323830078.593453901
827089.222296842830168.629745209827108.200946469830187.360987153
#Sta/Elev= 30
 9835.54533.05069850.724526.38319863.248 519.6889898.032 499.0269920.026488.1903
9930.979483.24019938.661478.75249947.186475.57689951.368474.64429964.076468.4117
9976.783 462.5369989.491 458.912 10002.2459.249110011.78460.512910027.59468.2236
10040.93470.713710054.27472.754910087.85479.177210102.61482.512510117.38486.8266
10122.22487.929410132.15491.146610135.81492.763710146.92496.751810162.99505.9968
10167.92   509.410176.04515.628810190.09520.305810191.23520.950210194.59523.7838
#Mann= 3 , 0 , 0
 9835.54    0.04       0 9835.54    0.04       010194.59    0.04       0
#XS Ineff= 2 , 0
       0                               0
Bank Sta=9835.54,10194.59
Exp/Cntr=0.3,0.1

Type RM Length L Ch R = 1 ,42478.83,99.010200,99.010200,99.010200
XS GIS Cut Line= 6
826807.842068719829968.053320687826837.896501135830016.547631843
826898.274604779830102.566083428826929.462166996830142.964949481
826977.667126156830202.109472409827020.599296179830251.564151046
#Sta/Elev= 30
9836.841510.47699856.778504.20919869.412500.79259880.308496.80439893.893492.4557
 9916.29 484.3239924.072480.93119928.427478.59129941.717472.81829952.702468.5349
9959.362466.76729964.839465.00279977.124459.72629989.578456.70559993.506456.2752
    9999456.054210002.07456.091110010.02 457.76410027.34462.357510039.97464.9682
10078.46476.306810091.36478.542410117.17484.612210122.12485.257710130.17485.6594
10143.41  485.3810152.78487.113910168.03490.617110183.13494.461510191.83497.7817
#Mann= 3 , 0 , 0
9836.841    0.04       09836.841    0.04       010191.83    0.04       0
#XS Ineff= 2 , 0
       0                               0
Bank Sta=9836.841,10191.83
Exp/Cntr=0.3,0.1

Type RM Length L Ch R = 1 ,42379.82,99.010100,99.010100,99.010100
XS GIS Cut Line= 6
826717.697538701829980.391018464826751.558422611830052.207208518
826775.397948157830094.110654986826806.558278037830143.234612142
826844.794902378830198.700944979826934.228552277830314.865184851
#Sta/Elev= 30
9792.381501.94629797.355500.3506 9819.15492.07879830.307488.22559841.464 483.866
9852.622478.59229863.779475.6098 9871.82 475.1639886.538473.77149919.226468.7134
9921.083468.72189937.956466.65219956.625462.60889980.326455.21249993.411453.5619
10004.41454.031610016.63455.813610028.84462.659510053.44473.783310062.63 477.045
10078.41481.531610090.89 483.26410103.37485.627910115.12486.901910128.62487.6236
10141.37488.992610145.07489.170410166.87492.479610179.62 494.08910192.19496.5339
#Mann= 3 , 0 , 0
9792.381    0.04       09792.381    0.04       010192.19    0.04       0
#XS Ineff= 2 , 0
       0                               0
Bank Sta=9792.381,10192.19
Exp/Cntr=0.3,0.1

Type RM Length L Ch R = 1 ,42280.81,99.010200,99.010200,99.010200
XS GIS Cut Line= 6
826636.851636867829982.074707927826654.221899434830048.015279713
826669.552395933830091.703067625826687.511473991830132.241281239
826736.448317745830216.565718041826848.883072703830377.414803431
#Sta/Elev= 30
 9744.62498.75229757.921494.40669768.276490.11559788.986 482.9059809.696476.9821
 9820.22  474.889830.818473.71899852.014 470.2869872.567468.14479884.598465.8488
9897.255464.6032 9917.94463.70349960.358459.24239963.834458.60129975.598454.5109
9987.361451.37559999.127 451.22310011.26452.115510016.01452.901710023.44455.3505
10035.61463.601410047.79470.332610059.97 475.71510072.15480.500210084.33482.6172
 10096.5486.324610121.15492.732610145.22498.198410157.39500.366310197.26505.6395
#Mann= 3 , 0 , 0
 9744.62    0.04       0 9744.62    0.04       010197.26    0.04       0
#XS Ineff= 2 , 0
       0                               0
Bank Sta=9744.62,10197.26
Exp/Cntr=0.3,0.1

Type RM Length L Ch R = 1 , 42181.8,199.561900,199.561900,199.561900
XS GIS Cut Line= 6
826582.538930817829990.044507184826590.122303598830094.382551856
826597.056559852830140.154440412826611.751386044830191.055614255
 826639.84239199830248.472581679826759.677449144830442.793517765
#Sta/Elev= 30
9708.217495.63289713.185494.27319723.211490.45859733.238485.77159743.264483.3702
9753.291 482.0999763.317478.20369793.396469.49869823.568464.30069843.797462.3471
9884.713460.04949916.456459.42639938.302458.44249960.786454.54369976.125453.0114
9985.996450.06359995.509449.569110007.27449.694610019.02451.322610030.77455.9987
10043.16462.6565 10062.2466.656110081.25469.762410089.52471.632510113.02478.4233
10138.38482.765410148.27485.187110183.52490.885110195.27494.060610204.43 497.947
#Mann= 3 , 0 , 0
9708.217    0.04       09708.217    0.04       010204.43    0.04       0
#XS Ineff= 2 , 0
       0                               0
Bank Sta=9708.217,10204.43
Exp/Cntr=0.3,0.1

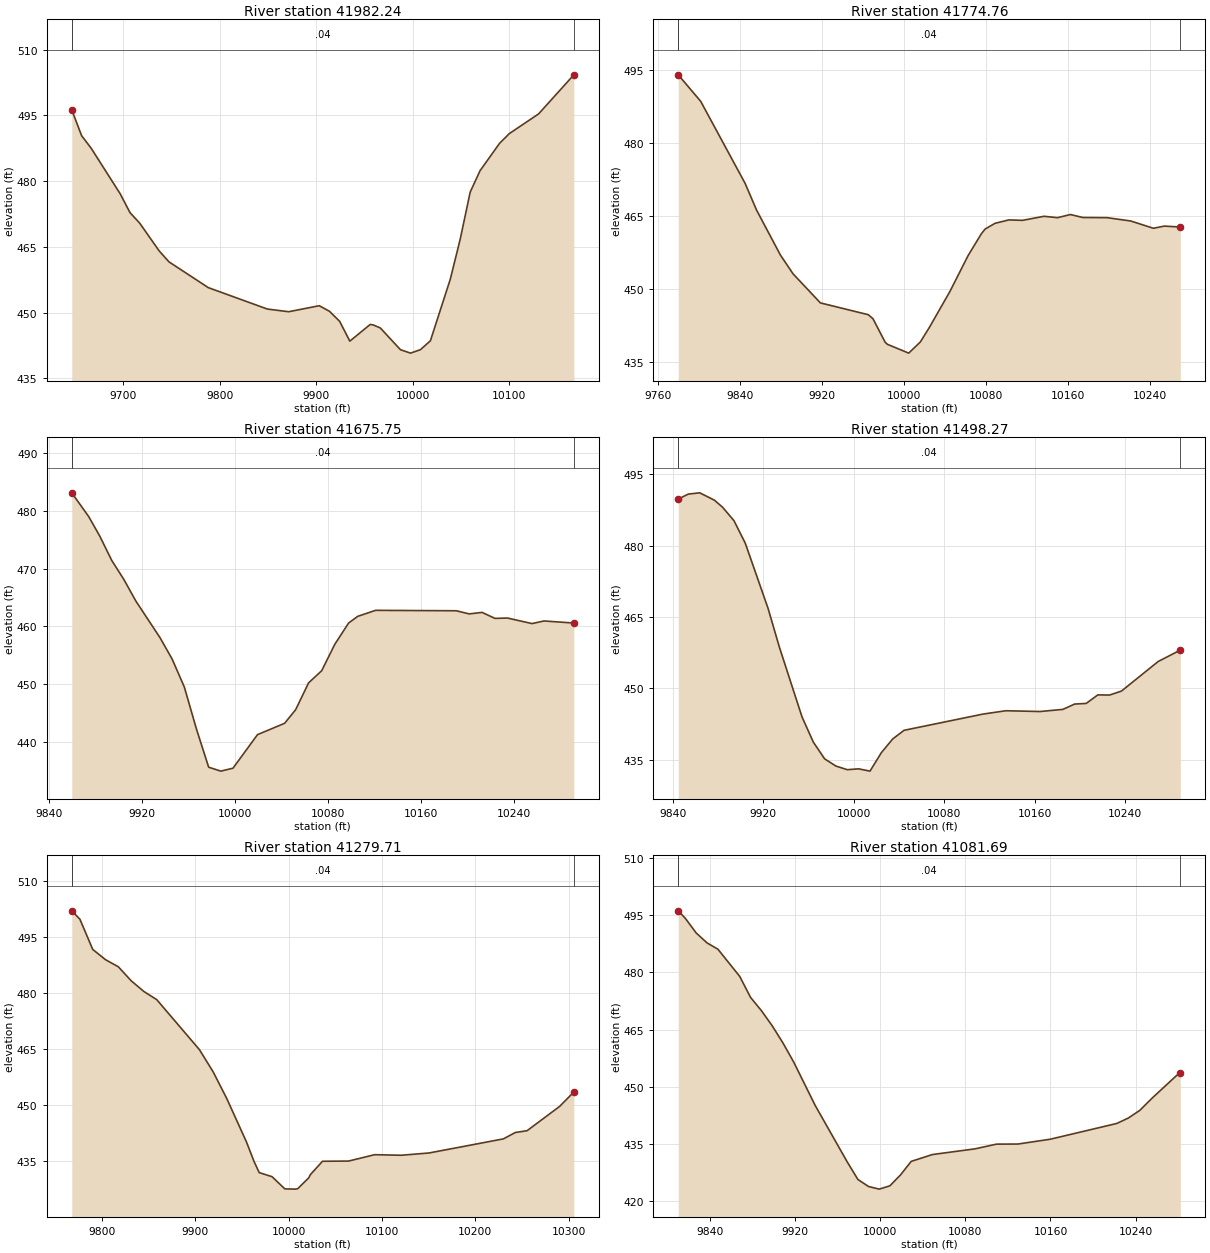
Type RM Length L Ch R = 1 ,41982.24,207.483100,207.483100,207.483100
XS GIS Cut Line= 6
826549.986661477829994.821198881826546.088287218830047.381113716
826530.157224714830139.995149688826468.823422959830332.118389286
826451.694338387 830399.45959105826440.110705119830501.528857381
#Sta/Elev= 30
9646.476496.28489656.665490.40449666.699487.49719696.801477.09239706.893472.8293
9717.003470.41439737.223464.07459747.333461.59369788.099455.71039849.345450.8226
9871.526450.20589903.257451.57669913.834450.3104 9924.41448.01619934.987443.4931
9956.141 447.3089959.487447.17269966.625446.49849987.508441.53799997.945440.7568
10008.26441.546310018.58443.577810039.22457.636910049.54 466.80110059.86477.5087
10070.08482.396610090.37488.654410100.52 490.874 10130.8495.3533 10167.4 504.279
#Mann= 3 , 0 , 0
9646.476    0.04       09646.476    0.04       0 10167.4    0.04       0
#XS Ineff= 2 , 0
       0                               0
Bank Sta=9646.476,10167.4
Exp/Cntr=0.3,0.1

Type RM Length L Ch R = 1 ,41774.76,99.010100,99.010100,99.010100
XS GIS Cut Line= 6
826487.907460849830003.930646798826472.956674527830051.336338014
826435.064526714830114.255140302   826264.410831830239.857728868
 826210.83405634830310.906262001826187.054005411830370.021275752
#Sta/Elev= 30
 9780.08494.04019801.938488.60049845.219471.73169856.468466.19769879.675456.9583
9892.055453.07069918.703447.09339965.409444.66539970.005443.8235  9981.8439.0204
9983.939438.5796 10004.8436.756910016.18439.062610025.11442.108410044.83  449.39
10062.68456.822810075.51461.288210079.29462.291210088.93463.472610102.35464.1752
10115.77464.087610136.66464.921210149.93464.637210162.45465.284310174.49464.6732
10198.26464.638310221.25463.956810243.39462.4562   10254462.902910269.61462.7229
#Mann= 3 , 0 , 0
 9780.08    0.04       0 9780.08    0.04       010269.61    0.04       0
#XS Ineff= 2 , 0
       0                               0
Bank Sta=9780.08,10269.61
Exp/Cntr=0.3,0.1

Type RM Length L Ch R = 1 ,41675.75,177.480400,177.480400,177.480400
XS GIS Cut Line= 6
826327.562208026829971.478675028  826309.8078745830042.329339792
826278.649721187830139.138353364826186.918554737830307.402198562
826172.753057798830352.492508219826170.615417266830370.232026883
#Sta/Elev= 30
9859.677483.09899874.246478.99159883.762475.61069894.113471.38699904.465 468.118
9914.817464.3695 9935.55458.05179946.013 454.3379956.477449.5076 9966.94442.2203
9977.404435.63999987.867434.95959998.331435.469210019.41441.2707 10042.7  443.23
10052.19445.576810063.35450.226510074.58452.320110085.88456.895710097.77460.5771
10105.63461.738710120.96462.772410190.38462.697810201.46 462.15510212.54462.4172
10223.61461.379710234.38461.4415 10255.5460.481810265.84 460.93410291.46460.5746
#Mann= 3 , 0 , 0
9859.677    0.04       09859.677    0.04       010291.46    0.04       0
#XS Ineff= 2 , 0
       0                               0
Bank Sta=9859.677,10291.46
Exp/Cntr=0.3,0.1

Type RM Length L Ch R = 1 ,41498.27,218.560200,218.560200,218.560200
XS GIS Cut Line= 6
826104.465528815829936.282190923826115.946645765830050.167268904
826109.336469716830141.737032835826110.885079777 830227.62157357
 826126.21983355830311.521342979826150.843226515830372.932450039
#Sta/Elev= 30
9844.901489.75759853.748490.80349863.896491.07219876.904489.52979884.125488.0426
9894.179485.22969904.233480.46729924.338466.79839934.343458.65789954.354444.0039
9964.364438.69719974.379435.18029984.393433.65869994.408432.900710004.44433.0805
10014.48432.598810024.51436.468510034.55 439.35410044.58441.172910114.63444.5938
10134.67445.287110164.93445.121610185.14445.573510195.42446.6883 10205.7446.8229
10215.98448.615510226.34448.584910236.85449.415110269.32455.625810288.92458.0274
#Mann= 3 , 0 , 0
9844.901    0.04       09844.901    0.04       010288.92    0.04       0
#XS Ineff= 2 , 0
       0                               0
Bank Sta=9844.901,10288.92
Exp/Cntr=0.3,0.1

Type RM Length L Ch R = 1 ,41279.71,198.020300,198.020300,198.020300
XS GIS Cut Line= 6
825748.625166978830001.523605528825918.552990633830160.926381397
825976.457953852830214.622952289826028.853336417830268.161815391
826075.722691949830322.048418172826124.361111535830384.467342456
#Sta/Elev= 30
9768.008502.07549776.746499.81779790.453491.73039804.161488.97689817.868487.0767
9831.575483.33179845.282480.4382 9858.99478.26379904.682464.85889919.303458.9384
9933.924451.76179954.941440.16359963.166434.87289968.648431.91149982.355430.8171
9996.062427.550510006.99427.480910009.79427.5829 10021.7430.513910023.43431.3714
 10036.4434.950210064.34435.004710092.18436.708510120.78436.561810150.46437.1714
10230.04440.947510242.72442.6526 10255.4443.1439 10290.2449.651810305.43453.5069
#Mann= 3 , 0 , 0
9768.008    0.04       09768.008    0.04       010305.43    0.04       0
#XS Ineff= 2 , 0
       0                               0
Bank Sta=9768.008,10305.43
Exp/Cntr=0.3,0.1

Type RM Length L Ch R = 1 ,41081.69,99.010200,99.010200,99.010200
XS GIS Cut Line= 6
825658.580674628830312.241323112825805.752829539830337.911709649
825925.754962011830342.887306815826015.374196149830353.453977308
 826089.36161783830379.105074609826117.175185641830397.180903645
#Sta/Elev= 30
9810.322496.14769816.952494.18969827.213490.34259837.442487.73269847.671486.0769
 9868.13 478.9519878.289473.45369888.431470.00519898.574466.03849908.716461.5264
9918.823456.51159938.961445.16779969.119430.34859979.135425.7538 9989.15423.9128
9999.165423.231610009.17424.102710019.18426.967710029.18430.5002 10049.2432.2952
10089.25433.788910109.34435.019710129.43435.045610159.74436.302910222.34440.4384
10233.19441.861510244.04443.889810255.38447.043410278.43452.986710281.99453.6768
#Mann= 3 , 0 , 0
9810.322    0.04       09810.322    0.04       010281.99    0.04       0
#XS Ineff= 2 , 0
       0                               0
Bank Sta=9810.322,10281.99
Exp/Cntr=0.3,0.1

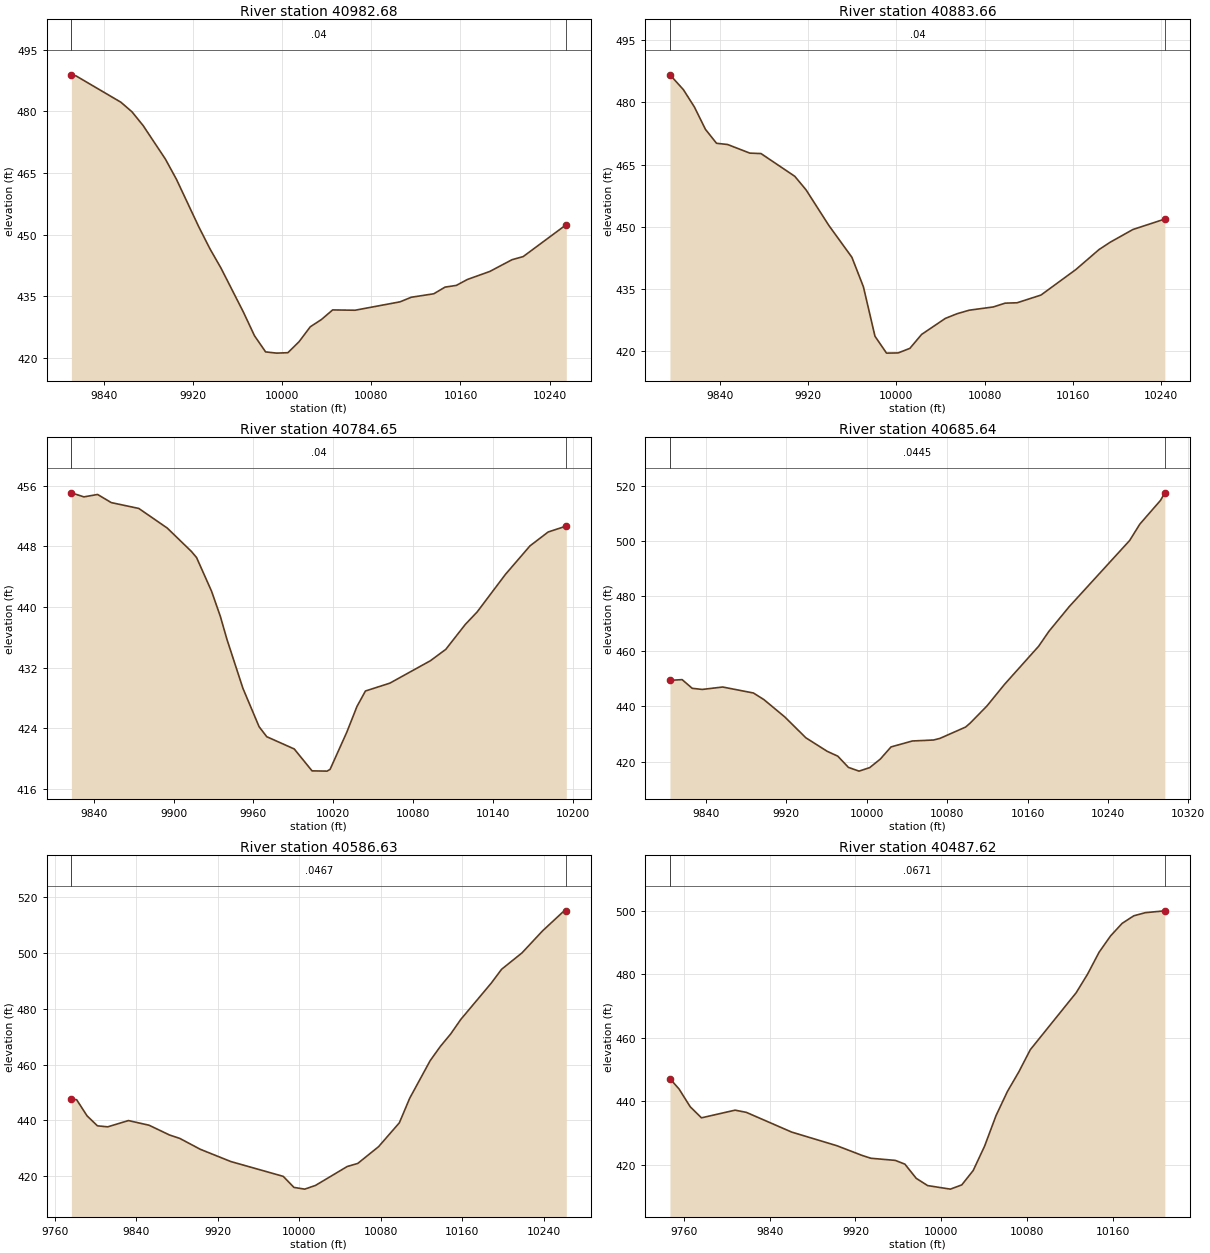
Type RM Length L Ch R = 1 ,40982.68,99.010100,99.010100,99.010100
XS GIS Cut Line= 6
825660.640737226830439.450188255825728.509928621830442.789678802
825849.070640404830439.017891359826035.834946314830416.398279303
826074.913579614830416.852953903826103.219598927830421.871557045
#Sta/Elev= 30
9810.395488.87069814.769488.57619854.838482.20889864.844479.8672 9874.85476.5213
9894.854 468.3659904.855 463.4049924.857451.88589934.858446.54689944.862441.8109
9964.887431.16119974.899425.38269984.912421.44639994.924421.147710004.94421.2538
10014.97423.930910025.01427.549910035.07429.327810045.14431.663210065.26431.5845
 10105.7433.630410115.81434.746710136.03435.591510146.14 437.21110156.24437.6265
10166.28 439.07910186.37441.026510206.37443.886810216.37444.644410255.08452.4106
#Mann= 3 , 0 , 0
9810.395    0.04       09810.395    0.04       010255.08    0.04       0
#XS Ineff= 2 , 0
       0                               0
Bank Sta=9810.395,10255.08
Exp/Cntr=0.3,0.1

Type RM Length L Ch R = 1 ,40883.66,99.010200,99.010200,99.010200
XS GIS Cut Line= 6
825662.851272149830575.950719426825725.660050113830571.694844953
825803.059109169830555.735828253825862.545593367830537.143779805
826038.087256471830469.665644484826093.631232759830460.382472106
#Sta/Elev= 30
9794.602486.68819806.752483.11749816.763478.91699826.806473.50879836.849470.1375
9846.892469.84459867.063467.75829877.196467.65299907.832462.16049918.111458.8645
9938.708450.29219959.656442.5777 9970.13435.42559980.605 423.4859991.079419.4035
10001.63419.453110012.28420.558410022.93423.928910044.42427.796110055.28428.9471
10066.13 429.78510087.85430.565410098.71431.485910109.57431.5789 10131.2433.4422
10162.83439.608910183.92444.452510194.23446.252410214.65449.297510243.58451.8204
#Mann= 3 , 0 , 0
9794.602    0.04       09794.602    0.04       010243.58    0.04       0
#XS Ineff= 2 , 0
       0                               0
Bank Sta=9794.602,10243.58
Exp/Cntr=0.3,0.1

Type RM Length L Ch R = 1 ,40784.65,99.010100,99.010100,99.010100
XS GIS Cut Line= 6
 825765.69048098830691.298924945825814.194945674 830680.34476202
825869.739270728830655.738478379825983.679620361830564.586337218
826025.452148005830540.568042075826088.094354278 830517.13547655
#Sta/Elev= 30
9823.141455.03669832.521454.50279842.814454.8211 9853.13453.74739873.794452.9802
9895.192450.39259913.383447.30739917.228446.50589928.453442.08849935.113438.7473
9940.076 435.7189952.059429.27849964.231424.21779969.972422.90349990.636421.2883
10004.01418.4055 10015.3 418.36910017.57418.601410030.11423.485810037.83426.9079
10044.15428.925510062.54429.9628   10093432.916110104.54434.410910119.24437.7015
10128.13439.343810149.38444.292110167.84448.048510181.49449.876310195.12450.6588
#Mann= 3 , 0 , 0
9823.141    0.04       09823.141    0.04       010195.12    0.04       0
#XS Ineff= 2 , 0
       0                               0
Bank Sta=9823.141,10195.12
Exp/Cntr=0.3,0.1

Type RM Length L Ch R = 1 ,40685.64,99.010200,99.010200,99.010200
XS GIS Cut Line= 6
825782.903726455830745.397696445825861.312098175830735.270622436
826119.059974435830650.329502727826189.761419689830641.189306749
826236.828500015830645.427759964826259.164840901830651.213570188
#Sta/Elev= 30
 9804.19449.49089816.297449.73979826.341446.58959836.386446.1849 9856.62447.0621
9887.236 444.8919897.662442.50039918.514436.18019939.452428.62949960.623 423.731
9971.208421.96179981.794417.89079992.379416.531810002.98417.811510013.59420.9302
10024.19425.3178 10045.4427.471110066.61427.830610072.92428.424310098.42432.5298
10102.96433.968410119.56440.151510137.23448.063110171.11461.876210181.29 467.261
10201.44476.204110261.65500.245910271.75506.171210292.37514.805510296.67517.5444
#Mann= 3 , 0 , 0
 9804.19  0.0445       0 9804.19  0.0445       010296.67  0.0445       0
#XS Ineff= 2 , 0
       0                               0
Bank Sta=9804.19,10296.67
Exp/Cntr=0.3,0.1

Type RM Length L Ch R = 1 ,40586.63,99.010100,99.010100,99.010100
XS GIS Cut Line= 6
825779.951719532830795.144818093825905.794798177830813.254868955
825970.034364542830804.081914251826098.154625148830768.869716713
 826175.19810785830762.391068865826258.111396514830770.252786832
#Sta/Elev= 30
9776.188447.67439781.346447.39899791.563441.62629801.745438.04879811.894437.6904
9832.191439.93429852.489438.26599872.623434.7588 9882.65433.54959902.704429.6627
9932.796425.25859984.303419.94469994.823415.990810005.37415.372910015.92416.6871
10047.18423.480710057.53424.580310078.02430.6025 10098.4439.1522 10108.5447.9008
10128.64461.4002 10138.7466.520910148.77470.949310158.77476.184910188.79489.2347
 10198.8494.132510218.84499.999910239.03  507.8810259.23514.723510262.38515.0759
#Mann= 3 , 0 , 0
9776.188  0.0467       09776.188  0.0467       010262.38  0.0467       0
#XS Ineff= 2 , 0
       0                               0
Bank Sta=9776.188,10262.38
Exp/Cntr=0.3,0.1

Type RM Length L Ch R = 1 ,40487.62,99.010200,99.010200,99.010200
XS GIS Cut Line= 6
825776.883660342830808.644278546 825843.74852064830829.307926182
825994.435841618 830881.17027105826080.687507832830912.564691706
 826165.53964727830945.070939212826211.796225055830964.276562366
#Sta/Elev= 30
9746.775447.09859755.235443.87589765.708438.25889776.181434.7827  9807.6437.1961
9818.086436.50199860.389430.29629902.692425.99229926.437 422.9159934.419422.0483
9957.165421.38069966.146420.20019976.725415.72939987.362 413.44610008.62412.3281
10019.26413.661510029.91418.185410040.56425.865910051.21435.457510061.86443.0712
10072.53449.256910083.24456.236910126.08474.178610136.78480.064210147.49486.9417
 10158.2 492.07110169.02496.026110179.85498.398510190.68499.390210208.87499.9682
#Mann= 3 , 0 , 0
9746.775  0.0671       09746.775  0.0671       010208.87  0.0671       0
#XS Ineff= 2 , 0
       0                               0
Bank Sta=9746.775,10208.87
Exp/Cntr=0.3,0.1

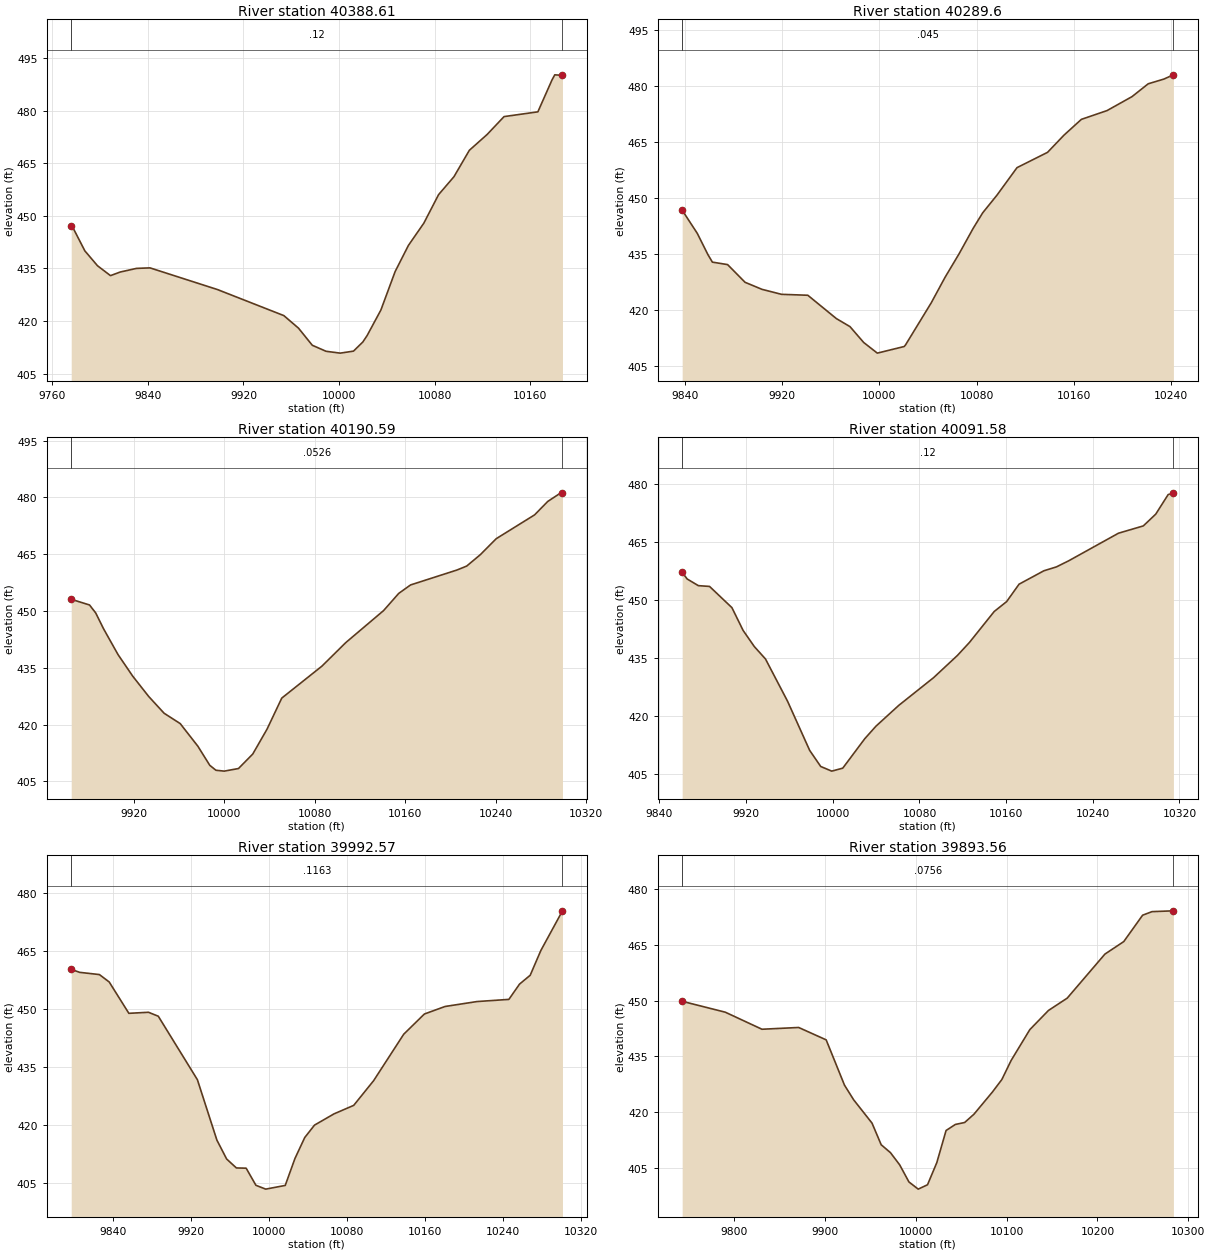
Type RM Length L Ch R = 1 ,40388.61,99.010100,99.010100,99.010100
XS GIS Cut Line= 6
825774.239347173830820.279256504825861.640213889830859.842770415
  825904.9563692830894.125108426825926.470614981830921.609173606
825986.035731168831020.839069786826059.841926364831100.909685331
#Sta/Elev= 30
9775.788447.08699776.594447.01839787.185439.99749797.785435.74899808.654432.9267
9816.805433.95539830.407434.99259841.733435.13969898.259 428.9549953.775421.5308
9966.077417.94459977.602413.07029989.128411.3529   10001410.8277 10012.1411.3979
 10019.9413.996710023.57415.880910035.04423.128710046.93434.066610058.05441.5303
10070.96447.877410083.33456.026210096.21461.140710109.09468.669310123.94473.1715
10138.16478.284210166.45479.636110178.26488.7144 10180.6490.194310187.05490.0518
#Mann= 3 , 0 , 0
9775.788    0.12       09775.788    0.12       010187.05    0.12       0
#XS Ineff= 2 , 0
       0                               0
Bank Sta=9775.788,10187.05
Exp/Cntr=0.3,0.1

Type RM Length L Ch R = 1 , 40289.6,99.010200,99.010200,99.010200
XS GIS Cut Line= 6
825755.012586545830872.466591374825782.416546257830892.673047422
 825819.84345995830933.353920389825877.322226112831041.682031032
  825927.6277042831117.116253496826001.258579209831185.733490091
#Sta/Elev= 30
9837.819446.79879850.228440.61029858.938434.95199862.652432.90579875.182432.2423
9889.535427.50659903.477425.62279919.518424.29069941.109 424.0449964.567417.8081
9975.795415.64999987.024411.41999998.252408.563310020.43410.340710021.56 410.819
10042.62422.037710053.88428.807910065.48435.132310077.08441.956510084.93446.1124
10096.53450.778510113.12458.1836 10138.2462.266310151.75  466.8810166.02471.0919
10187.15473.447310207.66477.176110220.96480.605810233.82481.867310241.68483.0066
#Mann= 3 , 0 , 0
9837.819   0.045       09837.819   0.045       010241.68   0.045       0
#XS Ineff= 2 , 0
       0                               0
Bank Sta=9837.819,10241.68
Exp/Cntr=0.3,0.1

Type RM Length L Ch R = 1 ,40190.59,99.010100,99.010100,99.010100
XS GIS Cut Line= 6
825671.645735439830952.812773911825712.682461033830983.289531918
825748.177636705831018.312807654825797.217660904831081.081477018
 825865.86859996831146.984373756825996.224606384831236.210604348
#Sta/Elev= 30
9864.888453.11019881.054451.6064 9886.51 449.5099893.371445.36699906.192438.5268
9919.298432.77339933.346427.43779946.953423.0113 9961.19420.27539976.792414.3017
9987.323409.24989992.746407.9536 10000.1407.720710012.68408.410410025.29412.2327
 10037.9418.801410050.91427.005210086.42435.453910107.48441.666910140.86450.1158
10154.26454.659810164.73456.898310205.78 460.84510214.31461.880210226.33464.8798
 10240.4469.110110274.32475.406810285.92478.943110297.53481.227810298.95481.1431
#Mann= 3 , 0 , 0
9864.888  0.0526       09864.888  0.0526       010298.95  0.0526       0
#XS Ineff= 2 , 0
       0                               0
Bank Sta=9864.888,10298.95
Exp/Cntr=0.3,0.1

Type RM Length L Ch R = 1 ,40091.58,99.010200,99.010200,99.010200
XS GIS Cut Line= 6
825580.532048089831093.761655436825655.363500801 831113.14065116
 825753.07251053831132.149174733825792.993351349831145.537543768
825836.788550395831165.666845753825999.211782058831256.907464349
#Sta/Elev= 30
9860.968457.14919865.583455.41639875.913453.69479886.243453.49289906.903448.0086
9917.233442.12239927.563437.95919937.892 434.7419958.277423.82019978.656411.1364
9988.845406.97749999.035405.7733 10009.2406.540710029.59414.169810039.85417.3823
10060.94422.767910093.13429.941710115.15435.688510126.15439.024910149.01447.0188
10160.48449.574910171.95454.073210194.89457.542710206.36458.530310217.83460.1238
10263.71467.244910286.64469.131610298.11472.170710309.58477.224910314.42477.6779
#Mann= 3 , 0 , 0
9860.968    0.12       09860.968    0.12       010314.42    0.12       0
#XS Ineff= 2 , 0
       0                               0
Bank Sta=9860.968,10314.42
Exp/Cntr=0.3,0.1

Type RM Length L Ch R = 1 ,39992.57,99.010100,99.010100,99.010100
XS GIS Cut Line= 6
825516.441669342831211.632961378825640.869313132831225.521750447
825759.776603394831221.592762835825814.517873044831226.479964378
825901.098333498831252.846417613826005.271565666 831298.89310788
#Sta/Elev= 30
9797.226460.16459805.895459.3911 9826.12458.81619836.192456.90349856.337448.8124
9876.482449.08169886.528448.0613 9926.62431.6788 9946.62416.0835 9956.62411.2032
9966.622408.89449976.642408.83559986.661404.4161 9996.68403.427910016.71404.3812
10026.72411.360910036.73416.750210046.74419.952410066.76422.857510086.93425.0474
10107.33431.411210138.25443.420610159.42448.634810180.67450.580410213.28 451.848
10246.08452.409710257.02456.355210267.95458.638110278.88465.031910301.05475.2728
#Mann= 3 , 0 , 0
9797.226  0.1163       09797.226  0.1163       010301.05  0.1163       0
#XS Ineff= 2 , 0
       0                               0
Bank Sta=9797.226,10301.05
Exp/Cntr=0.3,0.1

Type RM Length L Ch R = 1 ,39893.56,198.020300,198.020300,198.020300
XS GIS Cut Line= 6
825457.968434867831283.176683572825671.756402101831313.828678544
825711.514997007831321.668741558825790.665003043831338.761673049
825863.594820187831355.921823201825987.689923009831390.448570413
#Sta/Elev= 30
9742.502 449.8089790.014446.87599830.423 442.2929870.832442.76769901.139439.4413
9921.344427.25879931.446423.3177 9951.65 417.0649961.782411.23319971.974409.1174
9982.167405.8234 9992.36401.228810002.56399.3082 10012.8400.480910023.03406.4306
10033.26415.077610043.49416.697910053.72417.221510063.95 419.44610084.43425.4562
 10094.7428.777410104.97433.926110125.52442.193310146.07447.346810166.73450.6606
10208.25 462.49710229.01465.862110249.77472.952610260.15 473.913 10283.7474.1297
#Mann= 3 , 0 , 0
9742.502  0.0756       09742.502  0.0756       0 10283.7  0.0756       0
#XS Ineff= 2 , 0
       0                               0
Bank Sta=9742.502,10283.7
Exp/Cntr=0.3,0.1