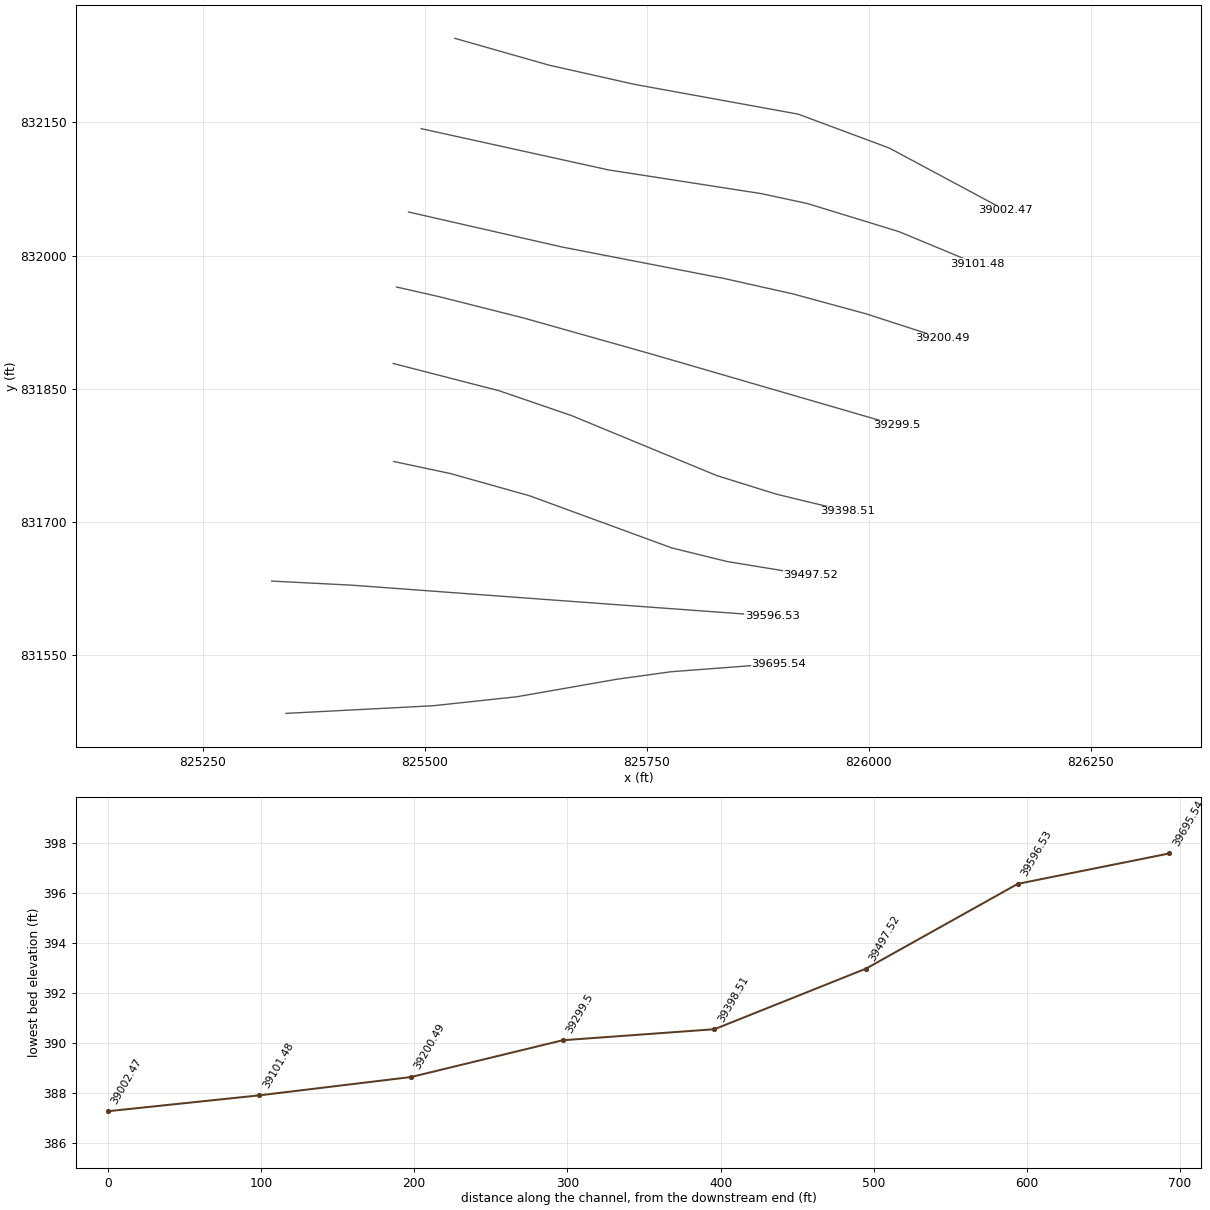
HEC-RAS study 18370_ras.prj: 18370

--- 18370_ras.g01 (geometry) --- (continued)

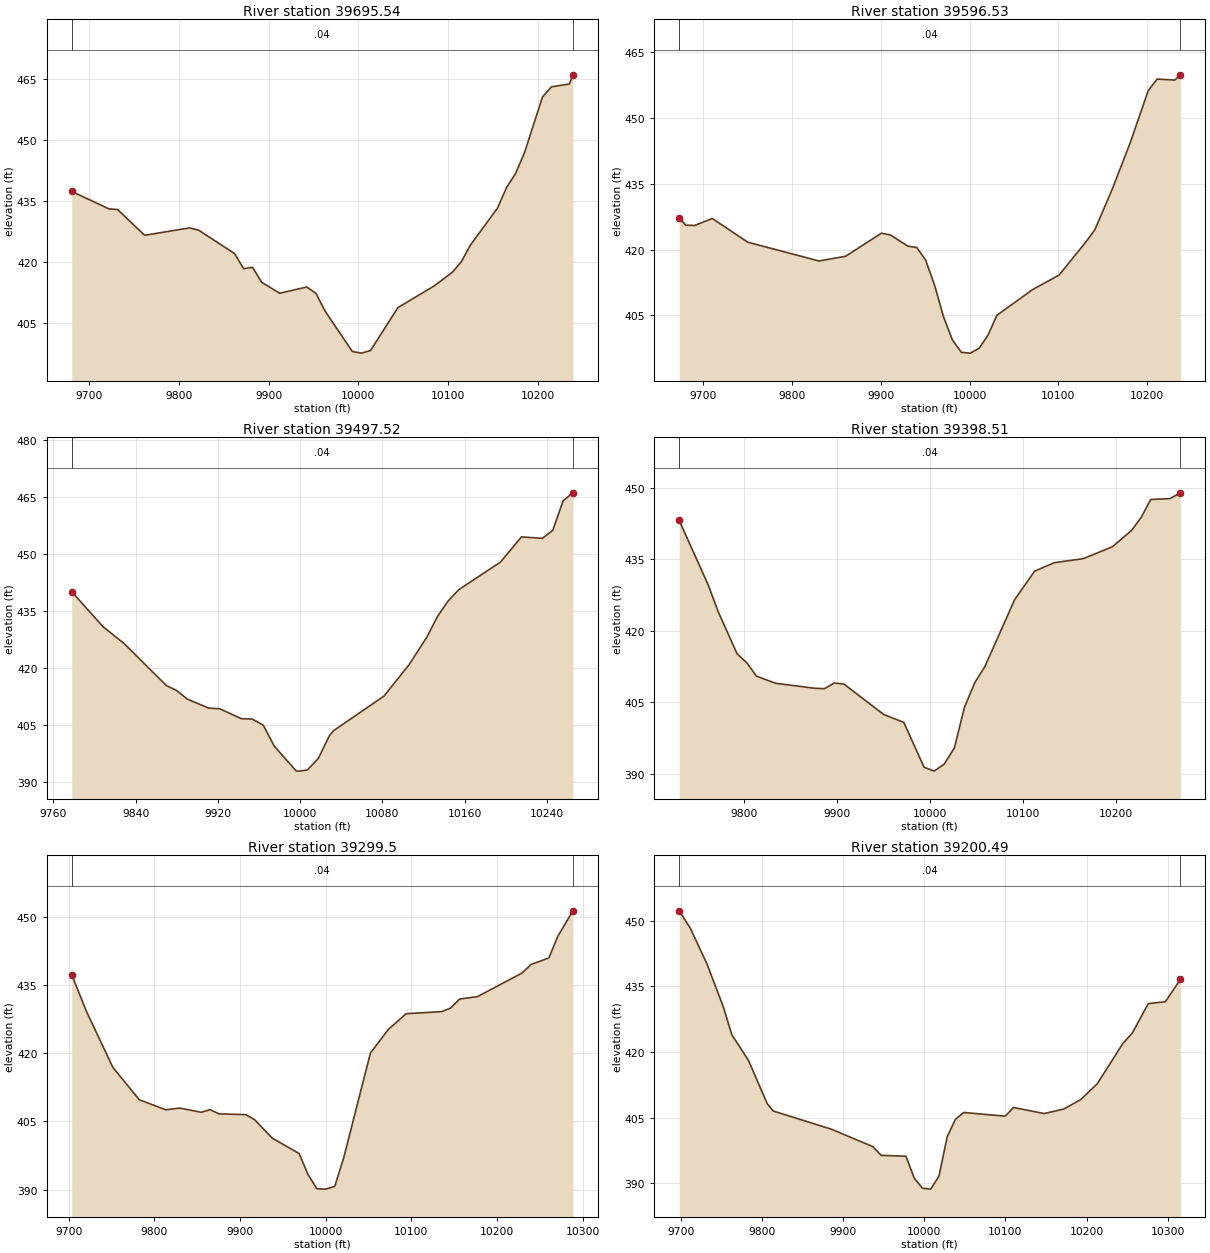
Type RM Length L Ch R = 1 ,39695.54,99.010200,99.010200,99.010200
XS GIS Cut Line= 6
825343.889990704831484.635728277825509.410681972831493.220078504
825603.792105926 831503.35413484825715.717845725831522.963836214
825776.809233155831531.462513499825898.800756155831540.734174553
#Sta/Elev= 30
9680.629 437.367 9721.77433.10459731.777432.89159761.818426.57859811.908428.3868
9821.926427.8593 9862.06422.06989872.117418.36639882.175 418.6849892.232 415.009
9912.347412.3195 9942.53413.8505 9952.67412.30069962.811407.96239993.232397.9903
10003.39397.587110013.55 398.22910044.04408.7839 10084.5414.1233 10104.7417.4744
10114.79420.091710124.84424.173110154.96433.2514   10165438.293310175.04 441.746
10185.08446.898810205.12460.601310215.14463.091510235.17  463.7910238.98466.0446
#Mann= 3 , 0 , 0
9680.629    0.04       09680.629    0.04       010238.98    0.04       0
#XS Ineff= 2 , 0
       0                               0
Bank Sta=9680.629,10238.98
Exp/Cntr=0.3,0.1

Type RM Length L Ch R = 1 ,39596.53,99.010100,99.010100,99.010100
XS GIS Cut Line= 5
825327.761536242831633.586748986 825417.77292384831628.994204622
825653.379702697831611.598584724825655.375729792831611.472585379
825891.163341876831594.196074468
#Sta/Elev= 30
9672.623427.29729679.871 425.5569689.884425.4786 9709.91 427.0719749.962421.6635
9830.162417.38139860.244418.45929900.353423.7091 9910.38423.34029930.434 420.762
9940.461420.44499950.489417.54179960.516411.80489970.543404.6467 9980.57399.3842
9990.597396.548110000.62396.370110010.65397.475710020.68400.4829 10030.7404.9983
10070.81410.845210100.89414.188810130.97421.7319   10141424.479810161.05433.9406
10181.11444.459110201.16456.204710211.19458.864210231.24458.637810237.42459.8342
#Mann= 3 , 0 , 0
9672.623    0.04       09672.623    0.04       010237.42    0.04       0
#XS Ineff= 2 , 0
       0                               0
Bank Sta=9672.623,10237.42
Exp/Cntr=0.3,0.1

Type RM Length L Ch R = 1 ,39497.52,99.010200,99.010200,99.010200
XS GIS Cut Line= 6
825465.293283878831768.199576933825529.038387653831754.634535863
825617.861930591831729.706506847825778.276875894831670.919049852
825840.578462418831655.590487659825934.446226197831640.204841931
#Sta/Elev= 30
9777.752440.10059808.123430.92319828.571426.52059869.725415.48579880.048414.1113
9890.383411.85429911.297409.52199921.754409.36469942.826406.74769953.504406.6543
9964.183405.01229974.861399.52829996.217393.0228    9999392.982910006.94393.2778
10017.69 396.32410028.44402.276410032.65403.626910081.61412.6889 10106.1420.9577
10123.32428.179710133.62433.580810143.92437.602810154.22440.598110195.05447.8868
10215.35454.485410235.64454.095410245.79456.173710255.89 463.949 10265.4466.0476
#Mann= 3 , 0 , 0
9777.752    0.04       09777.752    0.04       0 10265.4    0.04       0
#XS Ineff= 2 , 0
       0                               0
Bank Sta=9777.752,10265.4
Exp/Cntr=0.3,0.1

Type RM Length L Ch R = 1 ,39398.51,99.010100,99.010100,99.010100
XS GIS Cut Line= 6
825464.567021779831878.591419235825583.847542461 831847.89000494
825665.439833465 831819.87863242825828.760839337831752.423450259
825896.137526332831731.405389354825975.947594773831712.113153833
#Sta/Elev= 30
9730.441443.19519761.817429.56979772.149424.13189792.813415.14419803.145413.3046
9813.478410.50059834.142408.9971 9875.98407.95749886.552  407.869897.125409.0523
9907.698408.8212 9950.26402.46359971.971400.78439993.682391.394210004.56390.5594
10015.46392.047210026.36395.452910037.26404.007910048.16409.096110059.06412.4746
10091.19426.581410112.59 432.53110133.63434.305610165.05435.169210196.31437.6636
10216.89441.094710227.18443.812610237.47447.582210258.04447.765410269.31 448.978
#Mann= 3 , 0 , 0
9730.441    0.04       09730.441    0.04       010269.31    0.04       0
#XS Ineff= 2 , 0
       0                               0
Bank Sta=9730.441,10269.31
Exp/Cntr=0.3,0.1

Type RM Length L Ch R = 1 , 39299.5,99.010200,99.010200,99.010200
XS GIS Cut Line= 6
825468.284562033831964.693409747825517.156466417831953.606039339
825611.653309121831929.724834174825753.858904115831889.628710485
826017.581521004831812.978403862826031.992422694 831809.22052896
#Sta/Elev= 30
9703.668437.25269720.808429.20989751.571416.91329782.501409.76989813.444407.5609
 9829.72 407.9369854.727407.01189865.117407.58929875.507406.66789906.676406.4965
9917.066405.39139937.846401.30689969.016397.95649979.406393.34019989.796390.1866
10000.19390.1187 10010.6390.734710021.01396.950510052.26 420.03310073.08425.2043
10093.91428.682110135.57429.143510145.98429.939810156.39431.908110177.22432.4361
10229.29437.638310239.71439.497110260.53440.940210270.95445.701110288.53451.2961
#Mann= 3 , 0 , 0
9703.668    0.04       09703.668    0.04       010288.53    0.04       0
#XS Ineff= 2 , 0
       0                               0
Bank Sta=9703.668,10288.53
Exp/Cntr=0.3,0.1

Type RM Length L Ch R = 1 ,39200.49,99.010100,99.010100,99.010100
XS GIS Cut Line= 6
825481.799485587832049.161681925825654.759898723832009.698463807
825836.563871927831974.405858645825915.180661564831956.783712332
825997.581890513831934.321418061826082.584514709831906.733016871
#Sta/Elev= 30
 9697.73452.2583 9711.27448.34449731.784440.20559752.298430.24639762.555423.9603
9783.069418.10849806.348408.1576 9813.84406.4959 9885.57 402.337 9936.52398.3553
 9946.71396.3791 9977.28396.1679 9987.47391.19819997.661388.860710007.84388.6486
10018.02391.6174 10028.2400.621610038.38404.614310048.56406.165910099.72405.3215
10109.97407.308710147.68405.925510171.81406.945710192.54409.076210213.27412.7387
10244.62421.8941 10256.5424.357910276.16431.054710297.19431.479510315.68436.5813
#Mann= 3 , 0 , 0
 9697.73    0.04       0 9697.73    0.04       010315.68    0.04       0
#XS Ineff= 2 , 0
       0                               0
Bank Sta=9697.73,10315.68
Exp/Cntr=0.3,0.1

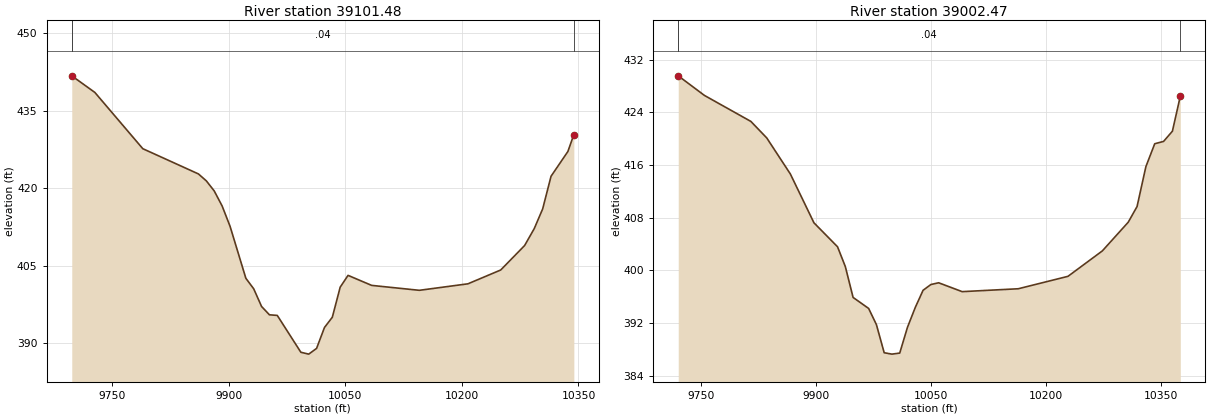
Type RM Length L Ch R = 1 ,39101.48,99.010200,99.010200,99.010200
XS GIS Cut Line= 6
825496.124156361 832142.98653749825706.789603797832096.575933121
825878.979109096832069.843012532825930.824547119832058.695811414
826033.965784931 832027.03873712826121.929276865 831990.54821077
#Sta/Elev= 30
9697.848441.78779727.584438.57069789.274427.68169860.812 422.8039871.007421.4614
9881.202 419.5099891.397416.58919901.591412.65689921.916402.60299932.031400.5578
9942.147397.14159952.262395.52749962.377395.40939992.723388.278410002.84387.9166
10012.96389.027210023.09393.067110033.21395.060410043.34400.878710053.46403.1627
10083.84401.221910145.22400.268310207.74401.526210249.95404.202510280.74408.9434
10293.14 412.22610303.93416.020910314.73422.347510336.44427.151110344.07430.4197
#Mann= 3 , 0 , 0
9697.848    0.04       09697.848    0.04       010344.07    0.04       0
#XS Ineff= 2 , 0
       0                               0
Bank Sta=9697.848,10344.07
Exp/Cntr=0.3,0.1

Type RM Length L Ch R = 1 ,39002.47,99.010100,99.010100,99.010100
XS GIS Cut Line= 6
825533.968101769832244.685051947825639.864157535832214.523014609
825736.004811323832192.912000164 825920.44617729832159.360660842
826023.143689226832121.125918751 826153.94254327832051.017713935
#Sta/Elev= 30
9720.392429.55269754.624426.57019815.067422.62789835.768420.11619866.516414.6449
9897.265407.22839928.013403.58549938.155400.58169948.285395.89169968.544394.2197
9978.674391.76389988.804387.48979998.934 387.28110009.06 387.441 10019.2 391.373
10029.34394.374410039.48396.974510049.62397.850310059.76398.119810090.43396.7718
10163.54397.209810228.35399.0987 10273.1402.958110306.84407.314410318.36409.6967
10329.87415.757110341.39419.237510352.91419.588810364.43421.142210374.73426.4629
#Mann= 3 , 0 , 0
9720.392    0.04       09720.392    0.04       010374.73    0.04       0
#XS Ineff= 2 , 0
       0                10068.86       0
Bank Sta=9720.392,10374.73
Exp/Cntr=0.3,0.1