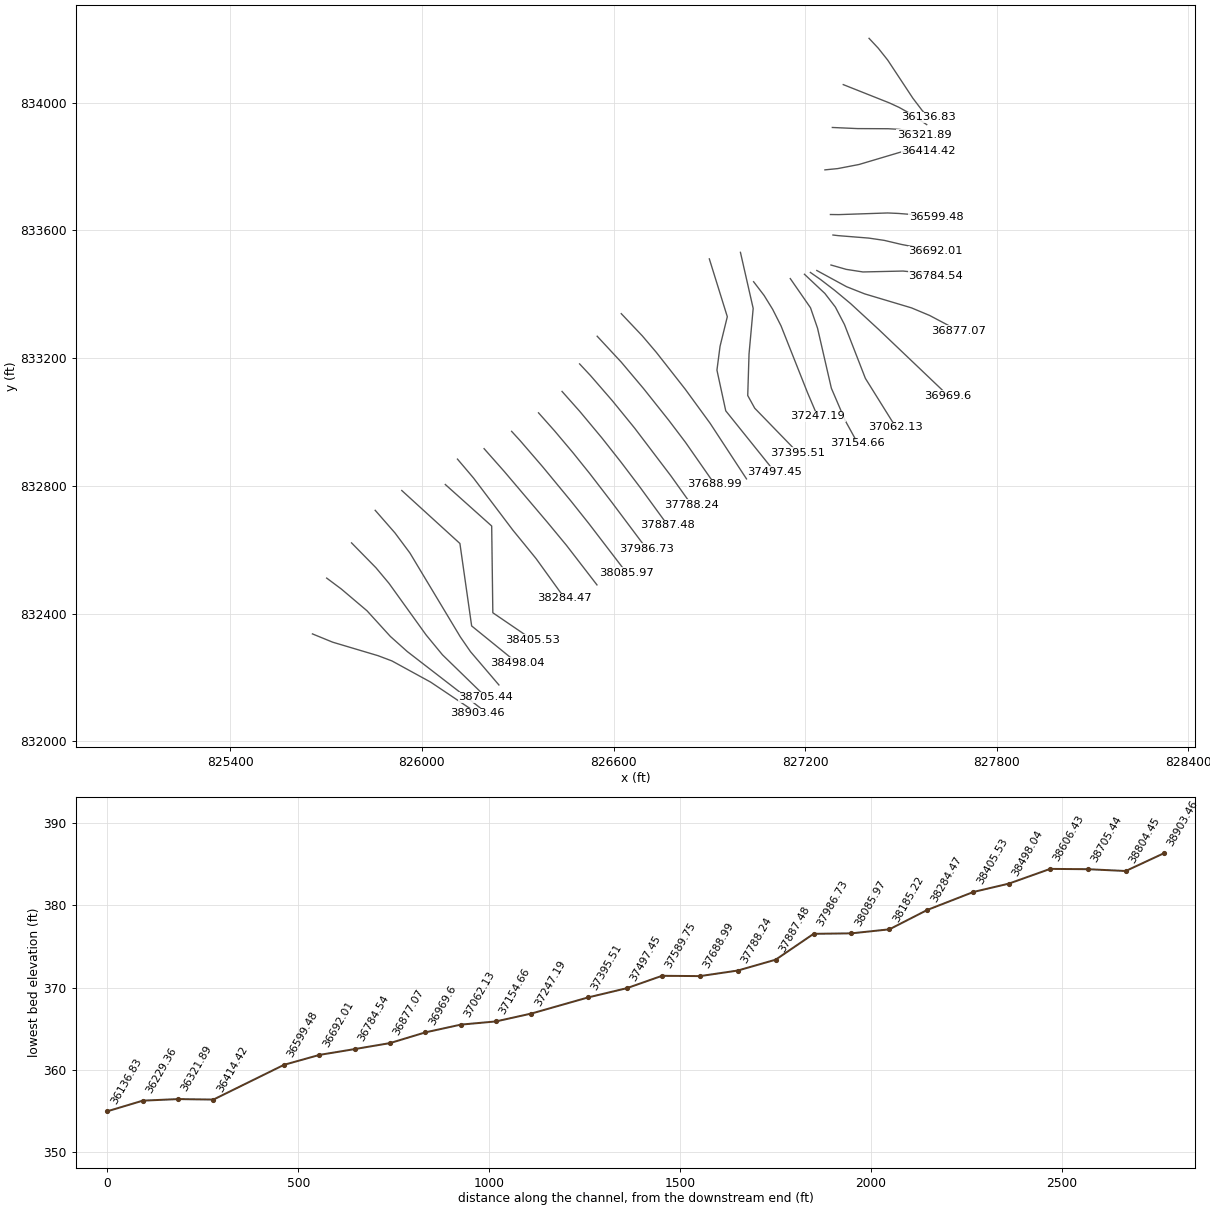
HEC-RAS study 18370_ras.prj: 18370

--- 18370_ras.g01 (geometry) --- (continued)

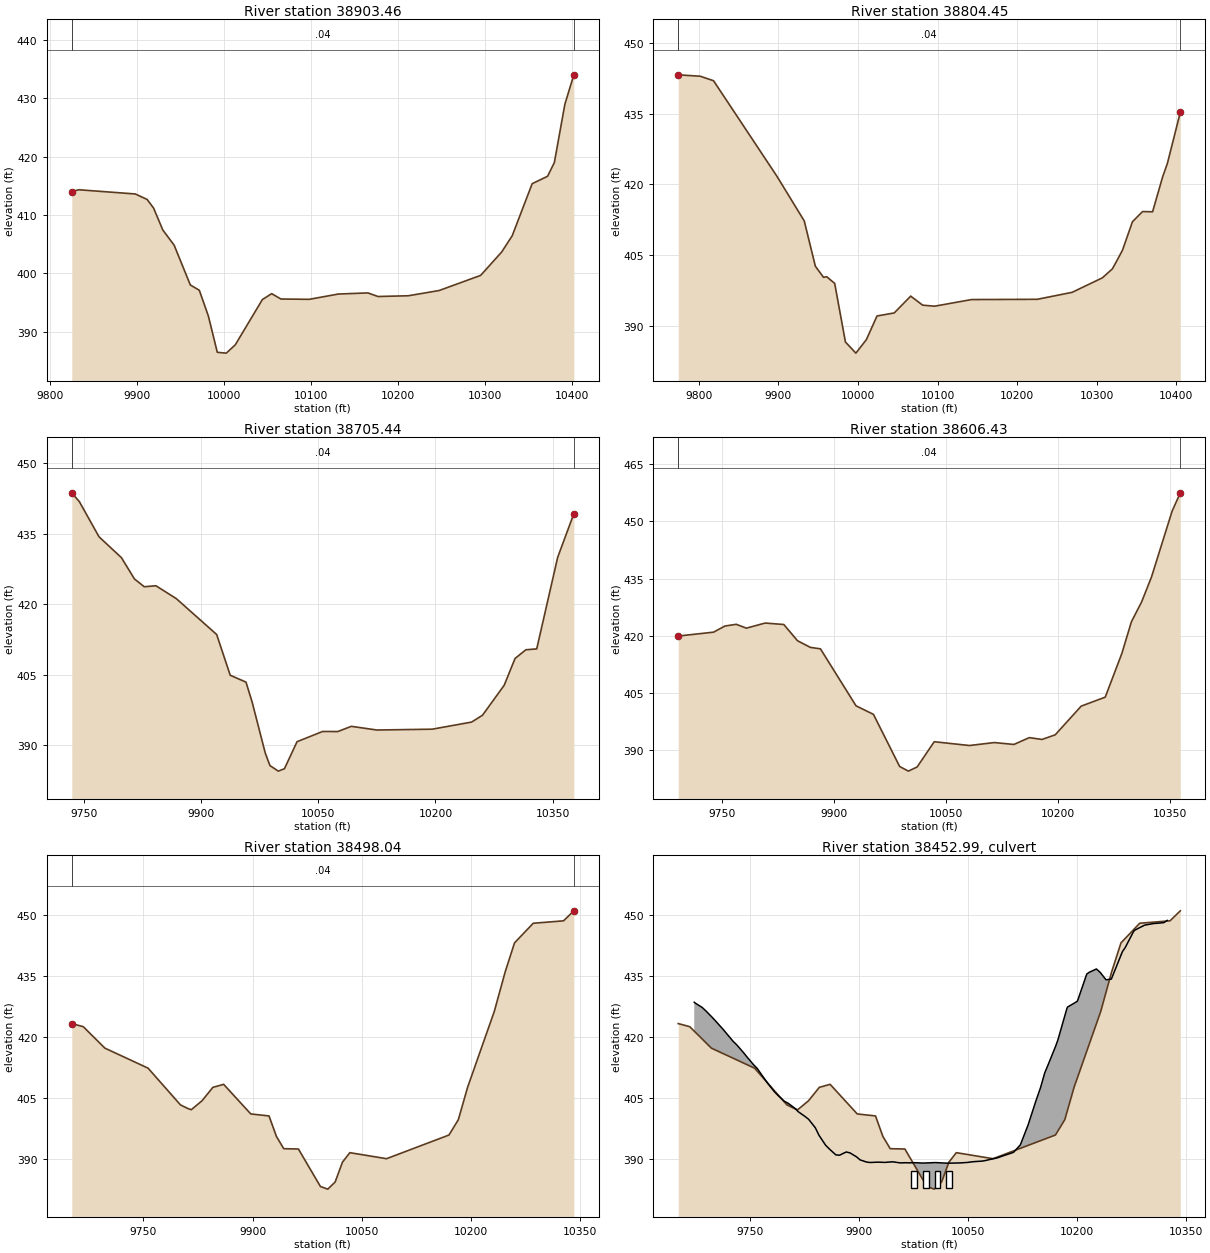
Type RM Length L Ch R = 1 ,38903.46,99.010200,99.010200,99.010200
XS GIS Cut Line= 6
825657.349906495 832336.78265927825720.747925092832310.835755002
825862.872509513832268.523050457825906.218742754832252.184882508
826027.552473114 832185.74840034826173.494201197832087.948623324
#Sta/Elev= 30
9824.638414.03389832.904414.33849897.631413.6202 9911.29412.68199918.753411.1908
9929.313407.44729942.391404.83469960.963398.02149971.306397.1126 9981.65 392.726
9991.994386.476610002.33386.338910012.67387.765210043.79395.516110054.48 396.531
10065.16395.613210097.66395.561110131.21396.467510165.15396.658610176.78396.0435
10211.66396.172210247.08397.070910294.82399.666410318.96 403.67110331.08406.4527
10354.04415.382810371.75416.651110379.54418.995310391.66429.013910401.95434.0405
#Mann= 3 , 0 , 0
9824.638    0.04       09824.638    0.04       010401.95    0.04       0
#XS Ineff= 2 , 0
       0                10107.49       0
Bank Sta=9824.638,10401.95
Exp/Cntr=0.3,0.1

Type RM Length L Ch R = 1 ,38804.45,99.010100,99.010100,99.010100
XS GIS Cut Line= 6
825701.952004385832511.509548389825747.935717378832477.183276406
 825828.17744086832409.192204676825901.381693426832328.784961432
825954.339067339832281.467712938826182.634274688832105.213206572
#Sta/Elev= 30
9774.165443.20449801.881442.90349818.534441.95279898.095421.71619932.487412.2315
9946.464402.61769956.701  400.279960.696400.39619970.755 398.9779984.236386.5557
9997.353384.196110010.56387.062510023.91392.073110045.55392.715410066.24396.2841
10081.25394.364910096.26394.147710142.68395.553610225.26395.606110269.06 397.087
10307.03 400.15410319.62 402.05710323.38403.197710332.26 405.99410344.89412.0604
10357.53414.210310370.17414.167110382.81421.577810388.79424.438710404.99435.2747
#Mann= 3 , 0 , 0
9774.165    0.04       09774.165    0.04       010404.99    0.04       0
#XS Ineff= 2 , 0
       0                 10118.3       0
Bank Sta=9774.165,10404.99
Exp/Cntr=0.3,0.1

Type RM Length L Ch R = 1 ,38705.44,99.010200,99.010200,99.010200
XS GIS Cut Line= 6
825779.775260392832621.759161061825856.338313182832543.764287921
825897.236666896 832494.82665325826012.926404093832333.895210905
826064.455741346832271.295939273826200.495455047 832138.95099167
#Sta/Elev= 30
 9734.78443.72289744.575441.82019769.632434.35799798.342429.90159814.978425.3657
9827.553423.70779842.418423.92059868.568421.16979920.173413.52639937.501404.8461
 9957.67403.38339965.569399.11059982.337 388.2529988.331385.5917    9999384.4144
10006.83384.922810022.99390.686910055.79  392.8710075.02392.844210092.51393.9608
 10125.1393.174210195.84 393.35210246.29394.866810260.28396.332810288.01402.7239
10301.87408.422810315.74410.2784 10329.6410.463510356.38429.958110377.09439.2768
#Mann= 3 , 0 , 0
 9734.78    0.04       0 9734.78    0.04       010377.09    0.04       0
#XS Ineff= 2 , 0
       0                10106.92       0
Bank Sta=9734.78,10377.09
Exp/Cntr=0.3,0.1

Type RM Length L Ch R = 1 ,38606.43,108.390500,108.390500,108.390500
XS GIS Cut Line= 6
825853.855467767832723.713202372825915.806827277832652.880324125
 825962.56574899832590.062867701826120.369746119832327.385416314
826152.143195599832281.238706604826241.195690242832176.943937726
#Sta/Elev= 30
9691.353419.91459738.647420.93569753.842422.53879769.036 422.9959782.641421.9827
9807.747423.32499832.679422.94479851.096418.67579868.217416.93839881.761416.5585
9929.358401.60569952.721399.35239987.766385.67949999.452384.453510011.13385.5309
 10034.1392.1705 10081.3391.175810114.52391.951410140.81391.456910161.36393.2464
10178.45392.770410196.08393.9887 10230.9401.519910263.06403.879610285.35415.3843
10298.12423.687610311.59428.801210325.08435.480210352.55452.690310363.55457.5116
#Mann= 3 , 0 , 0
9691.353    0.04       09691.353    0.04       010363.55    0.04       0
#XS Ineff= 2 , 0
       0                10101.05       0
Bank Sta=9691.353,10363.55
Exp/Cntr=0.3,0.1

Type RM Length L Ch R = 1 ,38498.04,92.508300,92.508300,92.508300
XS GIS Cut Line= 4
825937.120913357832785.692932606826119.086806267832619.861946464
826155.838538319832361.703438327826298.363548011832246.069939882
#Sta/Elev= 30
9651.385423.3851 9667.26422.61559696.952417.34279756.337412.41479800.875 403.379
9810.872402.50789815.721402.18919830.567 404.3999845.413407.68959860.259408.4389
9897.579401.15279922.692400.66049932.793395.63999942.894392.60549963.095392.5232
9993.398383.2885 10003.5382.6549 10013.6384.4056 10023.7389.2987 10033.8391.6237
10084.31390.142910170.14395.964410183.02399.739310195.89407.772210232.47426.3792
 10247.4436.077310260.28443.236410286.03448.0657 10327.7448.662410341.87451.1247
#Mann= 3 , 0 , 0
9651.385    0.04       09651.385    0.04       010341.87    0.04       0
#XS Ineff= 2 , 0
       0                10089.37       0
Bank Sta=9651.385,10341.87
Exp/Cntr=0.3,0.1

Type RM Length L Ch R = 2 ,38452.99,,,
Bridge Culvert--1,0,-1,-1, 0
Deck Dist Width WeirC Skew NumUp NumDn MinLoCord MaxHiCord MaxSubmerge Is_Ogee
18.754,55,2.6,0,96,96, , , 0.95, 0, 0,0,,
 9673.41 9675.23 9684.34 9689.37 9698.48 9703.51 9712.62 9717.65 9726.76 9731.79
 9740.91 9745.94 9755.05 9760.08 9769.19 9774.22 9783.33 9788.36 9797.47 9802.50
 9811.62 9816.65 9825.76 9830.79 9839.90 9844.93 9854.04 9859.07 9868.18 9873.22
 9882.33 9887.36 9896.47 9901.50 9910.61 9914.23 9915.26 9924.63 9925.58 9935.90
 9946.22 9956.53 9957.07 9965.03 9966.87 9977.20 9987.53 9997.8710004.7210008.20
10018.5310026.8810028.8310038.9410049.0510056.3510059.1710069.2810073.8510079.65
10081.9210090.2210100.7910111.3610112.7310121.9410132.5110143.0810143.5410149.73
10155.4010160.3010170.6710173.5310185.9410186.7610199.9910201.2210213.2310216.49
10226.4610231.7610239.6910247.0310252.9210262.3110266.1510277.5810279.3810292.61
10292.8510305.8410308.1210319.0710323.4010323.82
  428.63  428.37  427.35  426.51  424.85  423.87  422.06  420.99  419.04  418.17
  416.29  415.17  413.25  412.33  410.01  408.74  406.68  405.74  404.25  403.79
  402.57  401.67  400.53  399.82  397.75  395.91  393.47  392.55  391.08  391.00
  391.79  391.59  390.61  389.85  389.31  389.22  389.21  389.28  389.29  389.23
  389.38  389.11  389.11  389.16  389.12  389.16  389.07  389.13  389.19  389.16
  389.06  389.05  389.06  389.10  389.22  389.39  389.43  389.55  389.69  389.93
  390.02  390.35  391.01  391.64  391.75  393.57  398.44  404.26  404.49  407.69
  411.25  413.36  417.95  419.38  427.12  427.45  428.84  429.34  435.58  435.99
  436.82  435.97  434.16  434.33  436.95  441.11  442.10  446.05  446.38  447.59
  447.61  448.02  448.04  448.21  448.71  448.77
                                                                                
                                                                                
                                                                                
                                                                                
                                                                                
                                                                                
                                                                                
                                                                                
                                                                                
                                                
 9673.41 9675.23 9684.34 9689.37 9698.48 9703.51 9712.62 9717.65 9726.76 9731.79
 9740.91 9745.94 9755.05 9760.08 9769.19 9774.22 9783.33 9788.36 9797.47 9802.50
 9811.62 9816.65 9825.76 9830.79 9839.90 9844.93 9854.04 9859.07 9868.18 9873.22
 9882.33 9887.36 9896.47 9901.50 9910.61 9914.23 9915.26 9924.63 9925.58 9935.90
 9946.22 9956.53 9957.07 9965.03 9966.87 9977.20 9987.53 9997.8710004.7210008.20
10018.5310026.8810028.8310038.9410049.0510056.3510059.1710069.2810073.8510079.65
10081.9210090.2210100.7910111.3610112.7310121.9410132.5110143.0810143.5410149.73
10155.4010160.3010170.6710173.5310185.9410186.7610199.9910201.2210213.2310216.49
10226.4610231.7610239.6910247.0310252.9210262.3110266.1510277.5810279.3810292.61
10292.8510305.8410308.1210319.0710323.4010323.82
  428.63  428.37  427.35  426.51  424.85  423.87  422.06  420.99  419.04  418.17
  416.29  415.17  413.25  412.33  410.01  408.74  406.68  405.74  404.25  403.79
  402.57  401.67  400.53  399.82  397.75  395.91  393.47  392.55  391.08  391.00
  391.79  391.59  390.61  389.85  389.31  389.22  389.21  389.28  389.29  389.23
  389.38  389.11  389.11  389.16  389.12  389.16  389.07  389.13  389.19  389.16
  389.06  389.05  389.06  389.10  389.22  389.39  389.43  389.55  389.69  389.93
  390.02  390.35  391.01  391.64  391.75  393.57  398.44  404.26  404.49  407.69
  411.25  413.36  417.95  419.38  427.12  427.45  428.84  429.34  435.58  435.99
  436.82  435.97  434.16  434.33  436.95  441.11  442.10  446.05  446.38  447.59
  447.61  448.02  448.04  448.21  448.71  448.77
                                                                                
                                                                                
                                                                                
                                                                                
                                                                                
                                                                                
                                                                                
                                                                                
                                                                                
                                                
BR Coef=-1 , 0 , 0 ,, 0 ,,,0.8,-1,,0,
WSPro=,,,, 1 ,,,, 0 ,,,, 0 ,,,,-1 ,-1 ,-1 , 0 , 0 , 0 , 0 , 0
Multiple Barrel Culv=2,4,8,55,0.013,0.7,1,8,3,383,382,4,Culvert #1, 0, 18.754
 9976.00 9976.00 9992.00 9992.0010008.0010008.0010024.0010024.00
Culvert Bottom n=0.013
BC Design=,, 0 ,, 0 ,,,,,,

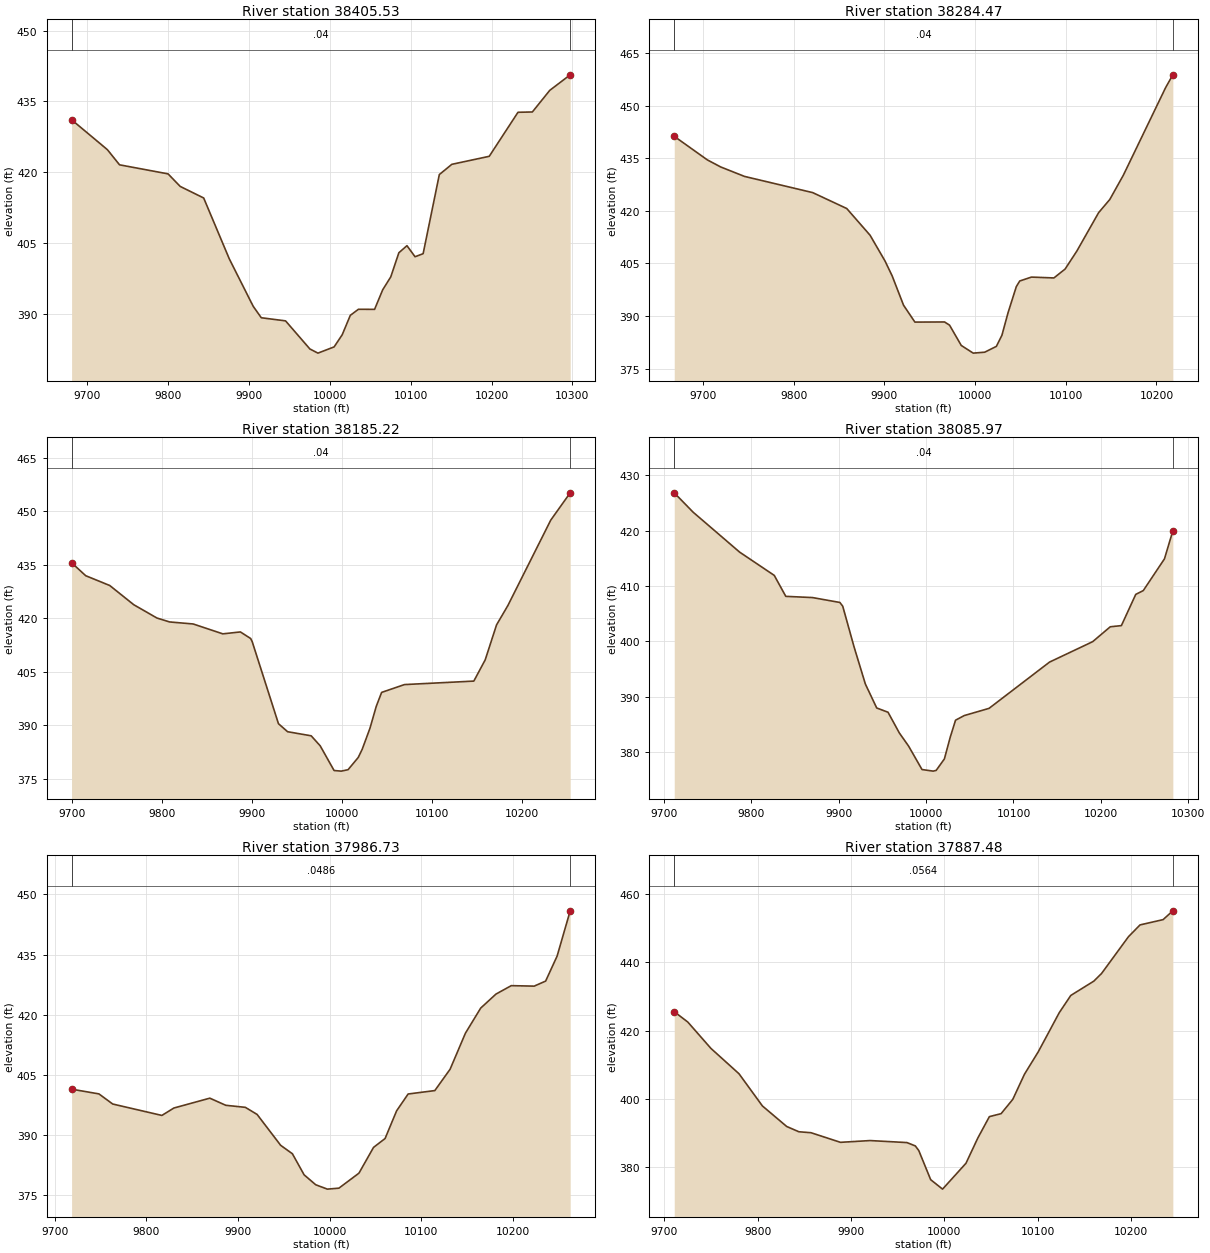
Type RM Length L Ch R = 1 ,38405.53,121.067000,121.067000,121.067000
XS GIS Cut Line= 4
826073.371237069832804.516990498826218.585397929832674.541352734
 826222.17093277832402.937088937826345.871884614832318.677020282
#Sta/Elev= 30
9681.065431.10519725.323424.76339740.318421.55349800.294419.63449815.288416.9757
9844.299414.52419875.952401.62319905.496391.56939915.497389.14279945.499388.4789
9975.502382.53349985.503 381.644 10005.5382.964510015.51385.543110025.51 389.653
10035.51390.933910055.51390.921810065.51395.054810075.51397.807510085.51402.9126
10095.51404.419110105.51402.074810115.51402.718110135.52419.4884   10151421.6587
 10197.2423.356110232.73432.687510250.49432.7554   10272437.336810297.25440.6272
#Mann= 3 , 0 , 0
9681.065    0.04       09681.065    0.04       010297.25    0.04       0
#XS Ineff= 2 , 0
       0                10071.63       0
Bank Sta=9681.065,10297.25
Exp/Cntr=0.3,0.1

Type RM Length L Ch R = 1 ,38284.47,99.245400,99.245400,99.245400
XS GIS Cut Line= 6
826111.401376555832884.094063733826161.789606198832824.669187435
826284.911057811832661.615341484826322.455967328832615.678158947
826357.738554345832572.274620845826446.888424053832448.581673045
#Sta/Elev= 30
9668.155441.24659704.644434.52969719.411432.51219745.633429.81889820.836425.2046
9858.428420.66849884.152 413.0569900.747405.6616 9908.55401.44879921.081393.1072
9933.612388.29369966.326388.32999971.842387.41779984.758381.6326 9997.93379.4489
10010.58379.714910023.46381.367210029.62384.563110036.35390.965410045.46398.3974
10049.24400.007210062.13401.121510086.94400.878710099.27403.410110112.27408.5513
10136.25 419.48310148.57423.239210163.58430.189410210.21455.157610218.12458.7723
#Mann= 3 , 0 , 0
9668.155    0.04       09668.155    0.04       010218.12    0.04       0
#XS Ineff= 2 , 0
       0                               0
Bank Sta=9668.155,10218.12
Exp/Cntr=0.3,0.1

Type RM Length L Ch R = 1 ,38185.22,99.245500,99.245500,99.245500
XS GIS Cut Line= 6
826194.777909646832916.737584789826257.613681327832845.722143617
826390.125978354832689.548105127826391.433238809832688.034477001
826452.392315286832614.448155652826548.182277521832490.179922495
#Sta/Elev= 30
 9699.36435.50189715.032431.87069741.737 429.1279768.443423.73679794.183420.0113
9808.245418.90919834.474418.33799867.426 415.5719886.933416.10849898.339414.2666
9900.048 413.4059929.251390.38819939.391388.14039965.621386.99159975.621384.1889
9991.077377.2595    9999 377.09210006.59377.492710017.93 380.92810022.27383.1919
10030.91389.086810037.94395.2603 10043.9399.160510069.29401.351410146.36402.3274
10158.99408.268410171.62418.085510184.24423.525910231.87447.457410253.46 455.101
#Mann= 3 , 0 , 0
 9699.36    0.04       0 9699.36    0.04       010253.46    0.04       0
#XS Ineff= 2 , 0
       0                               0
Bank Sta=9699.36,10253.46
Exp/Cntr=0.3,0.1

Type RM Length L Ch R = 1 ,38085.97,99.245400,99.245400,99.245400
XS GIS Cut Line= 6
826281.008909396832970.939927495826307.702641563832941.760715143
826378.159932123832860.055830977826467.188857259832752.132058675
826522.520901034832682.587367049 826640.81644408832528.151038293
#Sta/Elev= 30
9711.658426.79449733.262423.30589786.542416.09769826.156411.90239839.361408.1219
9869.843407.90579901.272407.02099904.538406.34649917.502399.00679930.465 392.302
9943.429387.99439956.392387.22049969.355383.48029979.846381.13769995.282376.8883
10008.13376.602810011.53376.7421 10020.9 378.80510027.59382.722410033.68385.7915
10043.66386.624810072.01387.921910141.28396.269810190.62 399.948 10210.8402.6358
10223.51402.847810239.95408.475510248.59409.166110272.84414.893610282.41419.9439
#Mann= 3 , 0 , 0
9711.658    0.04       09711.658    0.04       010282.41    0.04       0
#XS Ineff= 2 , 0
       0                10054.14       0
Bank Sta=9711.658,10282.41
Exp/Cntr=0.3,0.1

Type RM Length L Ch R = 1 ,37986.73,99.245500,99.245500,99.245500
XS GIS Cut Line= 6
826365.200298932833028.958015248826415.499609617832972.415697738
826472.984471309832904.194710552826526.327257747832837.789688509
826594.216130877832749.438308116 826703.55044046832603.565310566
#Sta/Elev= 30
9718.487401.45849748.276400.28439763.322  397.769816.938394.91369830.015396.7585
9869.245399.21959886.594397.44319907.996396.92999920.823395.16059946.476387.4709
9959.303385.35839972.085380.1054 9984.75377.63049997.415376.542710010.02 376.784
10031.89 380.52510047.79 386.94810060.38389.157310072.97 396.06510085.52400.2563
10114.63401.1093 10131.3406.435510148.01 415.41910164.65421.666510181.32425.1668
   10198427.267210222.99427.147110235.49428.407810248.02 434.64910262.27445.9207
#Mann= 3 , 0 , 0
9718.487  0.0486       09718.487  0.0486       010262.27  0.0486       0
#XS Ineff= 2 , 0
       09893.739                       0
Bank Sta=9718.487,10262.27
Exp/Cntr=0.3,0.1

Type RM Length L Ch R = 1 ,37887.48,99.245400,99.245400,99.245400
XS GIS Cut Line= 6
826438.886441849833095.897626096826494.481255327833033.341239012
826564.427113407832949.383609803 826623.60289752832874.354011149
826682.523354919832796.597950736826770.015620002832676.581551056
#Sta/Elev= 30
9710.476425.53359725.055422.48289749.786414.75319779.894407.30549805.023397.8361
9831.054391.8044 9844.07390.25579857.086389.97399888.715387.14879920.516387.6655
9959.969387.0765 9968.96386.09479972.705384.71319985.441376.16939998.177373.3973
10023.29380.998310035.84388.338410048.38394.698110060.93395.573110073.47399.7775
10086.02407.171910100.76 413.73410123.29425.240410135.66430.306710160.41434.5214
10168.66436.763910197.54447.578710209.91451.029110234.66452.588610245.08455.1707
#Mann= 3 , 0 , 0
9710.476  0.0564       09710.476  0.0564       010245.08  0.0564       0
#XS Ineff= 2 , 0
       09899.416                       0
Bank Sta=9710.476,10245.08
Exp/Cntr=0.3,0.1

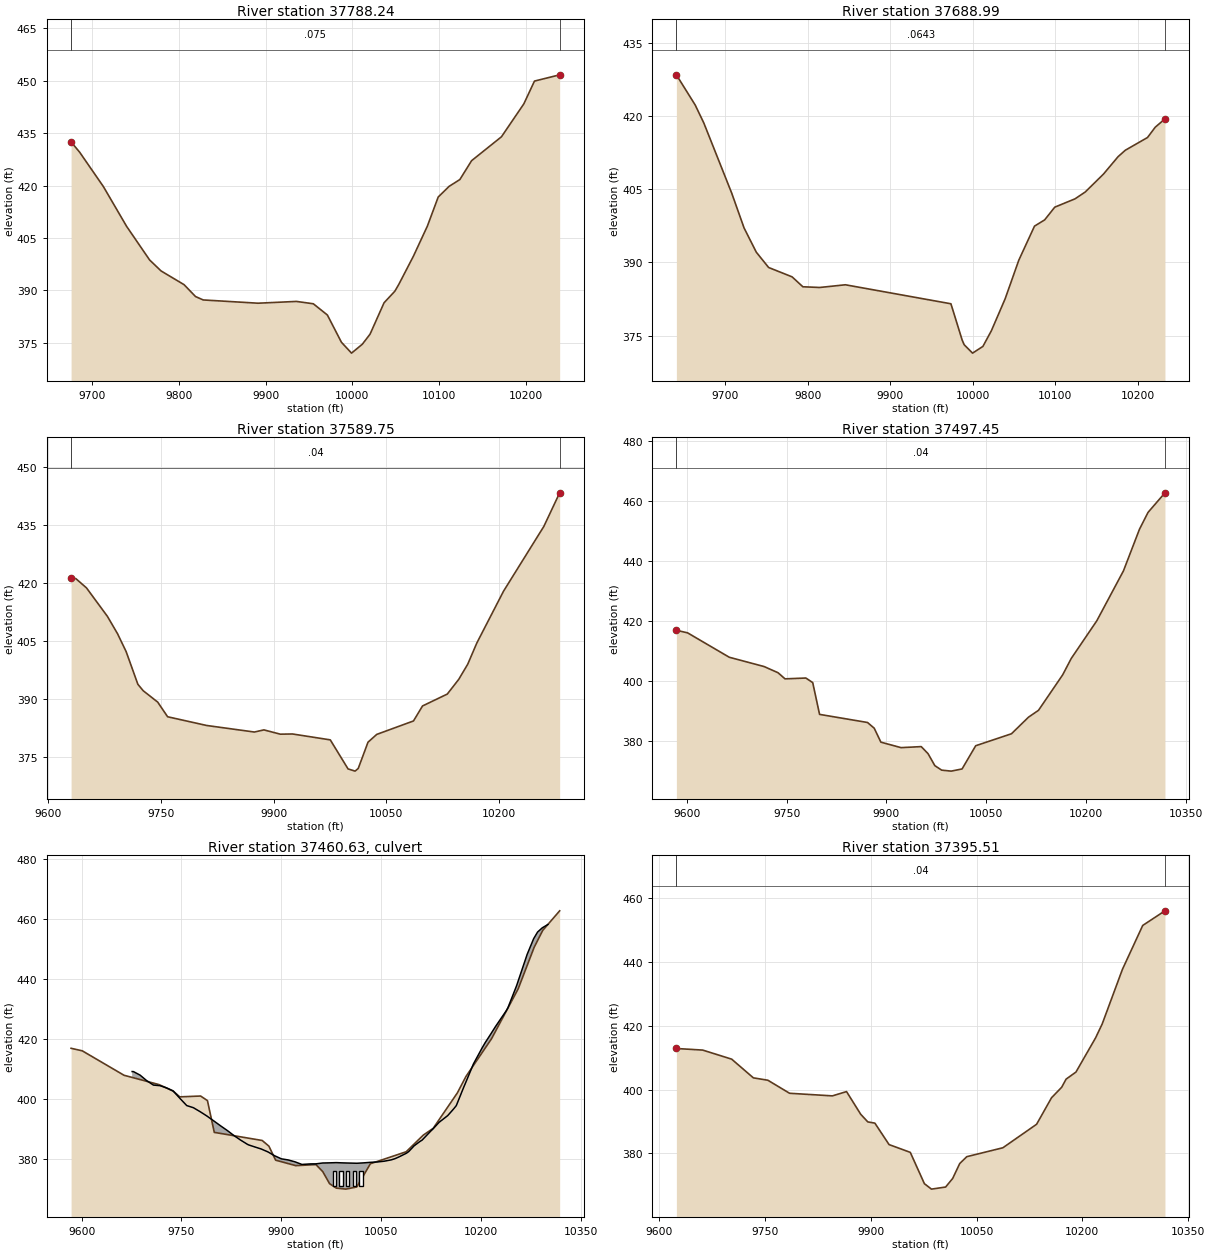
Type RM Length L Ch R = 1 ,37788.24,99.245500,99.245500,99.245500
XS GIS Cut Line= 6
 826493.77930307833182.157836591826528.461303966833144.999168151
826596.182282138833066.930860302 826665.63832431832981.695449207
 826779.63921302832831.561726654826843.974009601832741.358899181
#Sta/Elev= 30
9675.537432.47079685.329429.56489712.687419.74639739.604408.3175 9766.08398.7215
9779.318395.57499805.794391.65829819.033388.2567 9827.91387.28279891.164386.3502
9935.403386.85989954.861386.18979971.092382.97649987.323375.17019998.949372.0722
10011.46374.635410020.33 377.50610036.45386.471510048.94389.7893 10053.7391.8443
10070.39399.837610086.41408.399310098.91416.7192 10111.4419.754410123.89421.7242
10137.42427.117410171.86433.955910197.66443.368510209.94449.884810238.98451.6711
#Mann= 3 , 0 , 0
9675.537   0.075       09675.537   0.075       010238.98   0.075       0
#XS Ineff= 2 , 0
       09902.299                       0
Bank Sta=9675.537,10238.98
Exp/Cntr=0.3,0.1

Type RM Length L Ch R = 1 ,37688.99,99.245400,99.245400,99.245400
XS GIS Cut Line= 6
826548.876735758833268.739516533826624.225842505833187.669487179
826693.809099164833105.147844292826773.601554885833004.849381566
  826825.2229329832936.651664474826916.889499837832805.222811313
#Sta/Elev= 30
9640.449428.44759663.285422.25879673.758418.56949707.646404.15969722.532397.0635
9737.418392.08019752.353388.94839780.805387.02939793.885384.99529814.404384.8532
9845.429385.40549973.445381.51059987.068374.08039989.546 373.1129999.714371.3939
10012.25372.773110022.58376.0078 10039.2382.526210055.81390.458610074.82397.4287
10087.12398.706910099.42401.319910124.02403.028910136.32404.422210158.43408.0893
10176.24411.677310184.98412.988310211.87415.595410221.23417.702710233.04419.4153
#Mann= 3 , 0 , 0
9640.449  0.0643       09640.449  0.0643       010233.04  0.0643       0
#XS Ineff= 2 , 0
       09897.866                       0
Bank Sta=9640.449,10233.04
Exp/Cntr=0.3,0.1

Type RM Length L Ch R = 1 ,37589.75,92.298200,92.298200,92.298200
XS GIS Cut Line= 6
826624.279858319833339.413496867826690.316273279833269.705238674
826734.220748033833218.041414094826824.041017539833103.580483018
826902.509931883832996.044784167827016.355729684832822.103124402
#Sta/Elev= 30
 9630.32421.45679636.584421.19089650.778418.79819678.683 411.4299692.194406.9264
9703.596402.32229719.217393.87179726.371 392.2029745.669389.25959758.793385.4847
9810.748383.23069874.305381.53579887.016382.08959908.823380.98229925.021381.0343
9975.327379.5112    9999372.004410008.39371.432110012.57372.131610025.56378.9064
10037.17 380.92210086.09384.397810098.14388.275510131.11391.352410146.31395.1431
10158.35399.080310170.39404.536210206.01417.955710259.63434.682110280.69443.3597
#Mann= 3 , 0 , 0
 9630.32    0.04       0 9630.32    0.04       010280.69    0.04       0
#XS Ineff= 2 , 0
       0 9893.14                       0
Bank Sta=9630.32,10280.69
Exp/Cntr=0.3,0.1

Type RM Length L Ch R = 1 ,37497.45,101.935000,101.935000,101.935000
XS GIS Cut Line= 6
826900.000517547833510.960381418826956.302722275833329.860014766
 826933.56937921833237.302832365 826923.82651791833162.607562363
 826951.43129161833035.138460293827104.069452047 832845.15266484
#Sta/Elev= 30
9584.158416.94059600.999416.08989663.705407.93639716.065404.8341 9737.01402.7674
9747.482400.72629778.813 401.003 9789.11399.47949799.408388.86779871.439386.1627
9881.524384.26489891.609379.58889921.863377.76559952.229378.1074 9962.46375.7568
9972.692 371.7479982.924370.25419997.236369.923210013.62370.648910034.08378.3959
10087.87382.398110113.53387.944810128.47390.218610164.84402.063410177.67407.5164
10216.15420.1176 10256.2 436.77410280.29450.674910293.12456.285410318.58462.8322
#Mann= 3 , 0 , 0
9584.158    0.04       09584.158    0.04       010318.58    0.04       0
#XS Ineff= 2 , 0
       0                               0
Bank Sta=9584.158,10318.58
Exp/Cntr=0.3,0.1

Type RM Length L Ch R = 2 ,37460.63,,,
Bridge Culvert--1,0,-1,-1, 0
Deck Dist Width WeirC Skew NumUp NumDn MinLoCord MaxHiCord MaxSubmerge Is_Ogee
23.467,55,2.6,0,84,84, , , 0.95, 0, 0,0,,
 9675.94 9677.86 9687.88 9697.89 9707.90 9717.91 9727.93 9737.94 9747.95 9757.96
 9765.27 9768.02 9778.19 9788.36 9796.00 9798.52 9808.69 9818.86 9829.03 9839.20
 9849.36 9851.25 9859.53 9869.70 9879.87 9890.04 9900.20 9906.49 9910.37 9914.61
 9920.69 9931.12 9941.55 9944.64 9951.98 9962.41 9965.36 9972.70 9982.93 9993.03
 9993.1710003.4010013.6410023.8710034.1110040.0110044.3410054.5810058.5110065.54
10071.0710076.9610088.3710091.7910099.7910108.9210111.5110111.6610124.4310127.45
10137.3510143.2410150.2710159.0410163.1910174.8310176.1110189.0310190.6210201.95
10206.4110214.8810222.2010227.8010238.0010240.7210253.6410253.7910266.5610269.58
10279.4810285.3710292.4010301.03
  409.18  409.16  407.98  406.12  404.66  404.46  403.68  402.62  400.17  397.82
  397.30  397.10  395.77  394.32  393.11  392.72  391.08  389.51  387.79  386.26
  384.86  384.67  384.06  383.34  382.37  381.07  380.04  379.81  379.67  379.41
  379.04  378.16  378.31  378.35  378.36  378.65  378.66  378.70  378.77  378.68
  378.68  378.62  378.56  378.69  378.87  378.94  378.99  379.24  379.40  379.70
  380.09  380.68  381.93  382.49  384.39  385.90  386.23  386.26  389.22  389.87
  392.24  393.25  394.47  396.66  397.81  404.21  404.86  411.77  412.40  417.05
  418.75  421.66  424.22  426.06  429.38  430.43  437.73  437.82  446.22  448.23
  453.54  455.75  457.15  458.29
                                                                                
                                                                                
                                                                                
                                                                                
                                                                                
                                                                                
                                                                                
                                                                                
                                
 9675.94 9677.86 9687.88 9697.89 9707.90 9717.91 9727.93 9737.94 9747.95 9757.96
 9765.27 9768.02 9778.19 9788.36 9796.00 9798.52 9808.69 9818.86 9829.03 9839.20
 9849.36 9851.25 9859.53 9869.70 9879.87 9890.04 9900.20 9906.49 9910.37 9914.61
 9920.69 9931.12 9941.55 9944.64 9951.98 9962.41 9965.36 9972.70 9982.93 9993.03
 9993.1710003.4010013.6410023.8710034.1110040.0110044.3410054.5810058.5110065.54
10071.0710076.9610088.3710091.7910099.7910108.9210111.5110111.6610124.4310127.45
10137.3510143.2410150.2710159.0410163.1910174.8310176.1110189.0310190.6210201.95
10206.4110214.8810222.2010227.8010238.0010240.7210253.6410253.7910266.5610269.58
10279.4810285.3710292.4010301.03
  409.18  409.16  407.98  406.12  404.66  404.46  403.68  402.62  400.17  397.82
  397.30  397.10  395.77  394.32  393.11  392.72  391.08  389.51  387.79  386.26
  384.86  384.67  384.06  383.34  382.37  381.07  380.04  379.81  379.67  379.41
  379.04  378.16  378.31  378.35  378.36  378.65  378.66  378.70  378.77  378.68
  378.68  378.62  378.56  378.69  378.87  378.94  378.99  379.24  379.40  379.70
  380.09  380.68  381.93  382.49  384.39  385.90  386.23  386.26  389.22  389.87
  392.24  393.25  394.47  396.66  397.81  404.21  404.86  411.77  412.40  417.05
  418.75  421.66  424.22  426.06  429.38  430.43  437.73  437.82  446.22  448.23
  453.54  455.75  457.15  458.29
                                                                                
                                                                                
                                                                                
                                                                                
                                                                                
                                                                                
                                                                                
                                                                                
                                
BR Coef=-1 , 0 , 0 ,, 0 ,,,0.8,-1,,0,
WSPro=,,,, 1 ,,,, 0 ,,,, 0 ,,,,-1 ,-1 ,-1 , 0 , 0 , 0 , 0 , 0
Multiple Barrel Culv=2,5,5,55,0.013,0.7,1,8,3,371,370,5,Culvert #1, 0, 23.467
 9980.00 9980.00 9990.00 9990.0010000.0010000.0010010.0010010.0010020.0010020.00
Culvert Bottom n=0.013
BC Design=,, 0 ,, 0 ,,,,,,

Type RM Length L Ch R = 1 ,37395.51,148.326100,148.326100,148.326100
XS GIS Cut Line= 6
826997.397935868833531.392736471827037.287516774833355.930178217
 827024.29703504833213.034879065 827020.23750952833083.130061663
827042.158947439833043.346711314827176.935195507832904.510937727
#Sta/Elev= 30
9624.708412.92239662.029412.4235 9703.05 409.5819733.815403.70979754.325402.9629
9785.091398.87339845.746398.05249865.829399.40139885.911392.28569895.952389.8883
9905.994389.50029926.076382.77199956.171380.3265 9976.18370.49189986.185 368.791
 10006.2369.4485 10016.2372.1257 10026.2376.814710036.21378.971710087.38381.7704
10135.16389.147810156.32397.470110170.67400.754310176.97403.3165 10190.9405.5237
10218.78416.2795 10228.1 420.62710256.81437.779810285.53 451.53810317.02456.1256
#Mann= 3 , 0 , 0
9624.708    0.04       09624.708    0.04       010317.02    0.04       0
#XS Ineff= 2 , 0
       0                               0
Bank Sta=9624.708,10317.02
Exp/Cntr=0.3,0.1

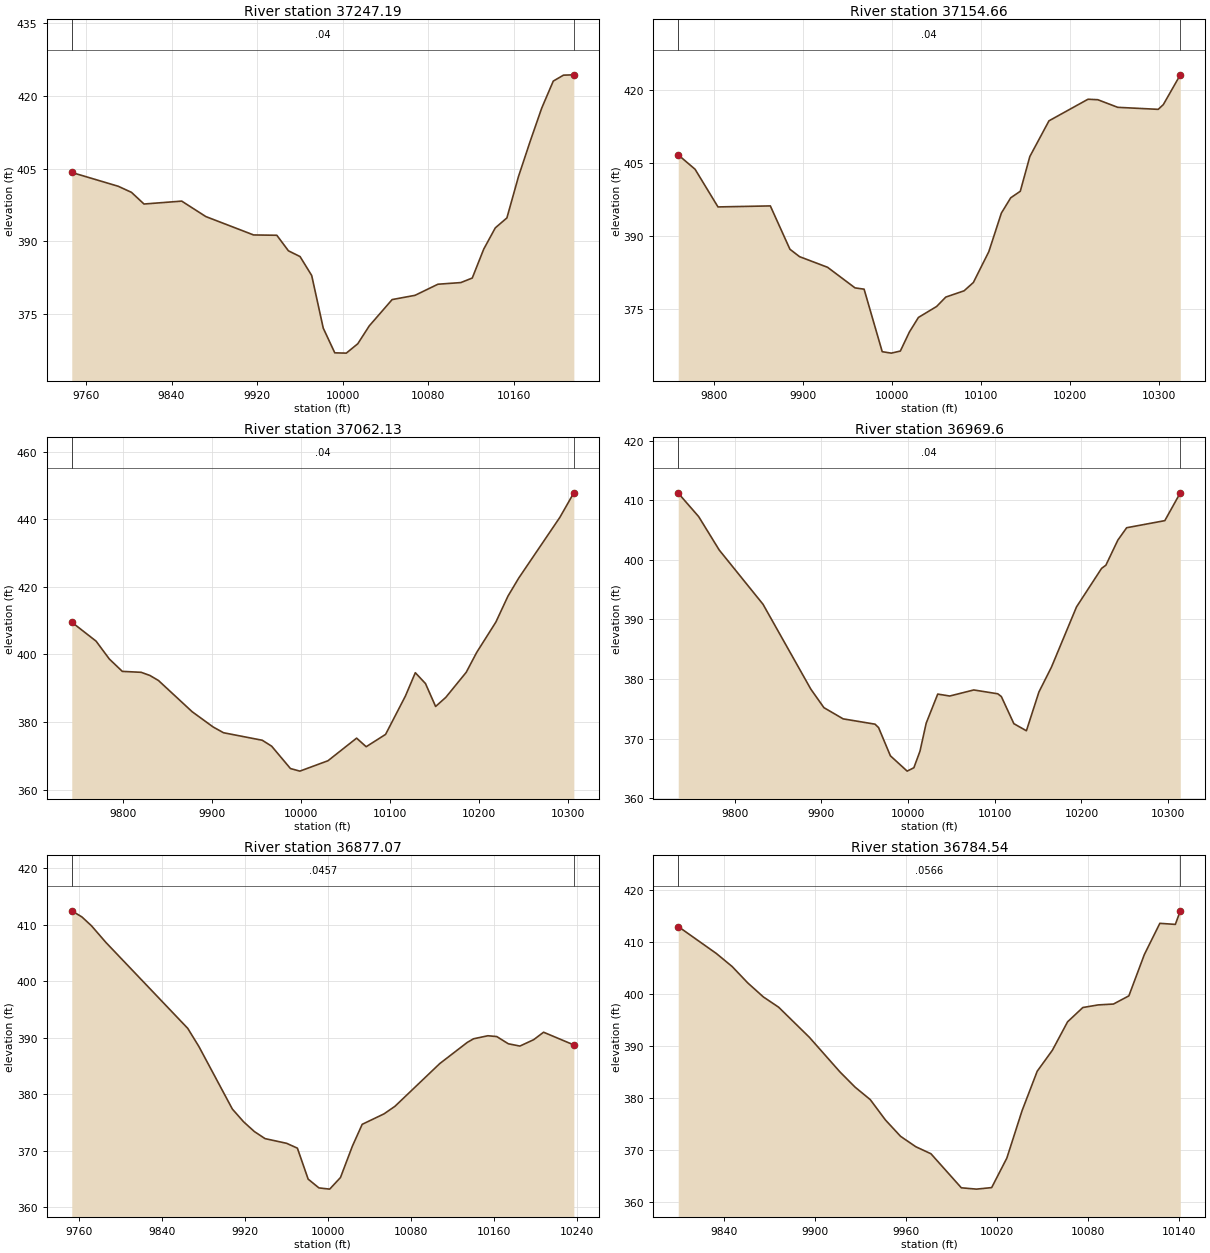
Type RM Length L Ch R = 1 ,37247.19,92.529800,92.529800,92.529800
XS GIS Cut Line= 6
827038.622813457833439.397060811 827071.48005316 833396.43748732
827098.202821343833353.084566897827124.551450066833301.050405303
827206.802673402833093.543244328827239.137545205833017.474374404
#Sta/Elev= 30
9746.741404.18849790.159401.33419802.514400.08199814.261397.66279849.502398.2639
9872.023395.06899916.651391.26739938.383391.20259949.248387.98749960.114386.7949
9970.979382.88699981.787372.00129992.559366.891810003.33 366.83310014.06368.7722
10024.76372.458210046.16377.904810067.56378.784210088.96381.078910110.36 381.419
10121.06 382.36110131.76388.333210142.58392.732410153.41394.788510164.25403.3459
10175.09410.570910185.92417.469610196.76423.0776 10206.3424.307810215.99424.3751
#Mann= 3 , 0 , 0
9746.741    0.04       09746.741    0.04       010215.99    0.04       0
#XS Ineff= 2 , 0
       0                               0
Bank Sta=9746.741,10215.99
Exp/Cntr=0.3,0.1

Type RM Length L Ch R = 1 ,37154.66,92.529800,92.529800,92.529800
XS GIS Cut Line= 6
827153.489862354833449.190688678827216.774871302833357.881281633
827238.813013598833293.817093791 827282.05227038833105.982564615
827325.625636103833004.382815358827364.558199864832933.456638655
#Sta/Elev= 30
9760.291406.63189779.201403.67889804.944 395.9329863.734396.14169885.742387.2322
9896.527385.71019928.026383.52289958.847379.28889969.032379.02479989.403366.1691
9999.585365.875310009.74366.299110019.91370.212410030.07373.2129 10050.5375.4677
10060.79377.398310081.35378.687610091.76380.394910109.14386.743710123.21394.6636
10133.71397.809510144.46399.1507 10155.2406.302610176.68413.634210220.51418.0727
10231.55417.973610253.92416.409810299.38415.994510305.12416.971710324.19 423.092
#Mann= 3 , 0 , 0
9760.291    0.04       09760.291    0.04       010324.19    0.04       0
#XS Ineff= 2 , 0
       0                               0
Bank Sta=9760.291,10324.19
Exp/Cntr=0.3,0.1

Type RM Length L Ch R = 1 ,37062.13,92.529800,92.529800,92.529800
XS GIS Cut Line= 6
827197.822387741833462.746915442827261.810940798833402.653327235
827294.549777323 833360.19392415827322.999574106833305.569198704
827388.547544405  833136.8716328827483.978301412832983.854112715
#Sta/Elev= 30
9741.915409.54029769.272403.93329784.202398.64039798.788394.98949819.976394.7136
9829.799393.78469839.463392.29189877.346383.05689901.051378.52669912.634376.8376
9956.244374.61479966.808372.85649987.937366.24729998.502365.481210030.13 368.547
10062.37 375.23710073.15372.700210094.97376.348810117.27387.687310128.42394.5948
10139.84391.396910151.26384.609510162.67387.289510185.69394.718110197.44400.5846
10219.06409.575910232.69417.267610244.77422.595110290.97440.527410306.77 447.812
#Mann= 3 , 0 , 0
9741.915    0.04       09741.915    0.04       010306.77    0.04       0
#XS Ineff= 2 , 0
       0                10058.58       0
Bank Sta=9741.915,10306.77
Exp/Cntr=0.3,0.1

Type RM Length L Ch R = 1 , 36969.6,92.529800,92.529800,92.529800
XS GIS Cut Line= 6
827216.407214841833468.429879098827248.221786677833446.324545862
827292.677430495833412.216920716827342.008909164833371.180634932
827430.237872288833289.939666127827647.604637648833082.802717082
#Sta/Elev= 30
9734.954411.1727 9758.49407.24569782.238401.63239832.748 392.5329887.923378.2892
9903.002375.1856  9925.2373.3073 9961.94372.41669966.048371.84589979.664367.1132
    9999364.539410006.76365.109210013.83367.897510020.97372.582310034.28377.4654
10048.14377.138110075.84 378.15610103.55377.513610107.67377.046210122.12372.4969
10136.57371.311810151.02377.821510165.47381.989810194.37392.093110223.27398.5502
10228.23399.083310242.08403.304910252.21405.369410296.21406.561410314.09411.2272
#Mann= 3 , 0 , 0
9734.954    0.04       09734.954    0.04       010314.09    0.04       0
#XS Ineff= 2 , 0
       0                 10057.9       0
Bank Sta=9734.954,10314.09
Exp/Cntr=0.3,0.1

Type RM Length L Ch R = 1 ,36877.07,92.529800,92.529800,92.529800
XS GIS Cut Line= 6
827236.485306892833474.569460962827329.653146798833423.814518702
827386.267383907833401.378971108827533.025387311833357.503101726
827589.556419338 833333.84538247827680.390135465833285.852904065
#Sta/Elev= 30
9753.016412.48519762.869411.39319772.037409.83559786.011406.8781 9864.89 391.685
9875.647388.47169907.917377.40759918.673375.16689929.105373.4284 9939.49372.1721
 9960.26371.34459970.645370.48529981.029365.00539991.414363.4541 10001.8363.2358
10012.21365.288810023.67370.829310033.15374.702110054.24376.557910064.79377.8979
10107.92385.443710134.54389.202410140.61389.842610154.42390.377710162.94390.2359
10174.11388.957110185.28388.550910198.55389.680110208.11391.001710237.31388.7505
#Mann= 3 , 0 , 0
9753.016  0.0457       09753.016  0.0457       010237.31  0.0457       0
#XS Ineff= 2 , 0
       0                               0
Bank Sta=9753.016,10237.31
Exp/Cntr=0.3,0.1

Type RM Length L Ch R = 1 ,36784.54,92.529800,92.529800,92.529800
XS GIS Cut Line= 6
827280.859325669833491.736792978827328.579731127833478.100135838
827380.953267382833469.998943601827506.406083105833472.821218079
827568.788281378833466.564605639827608.212367264833458.219821167
#Sta/Elev= 30
9809.518412.99859834.671407.81569845.056405.3174 9855.44402.14389865.654399.4702
9875.773 397.4869896.011391.70999916.203385.04999926.207 382.1149936.212379.7187
9946.217375.80499956.224372.65649966.242370.6614 9976.26369.30569996.295362.7614
10006.31362.506310016.32362.803110026.32368.474210036.33 377.55910046.35385.1715
10056.37389.212410066.39394.677110076.45397.424310086.55397.928310096.65398.0948
10106.83399.667610117.05407.620310127.27413.616110137.49413.409810140.77416.0201
#Mann= 3 , 0 , 0
9809.518  0.0566       09809.518  0.0566       010140.77  0.0566       0
#XS Ineff= 2 , 0
       0                               0
Bank Sta=9809.518,10140.77
Exp/Cntr=0.3,0.1

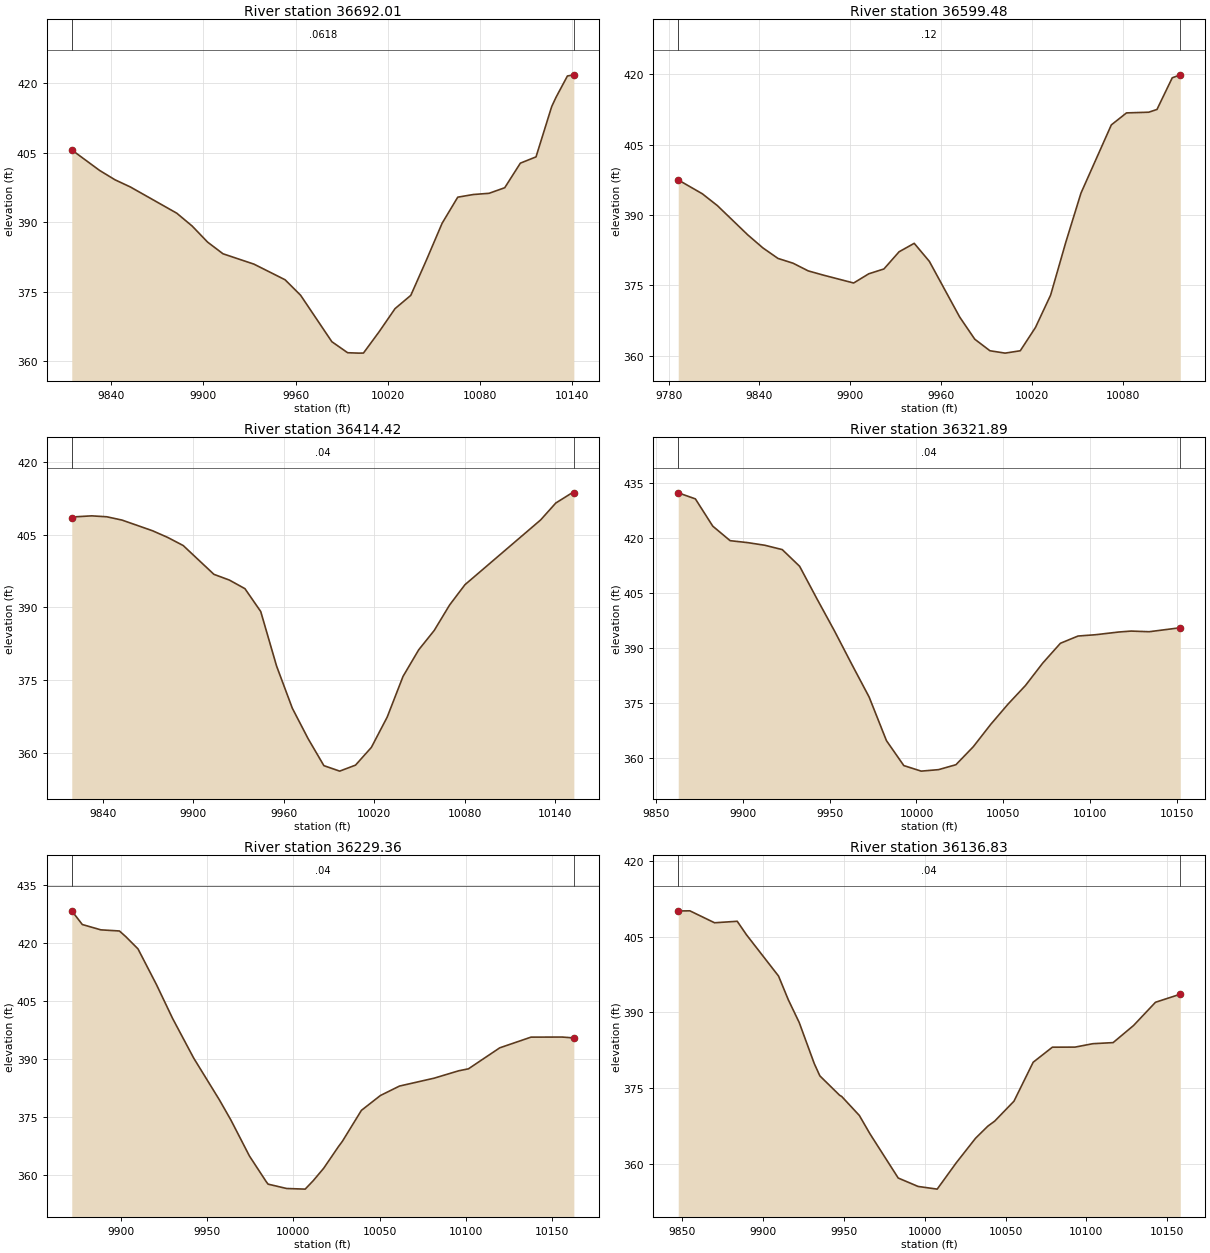
Type RM Length L Ch R = 1 ,36692.01,92.529900,92.529900,92.529900
XS GIS Cut Line= 6
827287.016231399833585.642820488827302.813678806833583.758353615
827399.610485612833575.968392023827447.796734368833568.845233699
827501.541687441833556.152612274 827609.07848575833535.304366189
#Sta/Elev= 30
9814.488405.55949832.591401.14449842.624399.12699852.656397.57279882.753 391.937
9892.785389.16629902.818385.7068 9912.85383.19029932.956380.96329953.173 377.603
9963.282374.27259983.611 364.2589993.875361.8816   10001361.794910004.17 361.808
10014.45366.437510024.72371.382110034.96374.237810045.14 381.85710055.32389.7646
 10065.5395.387810075.68395.960410085.86396.218510096.04 397.41810106.21402.7132
10116.39 404.06410126.57 414.885 10129.3416.832110136.81421.490110140.99421.7379
#Mann= 3 , 0 , 0
9814.488  0.0618       09814.488  0.0618       010140.99  0.0618       0
#XS Ineff= 2 , 0
       0                               0
Bank Sta=9814.488,10140.99
Exp/Cntr=0.3,0.1

Type RM Length L Ch R = 1 ,36599.48,185.059600,185.059600,185.059600
XS GIS Cut Line= 6
827279.116217806833649.830430893827305.615630754833649.526042999
 827458.23176645833654.701703545827491.680606981833653.211877847
827579.334975937833646.351500007827610.280470644833642.281021554
#Sta/Elev= 30
9786.313397.46319802.198394.52329812.198391.9923 9832.21385.78289842.215383.0054
9852.221380.75599862.227379.73079872.233378.09879882.238377.1961 9902.25375.5216
9912.256377.48189922.261378.50989932.267382.16489942.273383.96679952.279380.1288
9972.293368.29169982.303363.55429992.313 361.09710002.34360.590610012.37361.0939
 10022.4366.049410032.43372.949810042.46384.201310052.49394.659610072.55409.1806
10082.58411.734110097.29 411.88110102.72412.469910112.81419.206210118.14419.8403
#Mann= 3 , 0 , 0
9786.313    0.12       09786.313    0.12       010118.14    0.12       0
#XS Ineff= 2 , 0
       09948.539                       0
Bank Sta=9786.313,10118.14
Exp/Cntr=0.3,0.1

Type RM Length L Ch R = 1 ,36414.42,92.529800,92.529800,92.529800
XS GIS Cut Line= 6
827261.912064062833789.614179983827302.229562912833793.660816124
827368.621170597833806.442485024827507.650026162833847.787682771
827562.795010743833851.743983455827586.931521407833849.428770093
#Sta/Elev= 30
9819.524408.43179822.628408.65959832.678408.84189842.728408.65199852.778407.9773
9873.049405.78219883.233404.38859893.416402.73779913.784 396.8129923.967395.6461
9934.333393.87269944.803389.17249955.272378.00159956.557376.92339965.742 369.297
9976.211363.0308 9986.68357.4816 9997.15356.355810007.64357.587410018.14361.2306
10028.65367.468910039.15375.836410049.55381.304510059.81385.272910070.06390.5312
10080.19394.682810130.36407.998610140.41411.476210150.45413.425110152.39413.5761
#Mann= 3 , 0 , 0
9819.524    0.04       09819.524    0.04       010152.39    0.04       0
#XS Ineff= 2 , 0
       0                               0
Bank Sta=9819.524,10152.39
Exp/Cntr=0.3,0.1

Type RM Length L Ch R = 1 ,36321.89,92.529800,92.529800,92.529800
XS GIS Cut Line= 6
827285.157109569833922.345757407827364.459408729833918.831716778
827460.107153508833918.414074338827494.995460624 833916.39492682
827538.264216917833909.581300942 827572.22656086833899.682179453
#Sta/Elev= 29
9862.799432.42659872.669430.77699882.678423.33039892.686419.35889902.694418.8336
9912.702418.1011 9922.71416.92149932.718412.35539942.726403.44519952.726394.7614
9962.726385.62279972.726376.66879982.727364.73219992.727357.926310002.73356.4146
10012.73356.818810022.73358.165910032.73363.079810042.74369.167710052.76374.7308
10062.77379.796510072.79385.957310082.91391.335610093.04  393.3110103.16393.6701
10116.59394.4136 10123.6 394.66610134.02394.491110151.96395.5783
#Mann= 3 , 0 , 0
9862.799    0.04       09862.799    0.04       010151.96    0.04       0
#XS Ineff= 2 , 0
       0                               0
Bank Sta=9862.799,10151.96
Exp/Cntr=0.3,0.1

Type RM Length L Ch R = 1 ,36229.36,92.529800,92.529800,92.529800
XS GIS Cut Line= 6
827319.336273909834056.560948487827437.613331942834009.572984014
827462.887389382833999.628056161827493.915172483833985.328668028
827525.573930269833967.740605761827580.627357544833931.308708168
#Sta/Elev= 30
9871.731428.21939877.826424.68059888.586423.29749899.346423.00629903.045421.5332
9910.106 418.3659920.866409.0653 9930.13400.38599942.387390.09889957.215379.3409
9963.907374.10039974.668364.77839984.301 358.2059985.428357.51669996.188356.3872
10006.92356.224110011.58358.396410017.68361.637810026.16 367.19410028.49368.5987
 10039.5376.597710050.51380.443410061.57 382.88610081.59 384.92210095.89  386.84
10101.51387.344410119.63392.773910137.75395.543910155.81395.565110162.56395.3388
#Mann= 3 , 0 , 0
9871.731    0.04       09871.731    0.04       010162.56    0.04       0
#XS Ineff= 2 , 0
       0                               0
Bank Sta=9871.731,10162.56
Exp/Cntr=0.3,0.1

Type RM Length L Ch R = 1 ,36136.83,92.529800,92.529800,92.529800
XS GIS Cut Line= 6
827400.084377718834201.432546494827428.868100122834170.587888404
827458.401935349834133.451264903 827537.09903842834014.188577751
827566.236841552833975.797087539827586.573432571833953.693931813
#Sta/Elev= 30
9847.419410.12549854.624410.15129869.896407.78329883.939408.07639889.608405.4237
9909.525397.20389915.526 392.5289922.301387.99469931.591379.86619935.078377.4076
9947.356373.54979948.601373.32159959.543369.54419966.096365.91079983.592 357.137
9995.868355.469510007.71354.935610019.59360.192710031.48365.039910039.05367.4261
10043.36368.445810055.24372.384210067.12380.109710079.01 383.09610093.04 383.112
10104.06383.788210116.61384.004410129.25387.396710142.84392.0109 10158.2393.6124
#Mann= 3 , 0 , 0
9847.419    0.04       09847.419    0.04       0 10158.2    0.04       0
#XS Ineff= 2 , 0
       0                               0
Bank Sta=9847.419,10158.2
Exp/Cntr=0.3,0.1