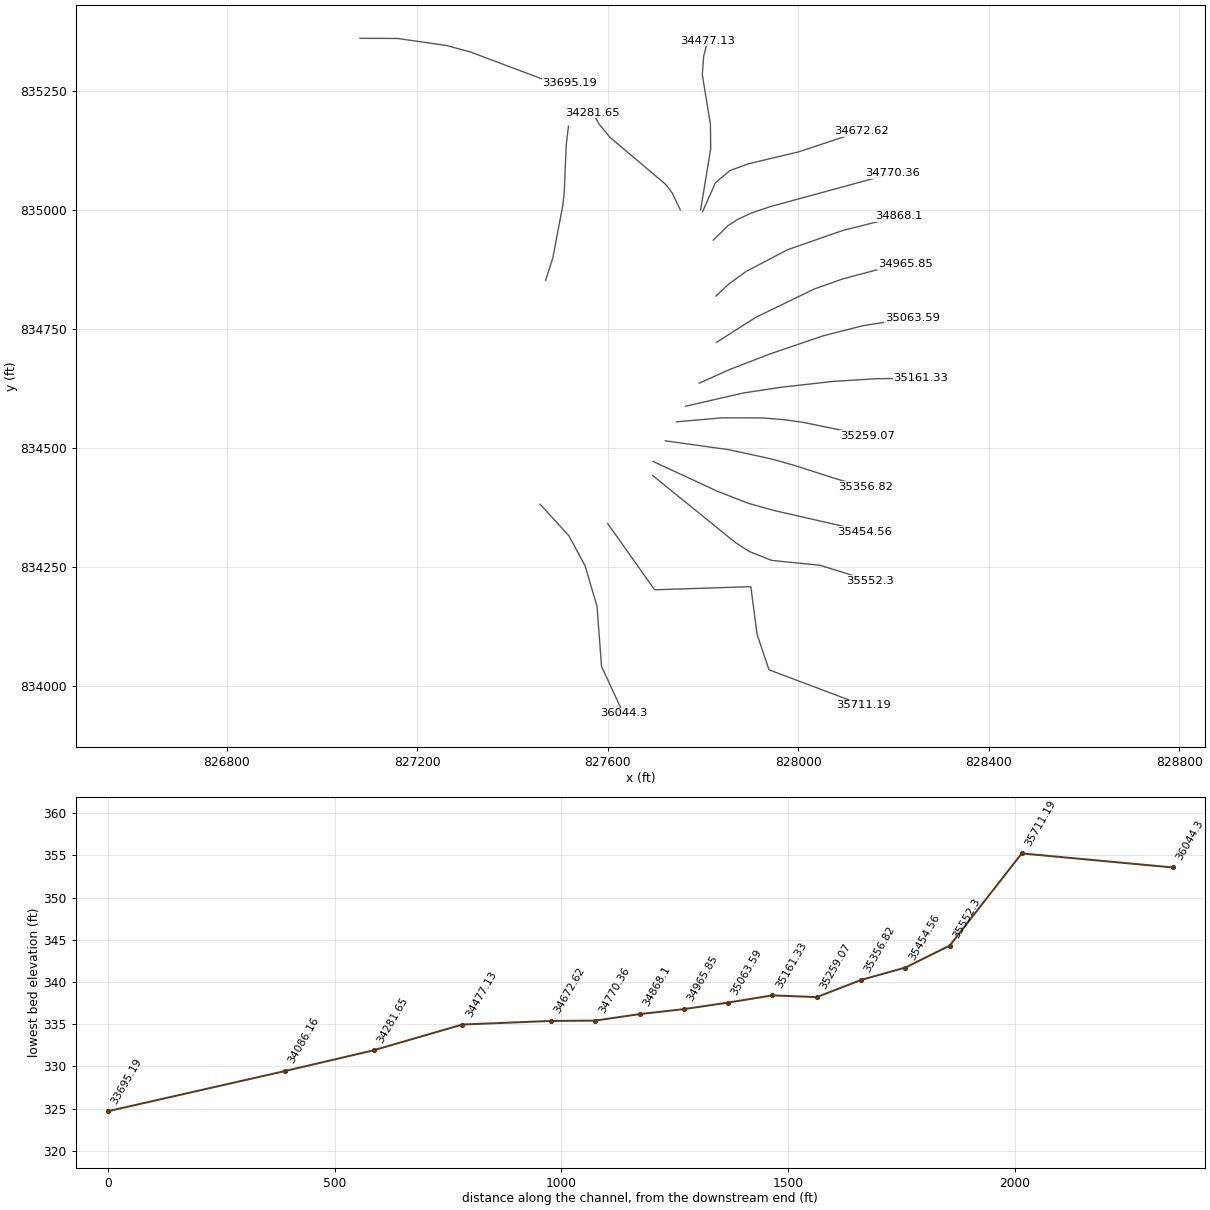
HEC-RAS study 18370_ras.prj: 18370

--- 18370_ras.g01 (geometry) --- (continued)

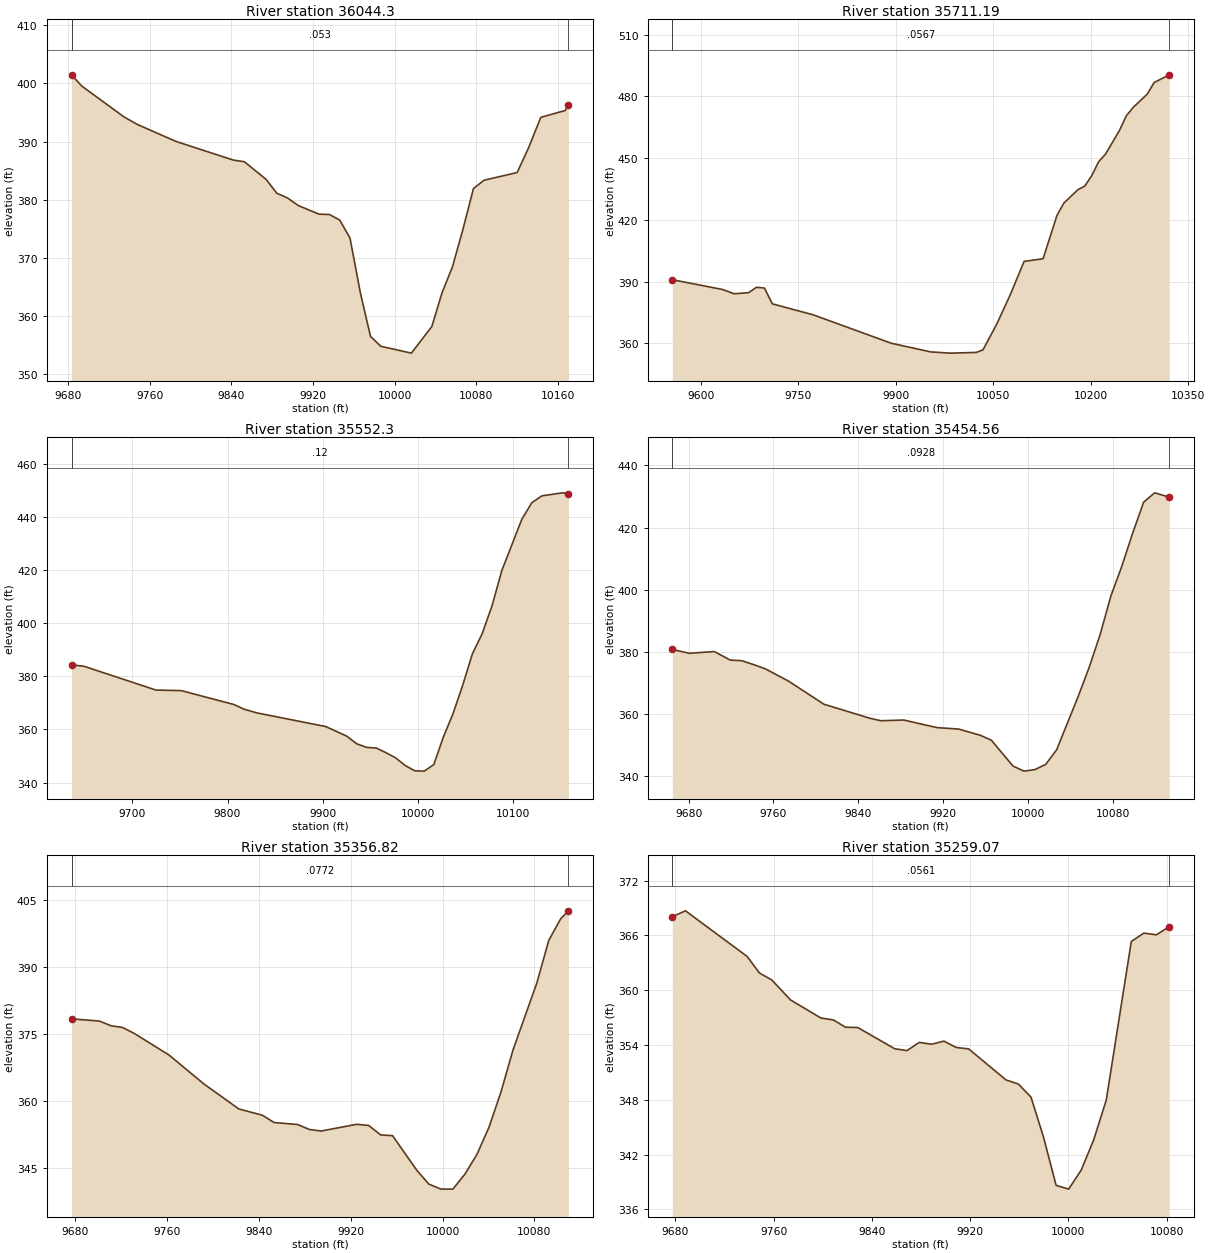
Type RM Length L Ch R = 1 , 36044.3,333.109300,333.109300,333.109300
XS GIS Cut Line= 6
827458.140576214834381.375640311827518.952652018834314.695068179
827552.538579693834251.889412862827577.525615193834167.170947909
827587.001474269834041.201779161827632.625946293833942.303847222
#Sta/Elev= 30
9683.469401.48039693.545399.5432 9735.14394.2039 9748.29392.90999785.925390.0081
9841.921386.8084 9852.73386.52239874.082383.48119884.524381.09869894.967380.2943
9905.373378.99519925.836377.49639936.037 377.4419946.132376.48619956.227373.3735
9966.256364.02729976.266356.46889986.277354.765410016.29353.578610036.35358.1574
10046.42364.011710056.49368.400310066.74374.847110077.11381.900410087.48 383.337
10119.89384.659710131.11 388.93510143.05394.159610166.94395.340510170.16396.2827
#Mann= 3 , 0 , 0
9683.469   0.053       09683.469   0.053       010170.16   0.053       0
#XS Ineff= 2 , 0
       0                               0
Bank Sta=9683.469,10170.16
Exp/Cntr=0.3,0.1

Type RM Length L Ch R = 1 ,35711.19,158.890700,158.890700,158.890700
XS GIS Cut Line= 6
827600.143473506834340.681875199827698.383991718834201.846101612
827900.548363775834208.341342479827913.538845509834108.477014095
827938.707903922834033.781744078828136.812750459833959.086474076
#Sta/Elev= 30
9555.832390.9245 9633.49386.15569650.802384.09779673.045384.61359685.427387.2678
9697.546 386.8799709.796379.20079772.574373.87449892.956360.0426 9953.54355.8458
9983.655355.245410023.81355.582510034.03356.833410055.13369.279210076.24383.7697
10097.34399.828810126.59401.128310147.96422.212910158.65428.207910180.03434.6338
10190.71436.4393 10201.4441.460810212.09448.252410222.78452.013410244.15463.4817
10254.84470.626510265.52474.7585 10286.9481.132410297.59486.7819 10320.9490.5159
#Mann= 3 , 0 , 0
9555.832  0.0567       09555.832  0.0567       0 10320.9  0.0567       0
#XS Ineff= 2 , 0
       0                               0
Bank Sta=9555.832,10320.9
Exp/Cntr=0.3,0.1

Type RM Length L Ch R = 1 , 35552.3,97.742500,97.742500,97.742500
XS GIS Cut Line= 6
827694.470548142834441.667045561827867.590788468834301.449413954
827896.714740145834282.450594032827944.109060959834263.565369174
828045.867707686834253.317432503828151.006565875834220.713870888
#Sta/Elev= 30
9636.249384.2766 9649.23383.7876 9724.89374.8076 9751.28374.61759806.258369.4281
9817.256367.63449830.429366.25589903.068361.08799925.045357.4884 9935.59354.5919
9945.999353.23929956.171 353.0059965.531351.37559976.346349.31589986.362346.4403
9996.378344.450710006.39344.3174 10016.4346.763810026.46357.126110036.56 365.891
10046.65376.491910056.92388.426310067.21396.022610077.49406.465110087.82419.7755
10108.82439.092210119.32445.316110129.86447.894210151.32449.026710157.76448.7316
#Mann= 3 , 0 , 0
9636.249    0.12       09636.249    0.12       010157.76    0.12       0
#XS Ineff= 2 , 0
       0                               0
Bank Sta=9636.249,10157.76
Exp/Cntr=0.3,0.1

Type RM Length L Ch R = 1 ,35454.56,97.742400,97.742400,97.742400
XS GIS Cut Line= 6
827695.314450055834471.363134369 827830.13731139834408.797488584
827895.690937813834383.224312195827949.766634667834368.194943813
828109.373902901834331.791477661828138.315502605 834323.66261977
#Sta/Elev= 30
9664.688380.81999680.621379.59619704.235380.15469719.356377.41299730.394377.2016
9741.433375.94899752.472374.59279774.549370.59739807.665363.2224  9851.3358.6912
9861.492357.9081 9882.96358.13999914.414355.6979 9934.88355.23099955.439353.2193
9965.688351.64429986.186343.32649996.434341.713710006.71342.194910016.97  343.88
10027.23348.525910047.75365.842610058.01375.080710068.27385.556210078.53398.0758
10088.79407.567710099.05418.228210109.38428.179510119.77431.1716 10133.6429.7792
#Mann= 3 , 0 , 0
9664.688  0.0928       09664.688  0.0928       0 10133.6  0.0928       0
#XS Ineff= 2 , 0
       0                               0
Bank Sta=9664.688,10133.6
Exp/Cntr=0.3,0.1

Type RM Length L Ch R = 1 ,35356.82,97.742500,97.742500,97.742500
XS GIS Cut Line= 6
827720.847934575 834514.64022678827855.399290437834495.845824475
827943.959189131834476.538018603827993.003900385834462.640994981
828083.117859826834433.761911272828141.571353954834417.539667461
#Sta/Elev= 30
9676.918 378.3539701.185  377.859711.296376.80199721.407 376.4069731.517375.0908
9761.849 370.2469792.181 363.7859822.632358.18449843.102356.78339853.337355.1486
9873.807354.70169884.042 353.5939894.276353.24499925.315354.75239935.709354.4909
9946.103352.3783 9956.52352.20799977.539344.50079988.049341.38239998.559340.2604
10009.06340.246110019.55 343.60710030.04 348.03410040.53 354.115   10051362.0307
10061.39 371.36810082.16386.355110092.54395.887410102.92 400.72510109.71402.5121
#Mann= 3 , 0 , 0
9676.918  0.0772       09676.918  0.0772       010109.71  0.0772       0
#XS Ineff= 2 , 0
       0                               0
Bank Sta=9676.918,10109.71
Exp/Cntr=0.3,0.1

Type RM Length L Ch R = 1 ,35259.07,97.742400,97.742400,97.742400
XS GIS Cut Line= 6
 827744.39090294834554.543562994827840.148449109 834562.89675287
827925.531669884834562.690884628827969.727366112834559.076808673
828010.936412152834553.291484477828145.321596862834525.671671809
#Sta/Elev= 30
9677.567368.04639688.259368.68419738.456363.69239748.486361.87739758.515361.1204
9773.708358.93569798.566356.94679808.569356.74589818.572355.94099828.575355.9051
9858.584353.58599868.616353.37749878.649354.27699888.682354.07449898.716354.4174
9908.783353.71989918.881353.56519949.222350.17329959.436349.70879969.649348.2774
9979.862343.88699990.076338.6287 10000.3338.210710010.51340.291310020.71343.6149
10030.92347.957910051.33365.329410061.53366.245110071.74366.056710082.27366.9482
#Mann= 3 , 0 , 0
9677.567  0.0561       09677.567  0.0561       010082.27  0.0561       0
#XS Ineff= 2 , 0
       0                               0
Bank Sta=9677.567,10082.27
Exp/Cntr=0.3,0.1

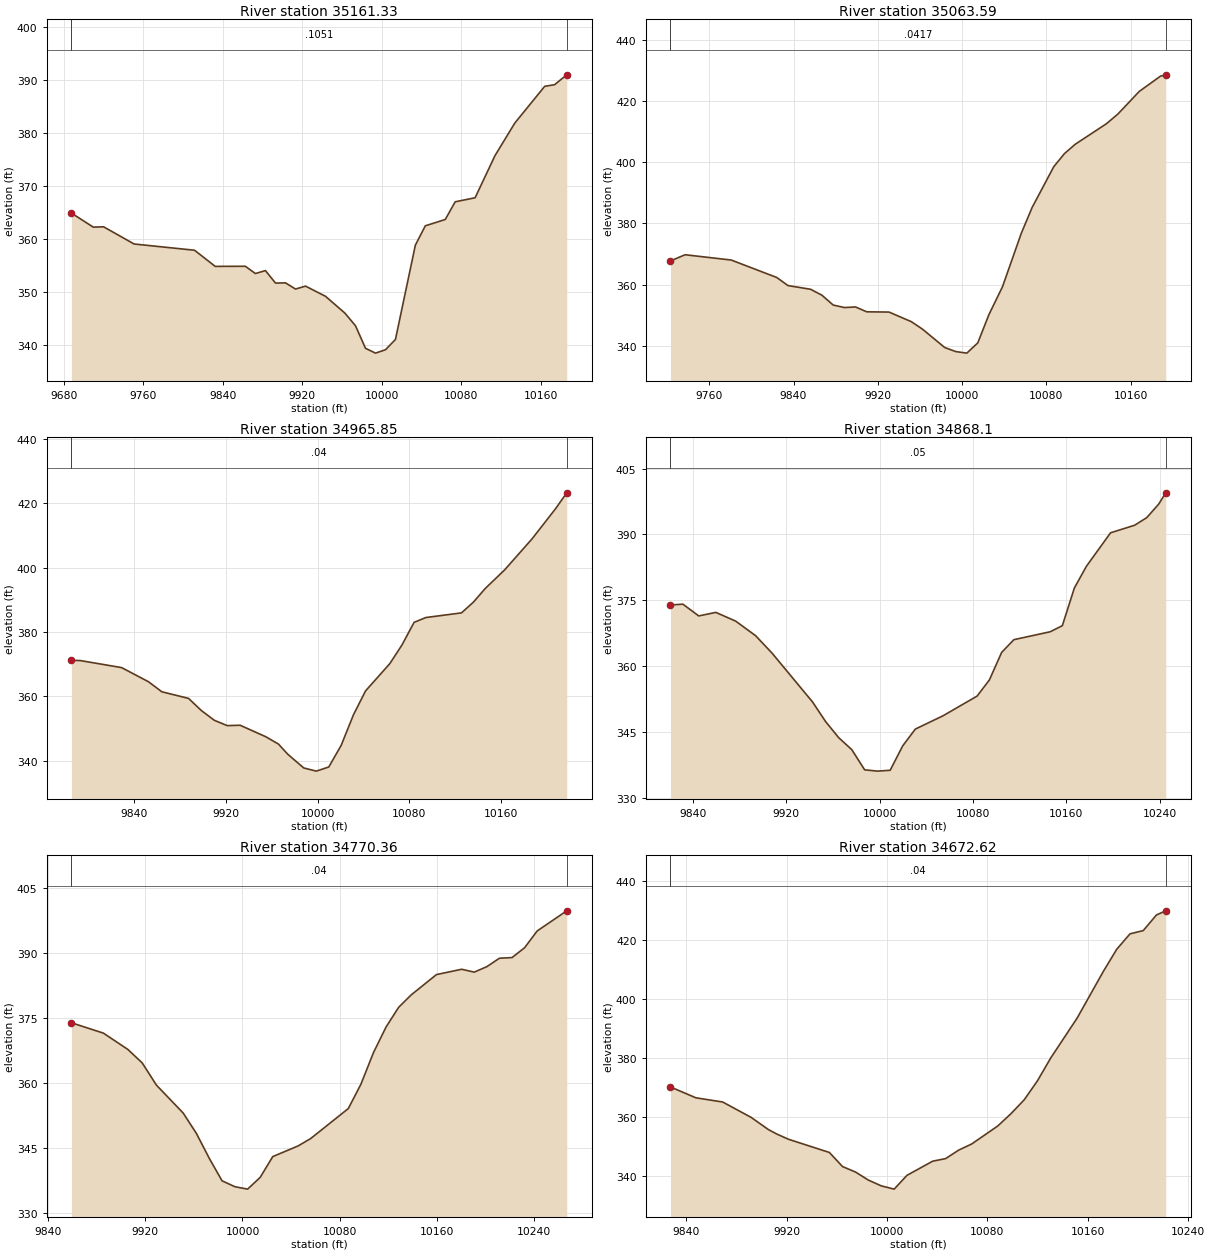
Type RM Length L Ch R = 1 ,35161.33,97.742500,97.742500,97.742500
XS GIS Cut Line= 6
827763.725408547834587.313911483 827885.44324176834615.214622627
827965.629754135834627.316419149828073.355913017834639.451306425
828166.030308712  834645.1555968828257.201895392834645.873062106
#Sta/Elev= 30
9687.882364.89519709.905362.24149720.256362.30649751.001 359.053 9811.76357.8747
9832.571354.82199862.911354.84059873.024 353.4679883.137354.02449893.251351.6623
9903.316351.70649913.378350.53399923.441351.09059943.565349.16279963.045 345.989
9973.752343.59059983.815339.33099993.877338.415910003.94339.057110013.96341.0028
   10034358.841510044.02362.495810064.06 363.68610074.08367.036110094.11367.7982
10114.12375.766710134.12381.939910164.12 388.86910174.12389.183910186.32391.0484
#Mann= 3 , 0 , 0
9687.882  0.1051       09687.882  0.1051       010186.32  0.1051       0
#XS Ineff= 2 , 0
       0                               0
Bank Sta=9687.882,10186.32
Exp/Cntr=0.3,0.1

Type RM Length L Ch R = 1 ,35063.59,97.742400,97.742400,97.742400
XS GIS Cut Line= 6
827792.322147737834635.782960961827857.131903268834664.824047427
827940.358897587834696.935735367828051.670676398834734.928713372
828136.570299228834756.563186817 828239.96746148834772.508685125
#Sta/Elev= 30
9723.151367.71829737.044369.75719780.876 368.0219824.041 362.3169834.759359.6639
9856.196358.45729866.915356.51689877.633353.2967 9888.29352.47789898.876352.6658
9909.461351.08079930.633350.99869951.804347.8557 9962.39 345.4079983.483339.3945
9993.985 338.07210004.47337.563110014.88340.9129 10025.3350.051310038.32  359.28
 10056.2376.806410066.48385.245510087.03398.5825 10097.2402.871710107.36405.9074
10137.01412.634810147.96415.830610168.12423.192910188.28428.200810193.29428.6322
#Mann= 3 , 0 , 0
9723.151  0.0417       09723.151  0.0417       010193.29  0.0417       0
#XS Ineff= 2 , 0
       0                               0
Bank Sta=9723.151,10193.29
Exp/Cntr=0.3,0.1

Type RM Length L Ch R = 1 ,34965.85,97.742500,97.742500,97.742500
XS GIS Cut Line= 6
827828.636461185834721.565943674827911.494292216834774.221348572
828034.321583191834833.680648201828093.079203022834854.463109862
828166.145723666834873.957337438828224.581908292834885.559054126
#Sta/Elev= 30
9785.167371.19839792.953371.12169828.935368.94319852.357364.56359864.068  361.43
9887.334359.3823  9898.6355.59449909.866352.57769921.132350.91729932.398351.0377
9954.823347.46149965.846345.19059974.009342.02269987.891337.77839998.914336.7872
10009.78338.078910020.62344.812110031.23354.228110041.84361.696710063.05370.1786
10073.66375.978510084.22382.993510094.57384.493210125.62  385.9410135.97389.2707
10146.32393.515410163.21399.272410187.27408.969210207.66418.275510217.43423.2204
#Mann= 3 , 0 , 0
9785.167    0.04       09785.167    0.04       010217.43    0.04       0
#XS Ineff= 2 , 0
       0                               0
Bank Sta=9785.167,10217.43
Exp/Cntr=0.3,0.1

Type RM Length L Ch R = 1 , 34868.1,97.742500,97.742500,97.742500
XS GIS Cut Line= 6
827827.175583153834818.714332546827855.239943854834844.612074479
827891.135704492834870.617530529 827977.51010163834915.769109646
828093.769419579 834956.44704449828210.947206432834985.744472082
#Sta/Elev= 30
9820.938 373.9699831.585374.15899845.192371.48119859.787372.28849876.832370.2969
9893.877366.9864 9907.95 363.0229942.565351.93819953.817347.45779965.069343.7847
9976.217341.07469987.234336.48789998.251336.196110009.07336.386210019.85341.9541
10030.63345.7565 10054.2348.757610083.52353.260310094.02356.918710104.53 363.191
10115.03366.086510146.16367.887910156.49369.268110166.81377.841210177.14382.7836
10197.79390.383610218.44392.108710228.76 393.82810238.97396.893910245.04399.4721
#Mann= 3 , 0 , 0
9820.938    0.05       09820.938    0.05       010245.04    0.05       0
#XS Ineff= 2 , 0
       0                               0
Bank Sta=9820.938,10245.04
Exp/Cntr=0.3,0.1

Type RM Length L Ch R = 1 ,34770.36,97.742400,97.742400,97.742400
XS GIS Cut Line= 6
827821.715131587834935.995254782 827853.22853208834967.013201212
827873.290100093834979.724170147827901.609527901834992.936545749
827941.880295696835006.546098566828198.594843369 835076.50748758
#Sta/Elev= 30
9859.142373.89619885.452371.50479905.587367.73879917.425364.61989929.126 359.486
9951.196353.01839962.071348.30969972.636342.5692  9983.2337.34679993.764335.9867
10004.24335.4259 10014.6338.141810024.97 342.94910045.71345.398210056.08347.0978
10087.19354.061210097.56359.683110107.93367.0083 10118.3372.932110128.67377.4796
10139.04380.358610159.78385.040910180.52386.271310190.89385.610810201.26 386.869
10211.63388.8219   10222 388.97410232.37391.248210242.74395.131610267.08399.7868
#Mann= 3 , 0 , 0
9859.142    0.04       09859.142    0.04       010267.08    0.04       0
#XS Ineff= 2 , 0
       0                               0
Bank Sta=9859.142,10267.08
Exp/Cntr=0.3,0.1

Type RM Length L Ch R = 1 ,34672.62,195.484900,195.484900,195.484900
XS GIS Cut Line= 6
827799.301549834834995.989162378827826.159032891835056.447991785
827856.334553547835082.007862927827896.057501948835096.494461549
828000.019821416 835121.17705722828132.022606523835164.822824653
#Sta/Elev= 30
9827.546370.09199847.786366.4114 9869.15364.97699891.746359.77789905.657355.5945
9912.198354.11119921.393352.34839954.147347.83799964.591343.05579975.023341.1759
9985.276338.43629995.507336.489110005.73335.386610015.95340.0723 10036.4344.8715
10046.75 345.75910057.11348.634210067.46350.713810088.26356.839110098.79361.0252
10109.33365.739610119.86372.172810130.39 379.90310151.45393.474810172.52409.4746
10183.05416.883710193.58422.101710204.12423.203810214.65428.517410222.05429.9207
#Mann= 3 , 0 , 0
9827.546    0.04       09827.546    0.04       010222.05    0.04       0
#XS Ineff= 2 , 0
       0                               0
Bank Sta=9827.546,10222.05
Exp/Cntr=0.3,0.1

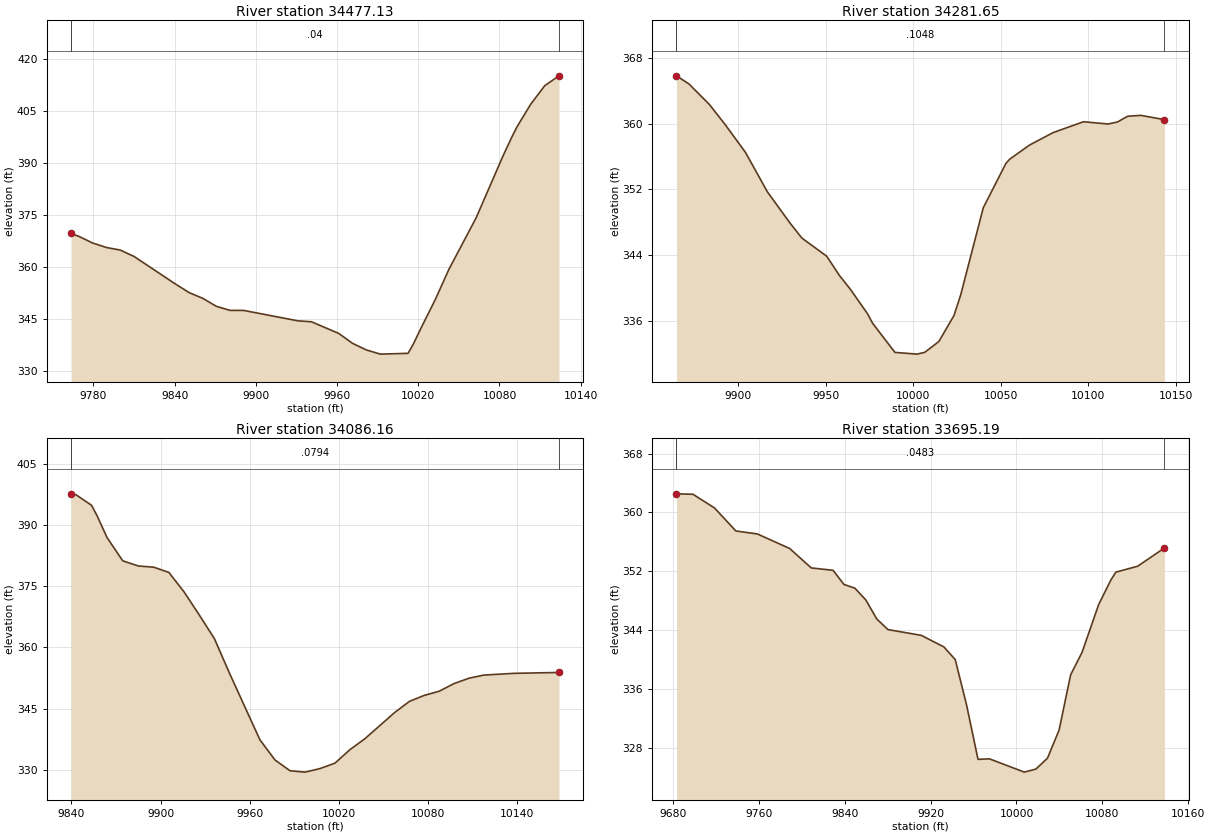
Type RM Length L Ch R = 1 ,34477.13,195.484900,195.484900,195.484900
XS GIS Cut Line= 6
  827795.0684727834999.296253894827816.242380955835127.863749541
827815.719228307835178.962578712827798.622726279835283.449113686
827801.379204645835321.532712098827809.882289767835355.063986422
#Sta/Elev= 30
9763.543369.73719769.359368.89749779.555366.97239789.751365.69329799.947364.9456
9810.143363.09429840.574355.18849850.712352.69949860.838 351.0369870.902348.7361
9880.967347.56969891.031 347.5589931.085344.55839941.102344.28759961.302340.9184
9971.465338.06319981.733336.15869992.001334.9588 10012.5335.188910016.31337.8299
 10022.6342.908210032.63 350.72410042.67359.417810062.73374.224310082.78392.2401
10089.33397.679310092.87400.434510103.08407.004910113.43412.340810123.96415.1788
#Mann= 3 , 0 , 0
9763.543    0.04       09763.543    0.04       010123.96    0.04       0
#XS Ineff= 2 , 0
       0                               0
Bank Sta=9763.543,10123.96
Exp/Cntr=0.3,0.1

Type RM Length L Ch R = 1 ,34281.65,195.484900,195.484900,195.484900
XS GIS Cut Line= 6
827752.350505729834999.607471286827735.822366863835034.469904425
827721.426496267835053.358732947827604.958168192835151.721068908
827581.601201546  835179.9117716827568.738383095835203.427527894
#Sta/Elev= 30
9864.799365.82019871.922364.83099883.618362.32579892.824359.81449904.166356.4958
9916.739351.67489929.562 347.8979936.367346.05899950.556343.84259957.754341.5181
9964.095 339.8089973.836336.84199976.809335.66499989.523332.120310002.14  331.91
10006.53332.126510014.61333.447210023.25336.619810027.09339.139910039.97349.7461
 10052.9355.151810055.04 355.663 10066.4357.388610079.89358.906110097.19360.2247
10111.23359.950610116.55360.1914 10122.4360.895510129.94361.002310143.39360.4815
#Mann= 3 , 0 , 0
9864.799  0.1048       09864.799  0.1048       010143.39  0.1048       0
#XS Ineff= 2 , 0
       0                               0
Bank Sta=9864.799,10143.39
Exp/Cntr=0.3,0.1

Type RM Length L Ch R = 1 ,34086.16,390.969900,390.969900,390.969900
XS GIS Cut Line= 6
827469.619470487834851.902376168 827484.77187547834898.855086025
827505.604928301835008.810484695827508.725252176835036.307910476
827512.813385064835135.717623299827517.591802414835175.276905583
#Sta/Elev= 30
9839.718397.57639842.973397.36699853.481394.77659857.237392.20159863.988386.8373
9874.496381.17939885.004379.91189895.328379.62069905.537378.33659915.745 373.568
9925.954367.93759936.163362.12499946.371353.61599966.789  337.369976.905332.4327
9987.016329.79149997.127329.449810007.23330.320510017.29331.655410027.36 334.951
10037.37337.617210057.39344.0263 10067.4346.775110077.41348.240210087.42  349.25
10097.42351.132810107.43352.434810117.44353.207910137.52353.628710168.01353.8488
#Mann= 3 , 0 , 0
9839.718  0.0794       09839.718  0.0794       010168.01  0.0794       0
#XS Ineff= 2 , 0
       0                               0
Bank Sta=9839.718,10168.01
Exp/Cntr=0.3,0.1

Type RM Length L Ch R = 1 ,33695.19,97.742400,97.742400,97.742400
XS GIS Cut Line= 6
827079.687665526835359.807025736827159.005911707835359.518001448
 827261.55989362835344.717422142827312.010523399835331.021216208
827470.415675161835271.471116293827519.727792077835266.194318253
#Sta/Elev= 30
 9683.22362.5208 9698.56362.46099718.562360.61219738.565357.46869758.568357.0668
9788.708355.08569808.815352.4472 9829.09352.12159839.261350.19729849.431349.6952
9859.602348.09719869.838345.5032  9880.2344.06539911.286343.2781 9932.33341.7086
9942.938339.98619953.546333.78269964.154326.41769974.826326.488410007.27 324.682
10018.07325.095410028.87 326.58110039.67330.391110050.47337.9171 10061.1340.9756
10076.54347.455310087.85350.784110092.56351.870610112.94352.681210137.82355.1579
#Mann= 3 , 0 , 0
 9683.22  0.0483       0 9683.22  0.0483       010137.82  0.0483       0
#XS Ineff= 2 , 0
       0                               0
Bank Sta=9683.22,10137.82
Exp/Cntr=0.3,0.1