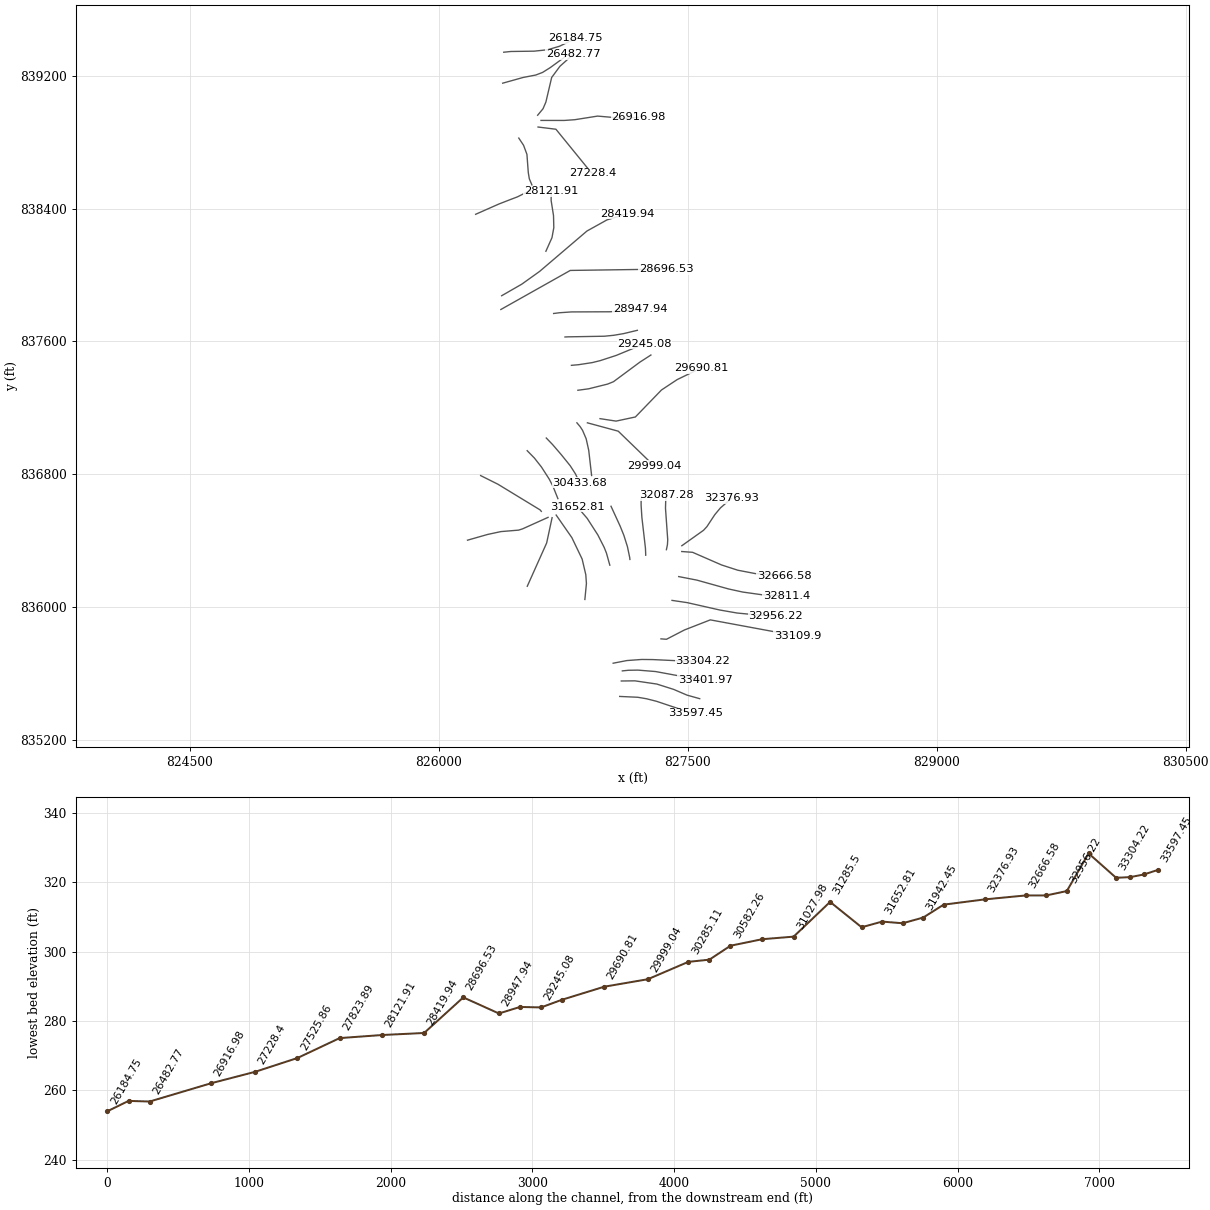
HEC-RAS study 18370_ras.prj: 18370

--- 18370_ras.g01 (geometry) --- (continued)

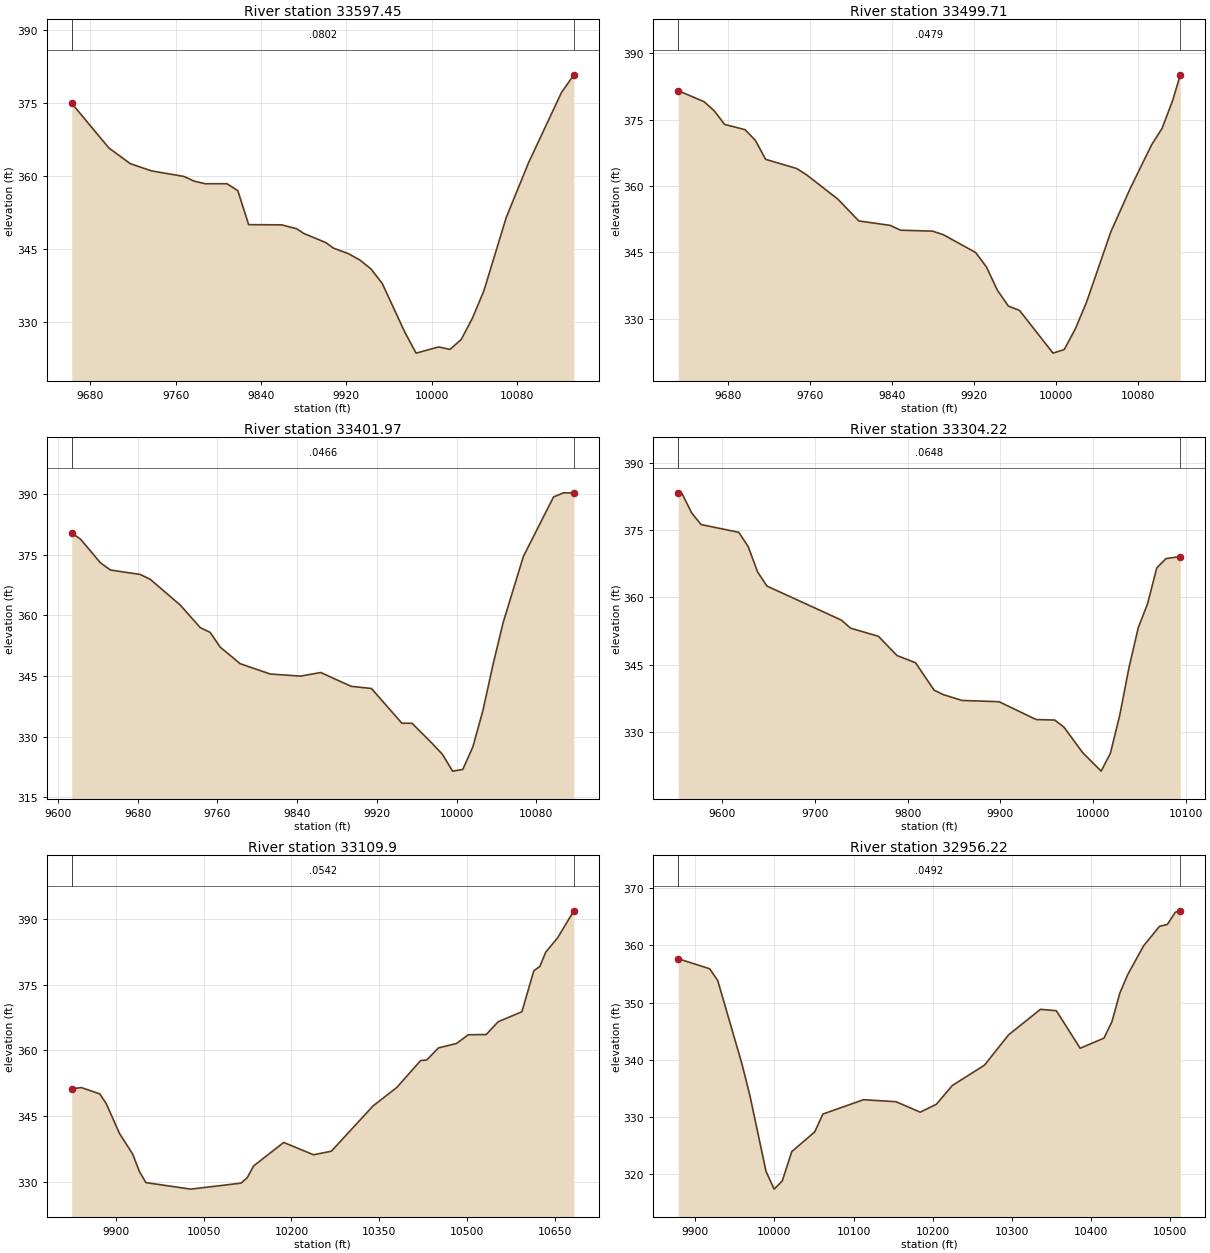
Type RM Length L Ch R = 1 ,33597.45,97.742500,97.742500,97.742500
XS GIS Cut Line= 6
827090.205916587835460.845982877827199.294439395835455.786204758
827251.335361128835446.947810377827312.167893833835431.567274418
827510.428145958835365.090537988827546.647249409 835358.75300034
#Sta/Elev= 30
9662.573 374.8799697.369365.70969717.413362.47969737.478360.98559767.575359.8561
9777.671358.85979787.814358.3485  9808.1358.34859818.243356.93499828.449349.9349
9859.393349.88879873.412349.09269880.023348.13619900.969346.22679907.827345.1124
9922.092343.95369932.654342.66369943.216340.81029953.777 337.803  9974.9327.8007
9985.462323.500910006.59324.775310017.19324.268210027.78326.310410038.37330.7525
10048.97336.293710070.01351.425610090.89 362.66710121.63377.055410133.36380.7542
#Mann= 3 , 0 , 0
9662.573  0.0802       09662.573  0.0802       010133.36  0.0802       0
#XS Ineff= 2 , 0
       0                               0
Bank Sta=9662.573,10133.36
Exp/Cntr=0.3,0.1

Type RM Length L Ch R = 1 ,33499.71,97.742400,97.742400,97.742400
XS GIS Cut Line= 6
827099.888603407835553.858459286827181.626685832 835554.83250703
827313.803075522835535.482895562827415.865274593835503.098787657
827495.889420826835468.720928883827572.407612579835447.326303871
#Sta/Elev= 30
9631.746 381.5269656.918379.05439666.923376.96179676.924373.91299696.926372.7149
9706.927370.29959716.946366.01089747.099363.9507 9757.15362.4626 9787.39357.0061
9807.757352.08969838.309351.08419848.516349.99779879.661349.78189890.043348.9911
 9921.61344.96039932.242341.66019942.873336.40419953.505332.84519964.377331.8674
9997.064322.205510007.95323.012210018.82 327.70110029.69333.704110053.33349.5792
10072.19359.377710093.12369.297910103.36373.029610113.61379.281610121.12385.1192
#Mann= 3 , 0 , 0
9631.746  0.0479       09631.746  0.0479       010121.12  0.0479       0
#XS Ineff= 2 , 0
       0                               0
Bank Sta=9631.746,10121.12
Exp/Cntr=0.3,0.1

Type RM Length L Ch R = 1 ,33401.97,97.742500,97.742500,97.742500
XS GIS Cut Line= 6
827106.230980293835614.783716027 827143.38848825835618.514529031
827200.649245071835619.401075554827306.544707804835610.803804761
827510.269378512835573.244505125827605.364625277835560.644251677
#Sta/Elev= 30
9613.713380.32249622.526378.83449642.626372.93659652.669371.18579682.672370.0899
9692.674368.85749722.693362.51069742.718356.94349752.731 355.7479762.771352.1077
9782.886348.00619813.057345.46179843.396344.94719863.657 345.8379894.216342.4212
9914.589341.87899945.148333.29859955.335333.28499975.707328.25689985.894325.5936
 9996.08321.440610006.26321.845110016.43327.436110026.59336.516410036.72347.8907
10046.84358.2086 10067.1374.535410097.39389.259710107.41390.2899 10117.8390.2441
#Mann= 3 , 0 , 0
9613.713  0.0466       09613.713  0.0466       0 10117.8  0.0466       0
#XS Ineff= 2 , 0
       0                               0
Bank Sta=9613.713,10117.8
Exp/Cntr=0.3,0.1

Type RM Length L Ch R = 1 ,33304.22,194.323900,194.323900,194.323900
XS GIS Cut Line= 6
 827050.93304717835661.049113219 827133.38447642835677.012169632
827223.020635919 835683.63437941827290.810248502835682.898129729
827461.950645235835674.755776678827590.384773059 835673.16649485
#Sta/Elev= 30
9552.457383.31429556.663383.11259566.938378.84059577.105376.23399617.774374.5088
9627.941371.30939638.091365.66419648.152362.52219728.359354.9394 9738.36353.1335
9768.361351.32799788.363347.03759808.379345.42689828.402339.31849838.413338.3085
9858.436337.02199898.481336.73459938.526 332.7579958.549332.64869968.557 331.045
9988.557325.400110008.56321.258210018.56 325.25110028.56333.654210038.56344.2927
10048.56353.213310058.56358.536310068.56366.577310078.57368.650210093.95369.1127
#Mann= 3 , 0 , 0
9552.457  0.0648       09552.457  0.0648       010093.95  0.0648       0
#XS Ineff= 2 , 0
       0                               0
Bank Sta=9552.457,10093.95
Exp/Cntr=0.3,0.1

Type RM Length L Ch R = 1 , 33109.9,153.676100,153.676100,153.676100
XS GIS Cut Line= 5
 827338.90882545835807.723871455827372.264979064835805.308105454
827480.549345165835861.397849053827636.354188472835922.161737934
828162.195534617835824.783710867
#Sta/Elev= 30
9824.791351.18619840.924351.50369872.576 350.0589883.838347.78339906.362 340.986
9928.886336.28929940.148332.3587 9951.41329.775810027.89328.286910113.76329.6505
 10124.5330.910610135.23333.569710186.72  338.9610237.57336.141410268.08336.9501
10339.27347.299910379.95351.540110420.63357.6862 10430.8357.782410451.14360.5709
10481.65 361.56210501.99363.5643 10532.5363.617910552.84366.528110593.52368.8326
10613.86378.199110624.03379.1684 10634.2382.450510654.54385.7294 10682.2391.8904
#Mann= 3 , 0 , 0
9824.791  0.0542       09824.791  0.0542       0 10682.2  0.0542       0
#XS Ineff= 2 , 0
       0                 10160.3       0
Bank Sta=9824.791,10682.2
Exp/Cntr=0.3,0.1

Type RM Length L Ch R = 1 ,32956.22,144.824300,144.824300,144.824300
XS GIS Cut Line= 6
827405.591167161836039.580875964827497.329805684836025.975459639
827693.575661391835981.546441287827798.400812716835963.326517061
827952.256050567835948.736030203828031.317081151835946.903743285
#Sta/Elev= 30
 9878.51357.65469918.276355.89929928.412353.84749958.822339.36849968.958 333.808
9989.403320.52449999.638317.430310009.89318.860310021.95323.990810050.92327.4224
10061.17330.534610112.46333.040310153.48332.694510184.13330.867910204.43332.2357
10224.73335.524510265.33339.077510295.65344.354610335.94348.819210356.06348.5806
10386.14342.022510416.22 343.79610426.24346.654210436.26 351.66810446.27354.9005
10466.28359.916510486.29363.307210496.29363.643410506.29365.769110512.61366.0164
#Mann= 3 , 0 , 0
 9878.51  0.0492       0 9878.51  0.0492       010512.61  0.0492       0
#XS Ineff= 2 , 0
       0                               0
Bank Sta=9878.51,10512.61
Exp/Cntr=0.3,0.1

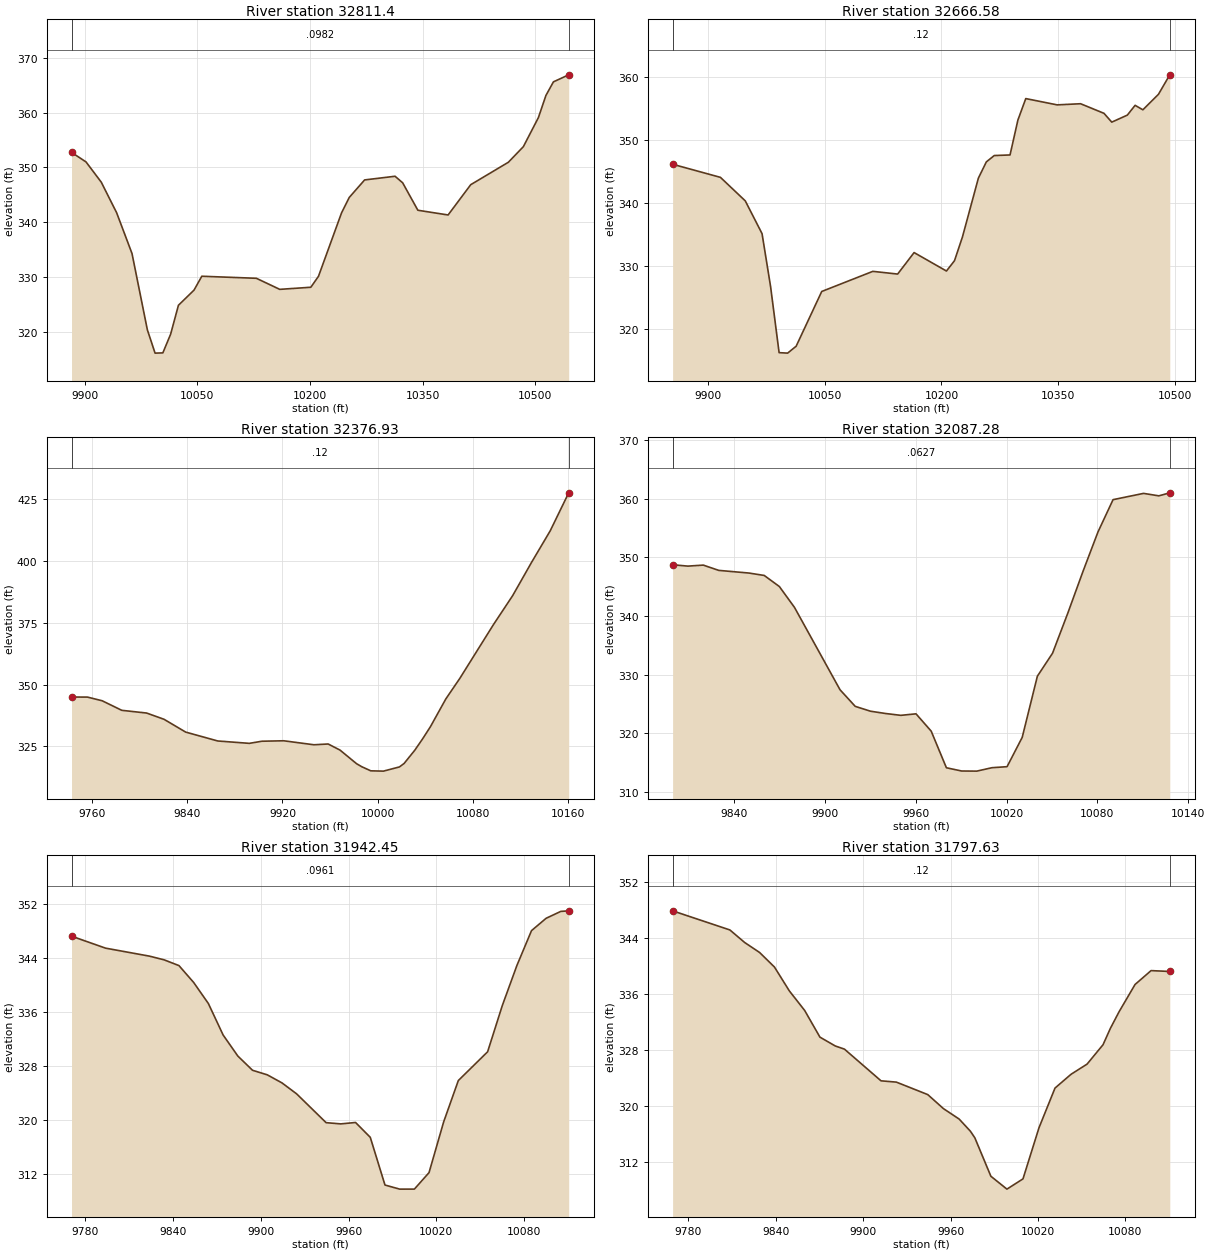
Type RM Length L Ch R = 1 , 32811.4,144.824300,144.824300,144.824300
XS GIS Cut Line= 6
827445.831065413836182.977806162827554.888629716836161.849687726
827745.784195285836108.550772355827831.245024313836089.849422744
827948.398680423836073.358472994828095.361646806836066.122357635
#Sta/Elev= 30
9882.324352.73769901.624351.00189921.929347.31699942.417 341.7479962.905334.3145
9983.394320.40129993.639316.1684   10004 316.21110014.38319.625110024.76324.8845
10045.53327.646410055.91330.1745 10128.6329.801110159.75327.785510201.15328.1693
10211.39330.1723 10242.1341.724710252.34344.526610272.81347.719310313.39348.3892
10323.52 347.19410343.77342.196510384.05341.335710414.19346.851910464.32350.9382
10484.34353.784310504.36359.078210514.37363.105210524.37365.585810544.73366.8666
#Mann= 3 , 0 , 0
9882.324  0.0982       09882.324  0.0982       010544.73  0.0982       0
#XS Ineff= 2 , 0
       0                               0
Bank Sta=9882.324,10544.73
Exp/Cntr=0.3,0.1

Type RM Length L Ch R = 1 ,32666.58,289.648700,289.648700,289.648700
XS GIS Cut Line= 6
827464.228321311836334.000125089827529.353220983836329.321309337
827704.610308995836252.894311406  827802.2713776 836221.29113739
827908.982044921836200.791850497828079.626319535836189.125680725
#Sta/Elev= 30
9854.006346.16389915.544344.08099947.533 340.3459969.127 335.1389980.097326.7459
9991.067316.243810002.05316.169110013.01317.267110045.92 325.95810111.71 329.154
10143.61328.7237 10164.8332.136110206.43329.207610216.79330.844910227.04334.6236
10247.54343.960510257.79346.538110267.98347.544910288.26347.636710298.39353.1833
10308.53356.589110348.87355.589910379.04355.771510409.16354.249510419.17352.8489
10439.21353.962910449.23355.517210459.23354.810410479.23357.260710493.86360.3617
#Mann= 3 , 0 , 0
9854.006    0.12       09854.006    0.12       010493.86    0.12       0
#XS Ineff= 2 , 0
       0                               0
Bank Sta=9854.006,10493.86
Exp/Cntr=0.3,0.1

Type RM Length L Ch R = 1 ,32376.93,289.648600,289.648600,289.648600
XS GIS Cut Line= 6
827464.720486878836368.943879888827595.612116742836462.086030197
 827616.07637585836484.365661352827663.176369466836555.876904605
827697.507107339836597.039285713827763.724190463836654.179525274
#Sta/Elev= 30
9742.701344.9609 9756.07344.94319768.464 343.4579784.949339.59249805.789338.4966
9820.417335.98089838.642 330.7999865.596327.20799892.137326.24799902.725327.1059
9921.042327.28959946.458325.6744  9958.4325.98849968.381323.52459982.283318.0251
9986.676316.80149994.225315.148510004.88315.026310018.33316.725710022.24 318.127
10031.27323.511710037.85 328.11710044.29332.919210057.31344.202710069.08352.5094
 10097.3374.203710113.52 385.96510129.11399.174410145.02412.100610160.58427.4732
#Mann= 3 , 0 , 0
9742.701    0.12       09742.701    0.12       010160.58    0.12       0
#XS Ineff= 2 , 0
       0                               0
Bank Sta=9742.701,10160.58
Exp/Cntr=0.3,0.1

Type RM Length L Ch R = 1 ,32087.28,144.824300,144.824300,144.824300
XS GIS Cut Line= 6
827371.782234708836345.143028537827377.932314118836375.016361729
827379.736112806836404.330847376827366.235694309836594.713181779
827367.571672388836641.198676049827372.179815179836672.142508895
#Sta/Elev= 30
9799.235348.75739809.299348.52449819.508348.69619829.718 347.7979849.756347.3388
9859.774346.93069869.776 345.0439879.779341.4786 9909.89327.40539919.932 324.572
9929.973 323.7479940.015323.35099950.057323.03789960.099323.29819970.141 320.337
9980.182314.08749990.224313.533510000.26313.511910010.27314.094410020.28314.2719
10030.29319.275410040.31329.727110050.32333.641810060.32340.424810070.33 347.535
10080.33354.337910090.33359.874610110.49 360.946 10120.6360.525210127.82361.0411
#Mann= 3 , 0 , 0
9799.235  0.0627       09799.235  0.0627       010127.82  0.0627       0
#XS Ineff= 2 , 0
       0                               0
Bank Sta=9799.235,10127.82
Exp/Cntr=0.3,0.1

Type RM Length L Ch R = 1 ,31942.45,144.824400,144.824400,144.824400
XS GIS Cut Line= 6
827246.878271065836311.746246811827247.076275039836314.997506538
827245.467001649836354.063256936827223.847775537836541.293768853
827219.414132002836612.659979648827219.359524697836650.445800993
#Sta/Elev= 30
9770.454347.2181 9793.73345.4432 9823.82344.25959833.887343.70739843.953342.8613
 9854.02340.36319864.087337.24549874.154332.59779884.221329.48129894.288327.3716
9904.354326.70099914.421325.50699924.488323.87629944.622319.62149954.689319.4409
9964.756319.64939974.822317.45499984.889310.39469994.956309.7881   10005309.7915
10015.02312.228610025.04319.744510035.06325.8527 10055.1330.110910065.11336.9255
10075.13342.877610085.13348.035710095.13349.862410105.13350.879210110.57350.9659
#Mann= 3 , 0 , 0
9770.454  0.0961       09770.454  0.0961       010110.57  0.0961       0
#XS Ineff= 2 , 0
       0                               0
Bank Sta=9770.454,10110.57
Exp/Cntr=0.3,0.1

Type RM Length L Ch R = 1 ,31797.63,144.824300,144.824300,144.824300
XS GIS Cut Line= 6
827151.775201983836286.317618711827150.797813465836296.561053978
827136.865228122836363.544748579827115.054943728836432.498668085
 827093.30358676 836486.36444663827038.020630221836606.692315258
#Sta/Elev= 30
9769.085347.94219808.423345.20899818.637343.40619828.851341.98379839.065339.9011
9849.319336.48089859.807333.69629870.295329.88079880.784 328.6229887.136 328.165
9912.249323.63539922.811323.4474 9944.38321.66249955.165319.65469965.949318.1617
9973.674 316.4259976.734315.47569987.729309.98829998.757308.147110009.78309.6119
10020.78316.922310031.78322.597710042.78 324.56610053.78326.019110064.77328.7936
10069.83331.137310075.77333.503110086.77337.410510097.77339.393410110.63339.2693
#Mann= 3 , 0 , 0
9769.085    0.12       09769.085    0.12       010110.63    0.12       0
#XS Ineff= 2 , 0
       0                               0
Bank Sta=9769.085,10110.63
Exp/Cntr=0.3,0.1

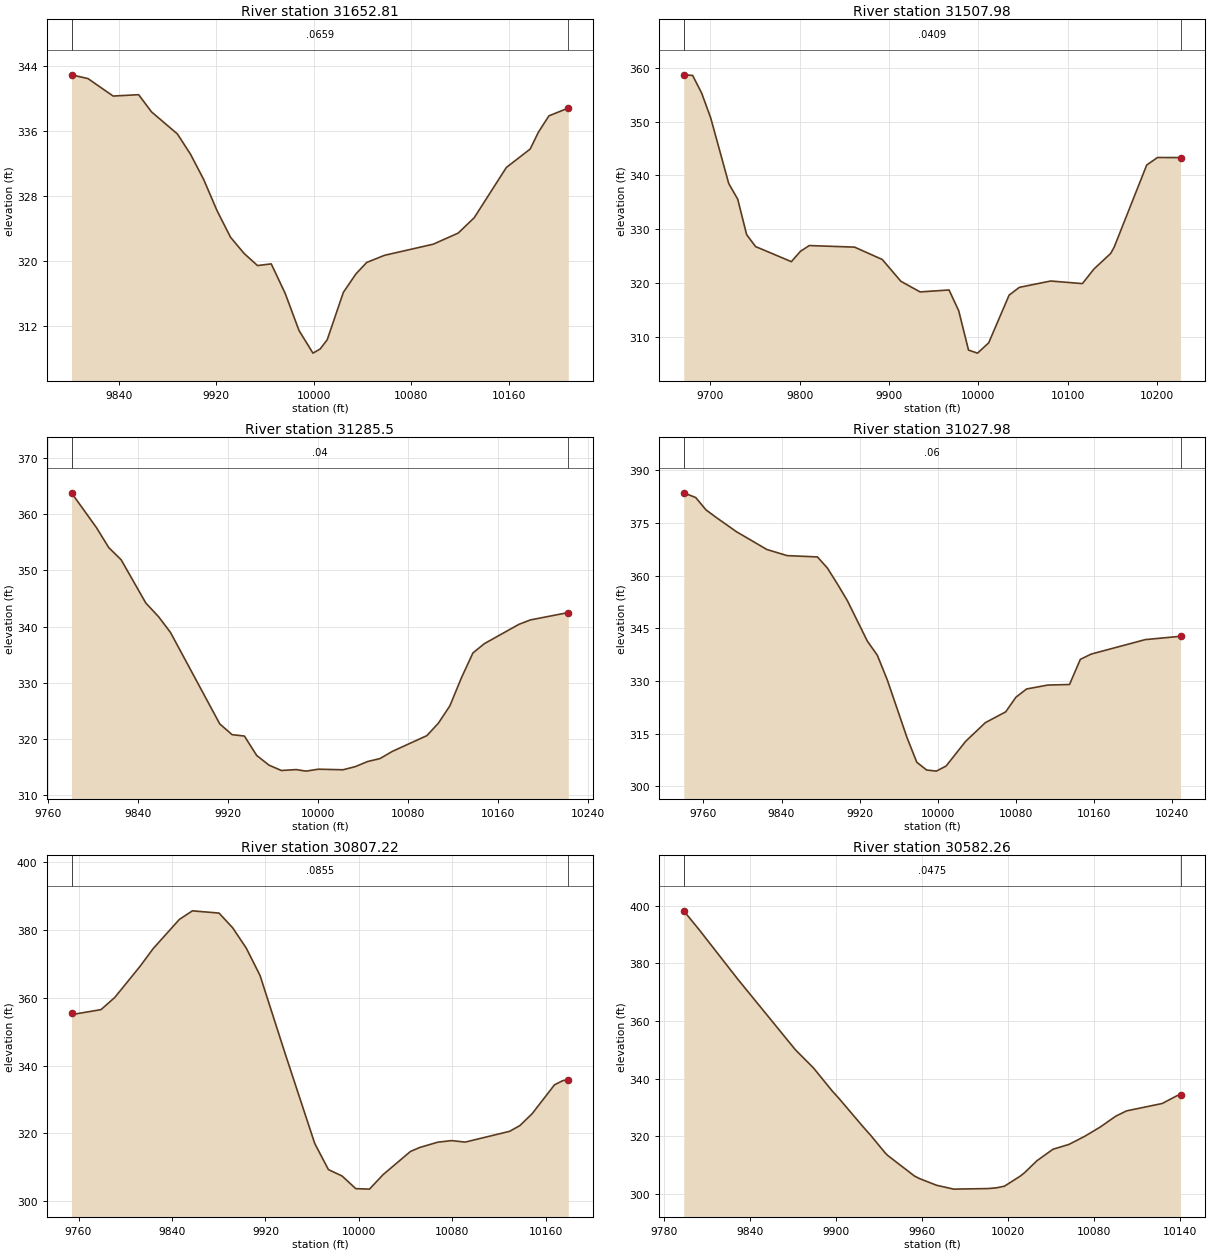
Type RM Length L Ch R = 1 ,31652.81,144.824300,144.824300,144.824300
XS GIS Cut Line= 6
827030.750674367 836251.77427119827010.485076874836324.448525637
826996.726208538836359.031569585826958.787128896836433.714660197
826894.605532706836533.531220406826834.660200357836603.621954724
#Sta/Elev= 30
9801.364342.90289814.887342.44019835.508340.28859856.459340.45759866.967338.3418
9888.252335.61739899.014333.11369909.777330.01369920.723326.17719931.793322.9024
9942.863320.91299953.933319.41139965.193 319.6189976.589316.00149987.985311.4102
9999.408308.626210005.24309.128410011.13310.282410024.34316.1086 10034.6318.3724
10043.45319.790110058.08320.673310098.08322.042510118.55323.412210131.71325.3094
10158.03331.492610177.55333.759110184.34335.842110192.94  337.8510208.85338.8111
#Mann= 3 , 0 , 0
9801.364  0.0659       09801.364  0.0659       010208.85  0.0659       0
#XS Ineff= 2 , 0
       0                               0
Bank Sta=9801.364,10208.85
Exp/Cntr=0.3,0.1

Type RM Length L Ch R = 1 ,31507.98,222.482300,222.482300,222.482300
XS GIS Cut Line= 6
826880.493779441836045.173645814826889.792280422836141.393485636
826886.037804966836194.438328515826863.983702176836288.624815494
826802.042350461 836417.69550489826707.534673785836553.653462353
#Sta/Elev= 30
9670.101358.67229680.033358.56119690.141355.27239700.249 350.6819720.464338.4825
9730.493335.5793  9740.5328.99479750.507326.77859790.577323.97879800.602 325.883
9810.627326.96969861.346326.67579892.333324.37989913.168320.3304 9934.65318.3597
9967.089318.71669977.901314.87019988.885 307.553    9999 306.99210011.47308.9035
10034.36317.7654 10045.8 319.20610080.83320.382710116.37319.9046 10129.4322.6295
10148.04325.502810151.92326.661210188.39341.923210200.44343.319710226.29 343.306
#Mann= 3 , 0 , 0
9670.101  0.0409       09670.101  0.0409       010226.29  0.0409       0
#XS Ineff= 2 , 0
       09940.921                       0
Bank Sta=9670.101,10226.29
Exp/Cntr=0.3,0.1

Type RM Length L Ch R = 1 , 31285.5,257.517700,257.517700,257.517700
XS GIS Cut Line= 3
826533.344929218836124.730292067826650.198561698836385.547599763
826682.917578787836537.924736515
#Sta/Elev= 30
9781.192 363.7969803.403357.59899814.361354.04679825.319351.89189847.234344.2057
9858.613341.7597 9869.15338.97739912.981322.70399923.939 320.7869934.897320.5397
9945.854317.08059956.812315.3597 9967.77314.41239980.902314.57549989.686314.3004
10000.64314.644210022.56314.541410033.52315.103710044.47316.009210055.43316.5345
10066.39317.810310097.11320.613110107.34322.832110117.57325.9158 10127.8330.8863
10138.03335.317210148.25336.978310178.94 340.40510189.17341.192810222.84342.5041
#Mann= 3 , 0 , 0
9781.192    0.04       09781.192    0.04       010222.84    0.04       0
#XS Ineff= 2 , 0
       09949.928                       0
Bank Sta=9781.192,10222.84
Exp/Cntr=0.3,0.1

Type RM Length L Ch R = 1 ,31027.98,220.761100,220.761100,220.761100
XS GIS Cut Line= 6
826173.189313106836402.303631509826294.716389855836436.967795432
826374.492016313836454.106244003826480.962181246836462.953938331
 826504.81626148836470.505755671826658.677376466836539.839806582
#Sta/Elev= 30
9739.886383.55189752.168382.20329762.566378.71919772.965 376.5729793.763372.4951
 9824.96367.41999845.757365.66539876.778365.29669887.006 362.1359897.235357.5974
9907.463352.84059927.919341.32569938.147337.29279948.367330.26849968.497313.8805
9978.561306.82779988.565304.61639998.567304.285610008.57305.730610028.58312.7619
10048.83318.097110069.62321.165510080.12325.338610091.02327.678810112.84328.8001
   10135328.958310146.12336.125210157.24337.625910212.59341.743810248.77342.6921
#Mann= 3 , 0 , 0
9739.886    0.06       09739.886    0.06       010248.77    0.06       0
#XS Ineff= 2 , 0
       0                               0
Bank Sta=9739.886,10248.77
Exp/Cntr=0.3,0.1

Type RM Length L Ch R = 1 ,30807.22,224.962900,224.962900,224.962900
XS GIS Cut Line= 4
826252.438721478836791.572710633826356.605388165836739.489377305
826610.754065752836584.744812697 826617.88544035836575.972645804
#Sta/Elev= 30
9753.963355.53449756.827355.22099779.187356.52169791.021360.12469812.728369.3403
9823.909374.54899846.269383.1405 9857.45385.68729880.253385.02099891.961380.6715
9903.669374.62549915.376366.61049936.743343.67859962.208317.01399973.916 309.317
9985.623307.42029997.331 303.69510009.04303.551210020.75307.835310044.16 314.674
10052.11315.844910067.58317.408710079.29317.868910090.99317.432110129.03320.6092
10137.82  322.3110148.26325.788110167.49 334.34910174.71335.592410179.28335.8252
#Mann= 3 , 0 , 0
9753.963  0.0855       09753.963  0.0855       010179.28  0.0855       0
#XS Ineff= 2 , 0
       0                               0
Bank Sta=9753.963,10179.28
Exp/Cntr=0.3,0.1

Type RM Length L Ch R = 1 ,30582.26,148.574700,148.574700,148.574700
XS GIS Cut Line= 6
826532.870804195836941.668869507826576.576937641836896.970654852
826618.639258674836843.490641939826665.846892474836769.987976327
826688.297165651836726.831989781826717.885506491836652.813425888
#Sta/Elev= 30
9793.729398.2057 9805.02391.30779831.399374.49239871.502350.04269884.224343.6717
9896.947335.88559902.249332.94929918.425323.48499924.312320.16729934.393314.0857
9936.109 313.2719954.656306.18089958.141305.30799970.014     3039981.888301.6661
 10005.7301.857610011.67302.111310017.29302.680410028.56306.2477 10031.5307.4448
10039.84  311.4710051.11315.488610062.31317.1843 10073.2319.970410084.09323.2011
10094.99326.998410102.48328.814310127.28331.3693 10137.8334.1195 10140.1 334.466
#Mann= 3 , 0 , 0
9793.729  0.0475       09793.729  0.0475       0 10140.1  0.0475       0
#XS Ineff= 2 , 0
       0                               0
Bank Sta=9793.729,10140.1
Exp/Cntr=0.3,0.1

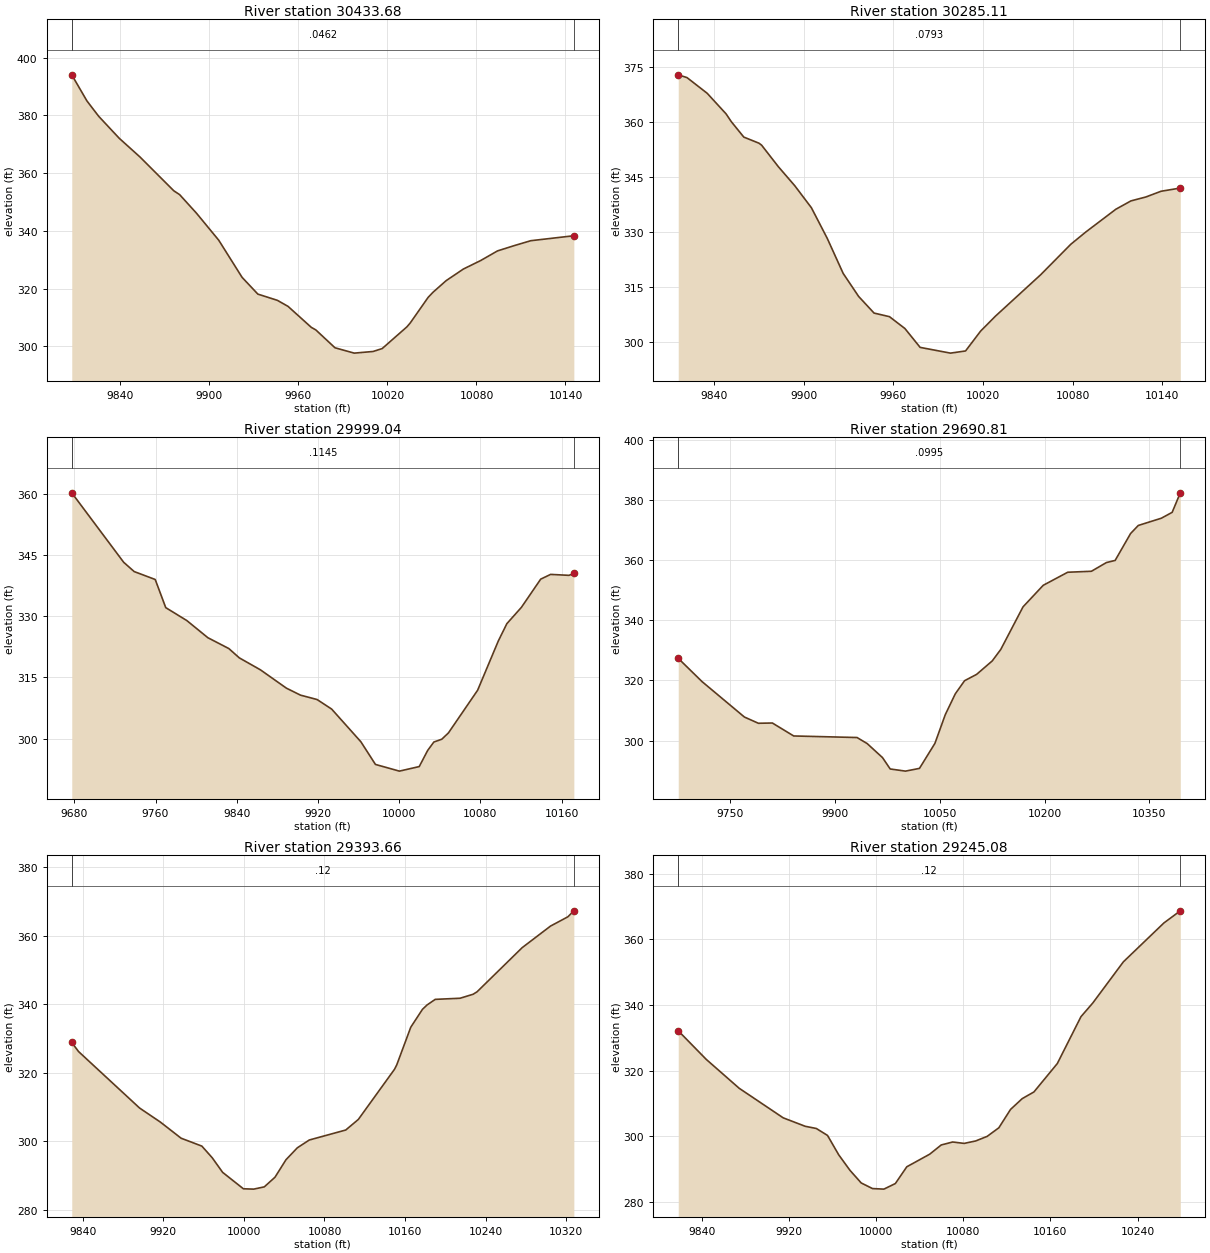
Type RM Length L Ch R = 1 ,30433.68,148.574700,148.574700,148.574700
XS GIS Cut Line= 6
826647.887593414837018.057020271826685.915353671 836978.57015759
826737.795686692836918.176276819826792.491681458836850.481821672
826824.377008958836800.669041787826848.075986815836748.034104498
#Sta/Elev= 30
9807.202394.03439817.455384.96989825.329379.68839839.212372.05349853.096365.6212
9875.964353.88239879.912352.5402 9891.31346.08849906.278336.75019922.003323.8972
9932.644318.08749945.756315.94269952.969313.84629968.694306.56129971.671 305.706
9984.629299.50169997.586297.649410010.31298.219210016.45299.232410033.11306.7492
10035.33308.083310047.47316.994810050.76318.7589 10059.6322.769310071.23326.7875
10082.83329.716510094.19333.054910105.37334.869410116.61336.586710145.63338.3013
#Mann= 3 , 0 , 0
9807.202  0.0462       09807.202  0.0462       010145.63  0.0462       0
#XS Ineff= 2 , 0
       0                               0
Bank Sta=9807.202,10145.63
Exp/Cntr=0.3,0.1

Type RM Length L Ch R = 1 ,30285.11,286.072400,286.072400,286.072400
XS GIS Cut Line= 6
826832.495593913837109.481934829826852.282428092837086.191421514
826866.627142123837063.979681296826888.162762569 837013.62734005
826903.609623944836944.293461605 826921.05820649836792.207553245
#Sta/Elev= 30
9816.082372.82019821.963372.06169835.395367.81619848.061362.20729851.652360.0321
9859.965355.86319870.084354.20639871.869 353.668 9883.05347.81659894.148342.5767
 9905.21336.61519915.836 328.2589926.462318.7354 9936.82312.45669947.135307.9285
 9957.45306.94599967.765303.72649977.976298.58189998.283297.017110008.38297.6105
10018.47303.024510028.53307.144410058.69318.3863 10078.8326.663810088.85330.0088
10108.96336.208510119.04338.474410129.12339.5593 10139.2341.1035 10152.1341.9817
#Mann= 3 , 0 , 0
9816.082  0.0793       09816.082  0.0793       0 10152.1  0.0793       0
#XS Ineff= 2 , 0
       0                               0
Bank Sta=9816.082,10152.1
Exp/Cntr=0.3,0.1

Type RM Length L Ch R = 1 ,29999.04,308.226300,308.226300,308.226300
XS GIS Cut Line= 3
826895.668731242837109.516100183827081.432620168837059.168877974
827298.446509063836849.099433526
#Sta/Elev= 30
9677.496 360.2599728.607343.22919738.968340.9488 9759.69339.00459770.051332.1059
9790.772328.94139811.494324.73519832.215322.06179842.576319.77219863.298316.8535
9888.845 312.3639902.763310.6431 9919.09309.56959933.467307.22259962.223299.2148
9976.601293.647910000.19292.006710019.73 293.12510028.02297.075110034.11299.1421
10041.94299.832410048.49301.381810077.25311.852810097.61323.9249   10106328.1617
10120.38332.183110139.36339.091910149.13340.2551 10167.2340.0223   10172340.4954
#Mann= 3 , 0 , 0
9677.496  0.1145       09677.496  0.1145       0   10172  0.1145       0
#XS Ineff= 2 , 0
       0                               0
Bank Sta=9677.496,10172
Exp/Cntr=0.3,0.1

Type RM Length L Ch R = 1 ,29690.81,297.149400,297.149400,297.149400
XS GIS Cut Line= 6
 826971.70246792837134.695616555827068.297466218837119.871012972
827184.801926681837144.758913374827342.217288087 837307.50010057
827436.909512572837370.157843328827579.815769166837439.505812354
#Sta/Elev= 30
 9675.81327.36699709.902319.62029770.482307.84319790.516305.76489810.552305.8488
9841.025301.5416 9931.71 301.0219946.191299.00919968.114294.35229979.139 290.561
   10001289.844610021.03 290.75910043.14 299.07810057.98308.634110072.31315.5608
 10085.6319.925810102.79322.028210125.18326.503810137.46330.352410169.22344.4827
10198.11351.654610233.16 356.00210267.12356.3284 10288.5359.217510301.07359.9368
10323.12368.868510334.15 371.56110367.23373.979310382.66375.932410394.31  382.42
#Mann= 3 , 0 , 0
 9675.81  0.0995       0 9675.81  0.0995       010394.31  0.0995       0
#XS Ineff= 2 , 0
       0                               0
Bank Sta=9675.81,10394.31
Exp/Cntr=0.3,0.1

Type RM Length L Ch R = 1 ,29393.66,148.574600,148.574600,148.574600
XS GIS Cut Line= 6
826838.324790446837305.719470905826903.586985946837314.568406616
827016.901246496837342.831961747827052.466257733837357.034605186
827212.116061645837475.329697959827278.296626559837518.063238584
#Sta/Elev= 30
9828.972328.8962 9835.67326.25849896.339309.76179916.957305.67079937.574300.9549
9958.191298.65029968.499295.24019978.808290.99519999.422286.197410009.71286.0958
10020.23286.7597 10030.8289.561910041.79294.689310053.03298.154910064.91300.4343
 10101.1303.3446 10113.6306.428310149.54321.067510151.81322.386710165.69333.3434
10177.28338.557610181.84339.831910190.01341.475110214.67341.801810227.59342.9658
10231.49343.670210276.36 356.57110304.54362.8706 10321.7365.561710327.67367.3145
#Mann= 3 , 0 , 0
9828.972    0.12       09828.972    0.12       010327.67    0.12       0
#XS Ineff= 2 , 0
       0                               0
Bank Sta=9828.972,10327.67
Exp/Cntr=0.3,0.1

Type RM Length L Ch R = 1 ,29245.08,148.574700,148.574700,148.574700
XS GIS Cut Line= 6
826799.435258567837455.888471906826842.919706965837459.803303868
826924.969662202837472.434514715826973.662857194837484.505535354
827069.966402956 837515.89659514827238.786409675837585.590226102
#Sta/Elev= 30
9818.416332.10529844.084323.40459874.299314.6061 9914.77305.58579935.005303.0092
9945.124302.34949955.426300.23339965.729294.31529976.032289.60539986.335285.7576
9996.659284.049310007.16283.874410017.68285.5724 10028.2290.681210049.24294.5209
10059.76297.320310070.29298.229110080.81297.802610091.33 298.53710101.95299.9421
10112.68302.562710123.41308.148710134.14311.443810144.87313.472710166.33322.1229
10188.05336.403710198.93340.581110226.98353.109310264.22364.960510279.22368.6389
#Mann= 3 , 0 , 0
9818.416    0.12       09818.416    0.12       010279.22    0.12       0
#XS Ineff= 2 , 0
       0                               0
Bank Sta=9818.416,10279.22
Exp/Cntr=0.3,0.1

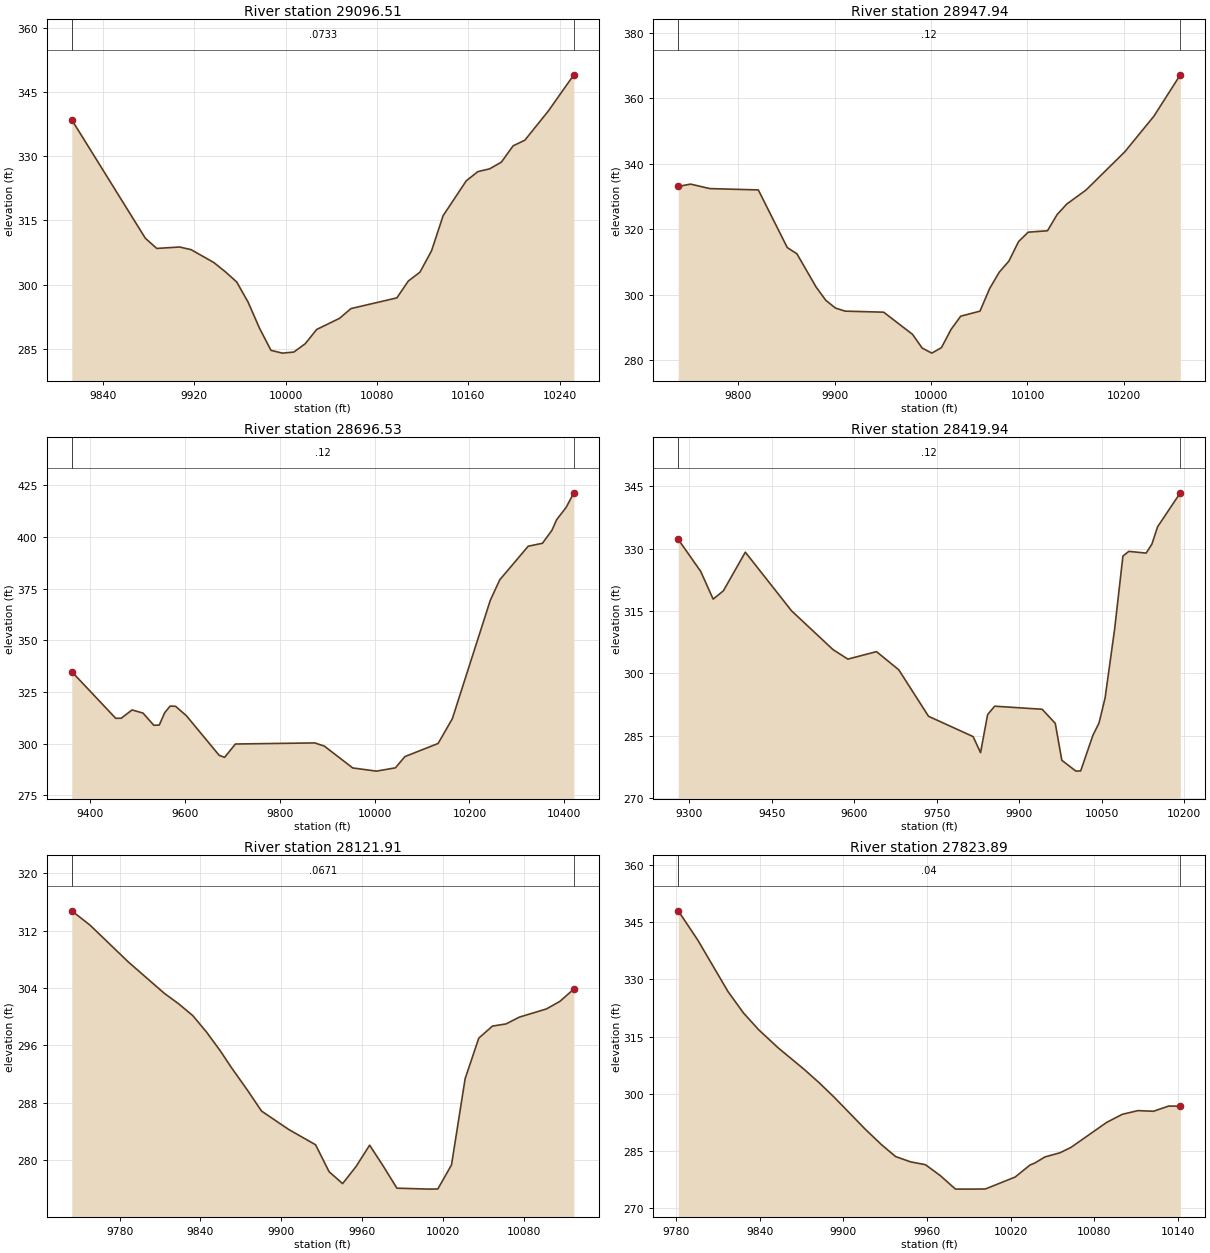
Type RM Length L Ch R = 1 ,29096.51,148.574700,148.574700,148.574700
XS GIS Cut Line= 6
826760.599847654837626.764280075826777.610987719837627.574515606
826997.877793292837631.337530895827053.669262901837636.862991722
827114.573031448837647.187649755827196.706802021837666.990122869
#Sta/Elev= 30
9812.699338.52389877.125310.85019887.126308.47139907.128308.8044 9917.13308.1909
9937.132305.17389947.133303.02979957.135300.63389967.136295.91219977.137289.8204
9987.138284.6624 9997.14284.011210007.14284.263810017.14286.209810027.15 289.537
10047.15292.139610057.19294.418210097.38296.918710107.44 300.86310117.59302.9259
10127.73307.912110137.87316.118110158.16324.270610168.31326.416410178.59327.0638
10188.88328.630210199.17332.441210209.45333.759310230.03340.585610252.35349.0303
#Mann= 3 , 0 , 0
9812.699  0.0733       09812.699  0.0733       010252.35  0.0733       0
#XS Ineff= 2 , 0
       0                               0
Bank Sta=9812.699,10252.35
Exp/Cntr=0.3,0.1

Type RM Length L Ch R = 1 ,28947.94,251.409900,251.409900,251.409900
XS GIS Cut Line= 6
826692.275847877837768.353111344826728.167964731837772.851938232
826799.413970308837777.786184451827027.081447585837778.614349167
 827121.53220367837782.966744218827212.255237187837793.100473761
#Sta/Elev= 30
9737.516333.0655 9750.34333.75729770.497332.38469820.634331.98819850.693314.3795
9860.696312.47429880.701302.28379890.703 298.2599900.706295.89649910.708294.9585
9950.709294.6408 9980.71287.8652 9990.71 283.67610000.71282.131210010.71283.8107
10020.71 289.38210030.71293.420110050.71294.956110060.71301.848110070.71306.8597
10080.72310.242310090.73316.199210100.74319.078310120.76319.506610130.77324.4584
10140.78327.6681 10160.8331.963910201.02343.631610231.21354.500810258.63367.1423
#Mann= 3 , 0 , 0
9737.516    0.12       09737.516    0.12       010258.63    0.12       0
#XS Ineff= 2 , 0
       0                               0
Bank Sta=9737.516,10258.63
Exp/Cntr=0.3,0.1

Type RM Length L Ch R = 1 ,28696.53,276.590100,276.590100,276.590100
XS GIS Cut Line= 3
826374.183199704837792.388444081826792.541461855838027.779210746
827371.253259301838036.002468958
#Sta/Elev= 30
9361.365334.83399454.096312.3003 9465.57312.34049488.518316.34959511.467314.8593
9534.415308.93059545.889309.04549557.364315.02289568.838 318.2229580.312 318.108
9603.261313.51649672.106294.4489 9683.58293.41659706.529299.8854 9873.86300.4055
9893.862298.89249953.868288.309710003.87 286.76910043.88288.358410063.88 293.799
10133.89300.140410163.89312.0872 10243.9  369.31 10263.9379.264410323.91395.5094
10353.91396.940310373.91403.189910383.91408.349810403.91414.281310420.17421.3276
#Mann= 3 , 0 , 0
9361.365    0.12       09361.365    0.12       010420.17    0.12       0
#XS Ineff= 2 , 0
       09890.709                       0
Bank Sta=9361.365,10420.17
Exp/Cntr=0.3,0.1

Type RM Length L Ch R = 1 ,28419.94,298.024900,298.024900,298.024900
XS GIS Cut Line= 6
826379.054981413837875.318403269826500.347600832837945.029597954
 826607.99880305838022.068813913 826892.97594968838265.227597144
827013.619758687838332.252097329827135.111191848838369.200355121
#Sta/Elev= 30
9279.909332.21999320.707324.52689343.407317.85319362.002319.8572  9401.9  329.14
9485.981315.03289561.351305.70999588.298  303.439640.372305.23029680.901300.8539
9734.939289.68719815.996284.80749829.505280.95119842.341290.09049855.165292.1174
9941.537 291.3769965.358287.98849977.268279.113710002.87276.504310011.56276.5662
10033.84285.141510044.89 288.07210055.93294.107510073.18310.570310088.34328.2023
10099.04329.330310130.57328.918210140.97331.066910151.37335.246210192.66343.4047
#Mann= 3 , 0 , 0
9279.909    0.12       09279.909    0.12       010192.66    0.12       0
#XS Ineff= 2 , 0
       09893.598                       0
Bank Sta=9279.909,10192.66
Exp/Cntr=0.3,0.1

Type RM Length L Ch R = 1 ,28121.91,298.024900,298.024900,298.024900
XS GIS Cut Line= 6
826645.608705857838143.312508386826682.329011295 838225.50141261
826693.291062571838285.313704708826691.526032536838358.076066599
826677.195449774838448.710058028826677.628466453838505.149543523
#Sta/Elev= 30
9744.537314.77159758.058312.77899786.534307.62589813.107303.26669823.687301.8081
9834.267300.15079844.564297.82739854.847295.18579862.477293.01629875.174289.6418
9885.268286.82149905.375284.2545  9925.4282.10659935.419278.34459945.437 276.686
9955.456279.08749965.475282.05419975.568279.13759985.695276.0508 10009.8275.9166
10016.08275.9404 10026.2279.297810036.32291.338310046.44 296.99810056.56298.6781
10066.61298.980910076.62299.936510096.63301.072610106.64302.137610116.95303.8467
#Mann= 3 , 0 , 0
9744.537  0.0671       09744.537  0.0671       010116.95  0.0671       0
#XS Ineff= 2 , 0
       0                               0
Bank Sta=9744.537,10116.95
Exp/Cntr=0.3,0.1

Type RM Length L Ch R = 1 ,27823.89,298.025000,298.025000,298.025000
XS GIS Cut Line= 6
826222.287987818838366.031011463826361.300742929838427.509080155
826424.216680543838452.087837826826474.615297259838471.274783878
826540.014721926838504.224698936 826552.74340852838509.045389429
#Sta/Elev= 30
9781.453347.92899795.353 340.3429817.221326.75749828.352321.1423 9839.09316.8144
9853.077312.07099871.893306.38279882.827302.81989893.761298.9583 9915.63290.7405
 9927.25286.70339937.424283.56329948.158282.18199958.892281.42449969.626278.5436
 9980.36275.04799991.095275.029510001.84275.065810023.24278.193610033.94281.3559
10037.29281.844410044.64283.465210055.36284.545910063.21285.934510088.95292.5139
10100.15294.627610111.35295.593610122.54295.428310133.49296.796110141.77  296.74
#Mann= 3 , 0 , 0
9781.453    0.04       09781.453    0.04       010141.77    0.04       0
#XS Ineff= 2 , 0
       0                               0
Bank Sta=9781.453,10141.77
Exp/Cntr=0.3,0.1

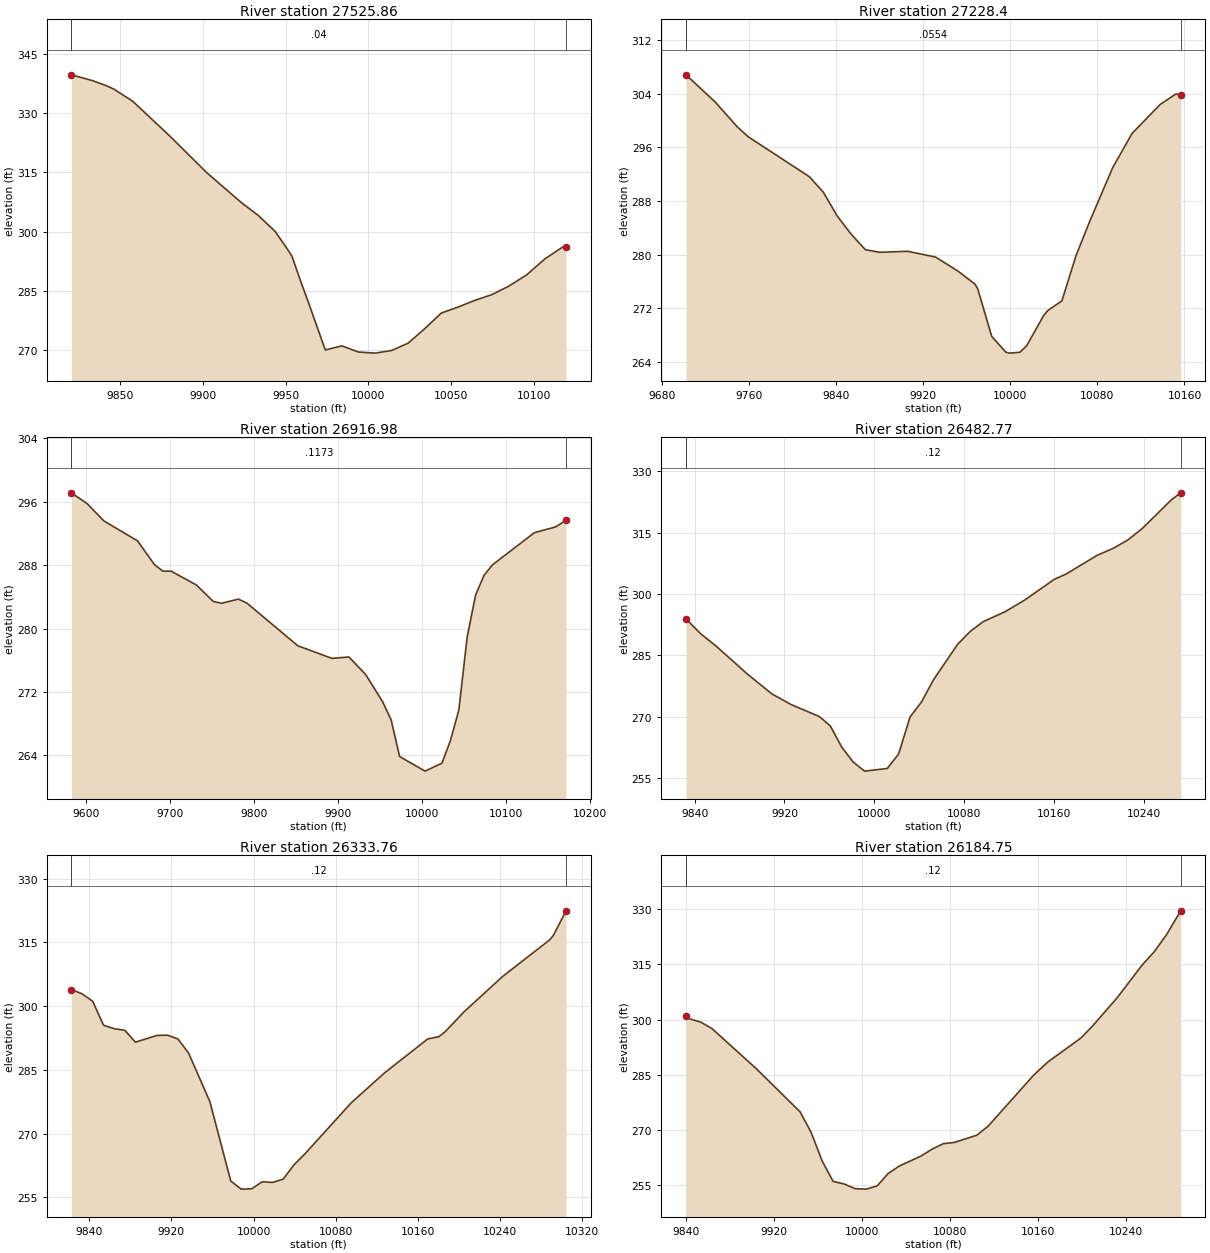
Type RM Length L Ch R = 1 ,27525.86,297.460600,297.460600,297.460600
XS GIS Cut Line= 6
826482.209031146 838825.29080805826511.004262711838781.971238373
826531.294285804838727.297090851826539.522913879838617.541709994
826545.786934199838579.729512445826561.165328202838543.354238889
#Sta/Elev= 30
9820.562339.70519833.505338.21469841.653336.95099846.081336.12989857.661333.0041
9880.288 324.1039902.588314.85429923.036 307.4529933.435304.13089943.619300.1042
9950.672295.84629953.803293.82479959.073287.46149963.916281.95219973.953270.0965
9983.982271.12589993.983269.572310003.99 269.28910013.99269.949810023.99271.8087
10033.99275.462410044.02279.426610054.16 280.944 10064.3282.637110074.43284.0614
10084.79286.231710095.41289.033710106.85293.201110117.51296.1616 10119.4296.2157
#Mann= 3 , 0 , 0
9820.562    0.04       09820.562    0.04       0 10119.4    0.04       0
#XS Ineff= 2 , 0
       0                               0
Bank Sta=9820.562,10119.4
Exp/Cntr=0.3,0.1

Type RM Length L Ch R = 1 , 27228.4,311.415200,311.415200,311.415200
XS GIS Cut Line= 4
826598.223773883838891.895357522826706.047070861838878.553116754
826912.104665428838625.475668326826926.267773018 838612.07813412
#Sta/Elev= 30
9702.001306.82839728.981302.74749749.134299.0587 9759.21297.58429815.228291.6429
9828.124289.32999841.019285.75079853.915283.0246 9866.81280.75089879.706280.3606
9905.497280.51139931.288 279.6499951.531277.59369967.369275.63129969.974274.9381
 9982.87267.82149995.765 265.4689999.045265.321210008.66265.446910014.88266.3976
10030.72270.958710034.45271.685410047.35273.115110060.24279.814210073.14285.0591
10094.07292.991510111.82298.081110137.69302.418210152.25303.9852 10156.5303.7673
#Mann= 3 , 0 , 0
9702.001  0.0554       09702.001  0.0554       0 10156.5  0.0554       0
#XS Ineff= 2 , 0
       0                               0
Bank Sta=9702.001,10156.5
Exp/Cntr=0.3,0.1

Type RM Length L Ch R = 1 ,26916.98,434.211400,434.211400,434.211400
XS GIS Cut Line= 6
826616.156173887838931.648615181826756.734454415838931.560640051
 826819.58345971838936.000640314826957.326538257838957.791980756
827111.599758127838944.261227631827202.548252798 838950.26291263
#Sta/Elev= 30
9582.014297.12389600.867295.74839620.877293.56679660.891291.06169680.895288.0768
9690.898 287.249  9700.9287.24019730.925285.49979750.975 283.431    9761283.1883
 9781.05 283.7179791.112 283.2189851.814277.8322 9892.56276.24179912.806276.4175
9932.871274.1722 9952.89270.76739963.012268.49419973.141  263.8610003.48262.0174
10023.64263.024810033.66265.869910043.67269.693810053.67278.943910063.68284.2256
10073.69286.7066 10083.7  288.0310133.77292.099410158.96292.818710171.47293.6759
#Mann= 3 , 0 , 0
9582.014  0.1173       09582.014  0.1173       010171.47  0.1173       0
#XS Ineff= 2 , 0
       0                               0
Bank Sta=9582.014,10171.47
Exp/Cntr=0.3,0.1

Type RM Length L Ch R = 1 ,26482.77,149.012500,149.012500,149.012500
XS GIS Cut Line= 6
826595.893386753 838962.96362958826628.289641198839002.103210396
826645.541335127839042.324965186826680.332521272839190.366867666
826730.538895331839258.310803465826811.234907895839330.283373742
#Sta/Elev= 30
9832.355293.92299845.205290.35559859.161287.28659886.654280.53769908.727275.6285
9925.706273.03269950.751270.11979954.448269.30389960.965267.71959971.093262.5748
9981.221258.9575 9991.35256.742210011.55257.392110021.64260.916910031.88269.9782
10042.16273.690510052.56278.981210074.13287.711110085.36290.8625 10097.1293.2817
10116.45295.683410134.13298.5758 10160.3303.614610170.79304.895110198.41309.4675
10212.23311.102810225.83313.2263 10238.8316.071210264.53323.030910272.83324.7403
#Mann= 3 , 0 , 0
9832.355    0.12       09832.355    0.12       010272.83    0.12       0
#XS Ineff= 2 , 0
       0                               0
Bank Sta=9832.355,10272.83
Exp/Cntr=0.3,0.1

Type RM Length L Ch R = 1 ,26333.76,149.012400,149.012400,149.012400
XS GIS Cut Line= 6
826385.144405173839156.055686406826508.662418279839190.599272352
826584.854597857839205.287409202826625.929710576839221.111995939
826672.410246238839250.315166518826814.958554597839354.354089937
#Sta/Elev= 30
9822.794303.8917  9833.1302.89529843.557301.12559854.014295.49779864.456294.6849
9874.809294.28679885.161291.50289905.866293.08529916.219293.15189926.572292.2471
9936.924288.88969957.522277.51379977.889258.82539988.073256.91879998.256256.9931
10008.43258.642310018.62258.496210028.82259.265210039.31262.611510049.81265.1617
10095.28277.278910127.65284.299610169.52292.260910180.38292.790910186.49293.9626
10205.14298.709510242.28306.934910288.26315.5943 10291.8316.627410304.13322.4132
#Mann= 3 , 0 , 0
9822.794    0.12       09822.794    0.12       010304.13    0.12       0
#XS Ineff= 2 , 0
       0                               0
Bank Sta=9822.794,10304.13
Exp/Cntr=0.3,0.1

Type RM Length L Ch R = 1 ,26184.75,149.012500,149.012500,149.012500
XS GIS Cut Line= 6
826391.598328737839342.631109173826434.546895925839347.044427791
 826575.01633547839349.023416848826656.617885279839357.576147616
 826727.72645803839378.663494878826826.089674152839426.308827107
#Sta/Elev= 30
9840.205301.00819843.655300.17419853.714299.28899863.758297.55449903.847286.7135
 9943.85274.92799953.851269.36569963.852 261.6119973.853256.03519983.854255.3449
9993.855254.072310003.86 253.94210013.86254.806110023.86258.182810033.89260.1999
10053.95262.968910063.98264.848310074.01 266.28210084.08266.633110104.35 268.584
10114.62 271.02410156.23284.963210168.85288.460510198.97294.984710209.82298.3431
10232.05305.977210254.32  314.72 10265.5 318.38710276.94 323.14210289.61329.5377
#Mann= 3 , 0 , 0
9840.205    0.12       09840.205    0.12       010289.61    0.12       0
#XS Ineff= 2 , 0
       0                               0
Bank Sta=9840.205,10289.61
Exp/Cntr=0.3,0.1