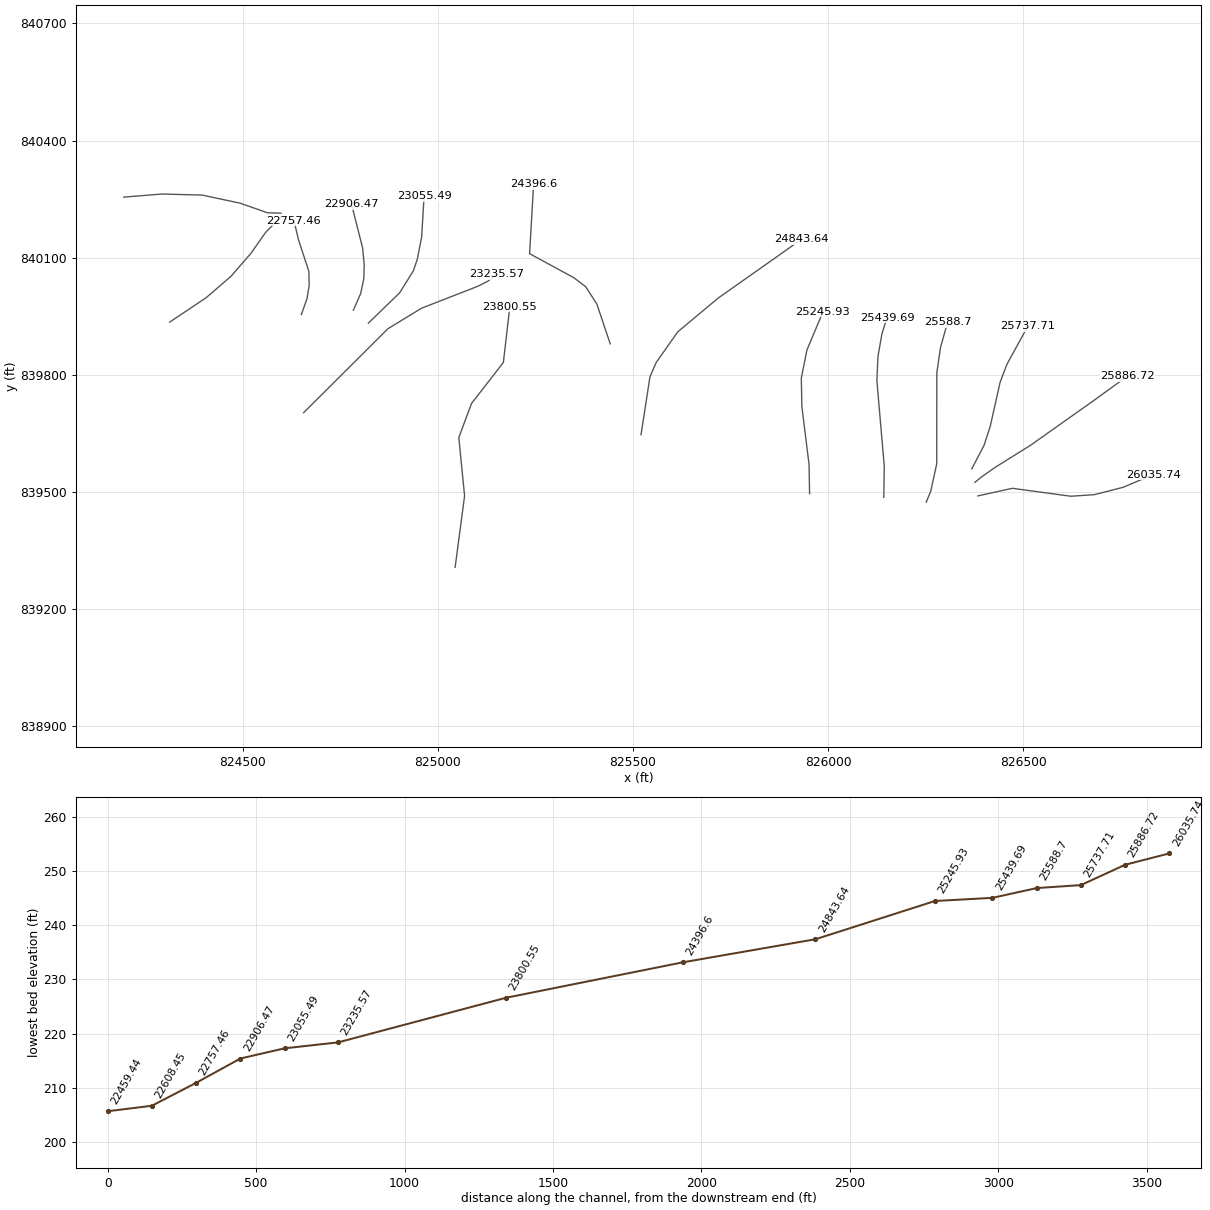
HEC-RAS study 18370_ras.prj: 18370

--- 18370_ras.g01 (geometry) --- (continued)

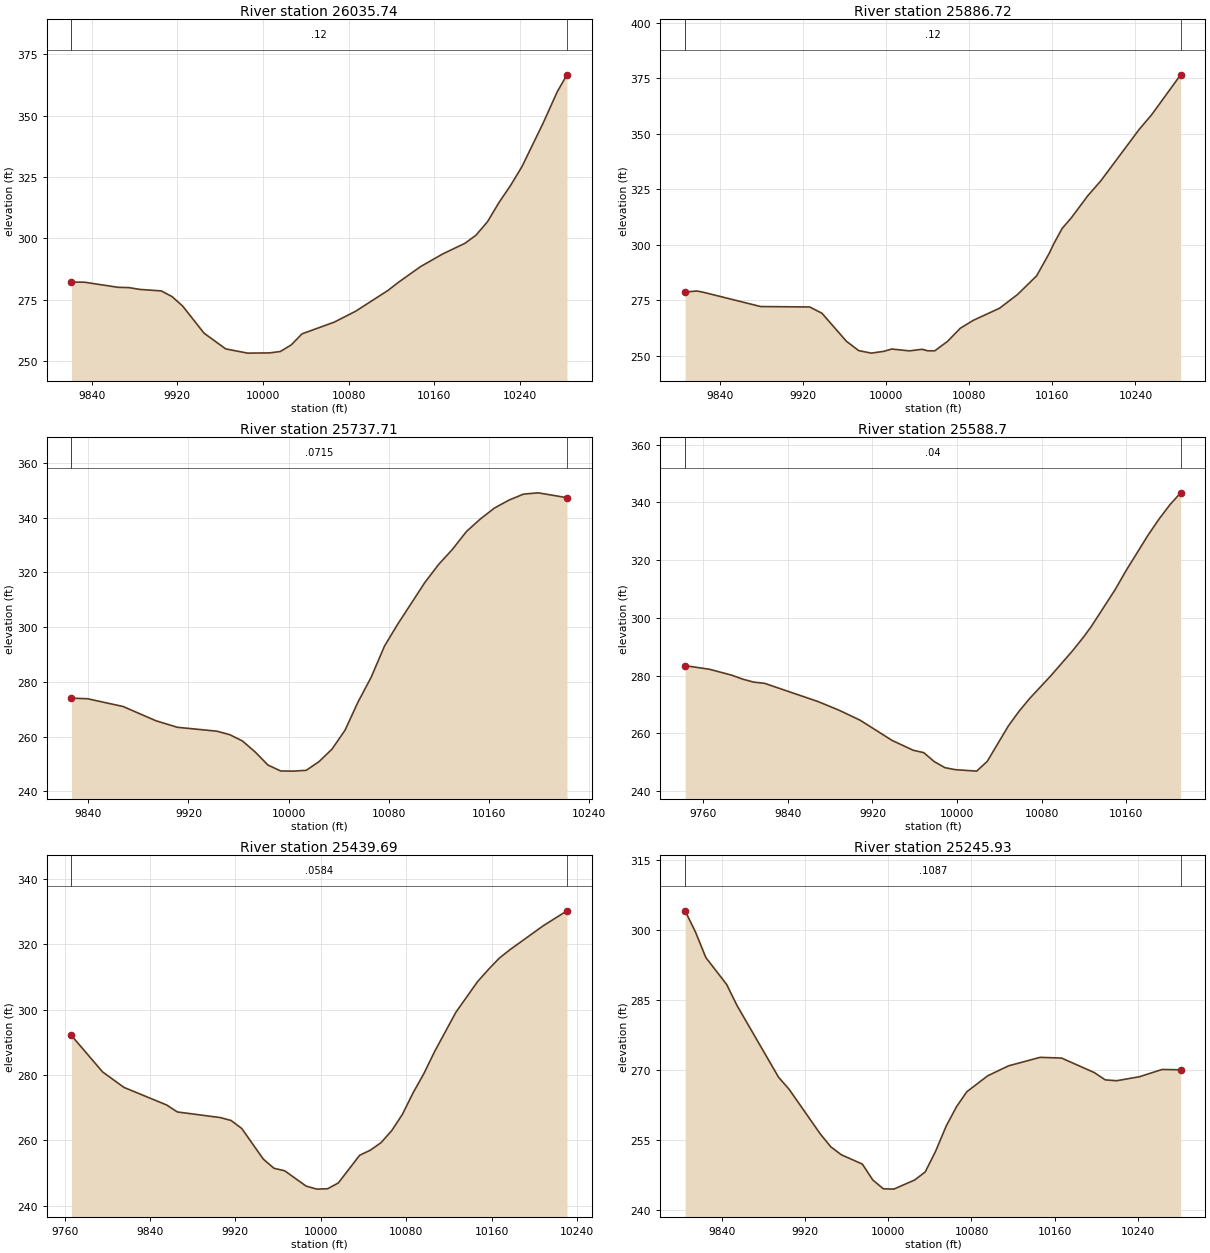
Type RM Length L Ch R = 1 ,26035.74,149.012500,149.012500,149.012500
XS GIS Cut Line= 6
826383.856477644839489.514884993826472.249882115839508.968019928
826621.918177346839488.626198517 826682.61199294 839492.74035012
826756.247411622839511.649433393826833.214791728839544.234782268
#Sta/Elev= 30
9820.995282.20559833.156282.17439864.492280.09139874.676279.97299884.838279.2391
9904.893278.62799914.915276.33999924.924 272.454 9944.99261.37219965.189 254.985
9985.623253.260210006.05253.352110016.21253.920910026.37256.5937 10036.5261.1237
10066.58265.885510086.58 270.33610116.74278.787610126.84282.209910147.25288.5219
10167.88293.662610188.76 298.03310199.19301.366710209.96306.900210220.55314.6302
10231.24321.479710242.16329.371310261.74346.9371 10275.1359.859810284.12366.7054
#Mann= 3 , 0 , 0
9820.995    0.12       09820.995    0.12       010284.12    0.12       0
#XS Ineff= 2 , 0
       0                               0
Bank Sta=9820.995,10284.12
Exp/Cntr=0.3,0.1

Type RM Length L Ch R = 1 ,25886.72,149.012400,149.012400,149.012400
XS GIS Cut Line= 6
826376.067469035839524.360449791 826394.36711567839538.970707863
826428.793409312839563.082390263826518.899347908839619.314906505
826677.774633061839731.748575842 826767.40518796839796.684737846
#Sta/Elev= 30
9806.575 278.7419818.005279.14639823.627278.66099879.337272.15689926.488271.9721
9938.275269.1485 9961.85256.50639973.638 252.3069985.725 251.1659998.004251.9866
10005.42253.010510022.45252.1815 10034.7252.900910040.04252.216610046.95252.2155
 10059.2256.477210071.46262.377410083.71265.881710109.27271.416810126.58277.5989
10144.97286.029710157.22296.303410161.19300.224910169.47307.357910178.41312.1901
10194.14322.084910206.49328.697110243.54351.935810255.89358.763910283.55376.6055
#Mann= 3 , 0 , 0
9806.575    0.12       09806.575    0.12       010283.55    0.12       0
#XS Ineff= 2 , 0
       0                               0
Bank Sta=9806.575,10283.55
Exp/Cntr=0.3,0.1

Type RM Length L Ch R = 1 ,25737.71,149.012500,149.012500,149.012500
XS GIS Cut Line= 6
826368.317229159839559.032575517826399.524719278839618.691180384
826415.394859885839667.298549827826440.722627526839780.418049274
826458.204781537839826.492922615826512.026623315839924.624162564
#Sta/Elev= 30
9826.529274.09289839.492273.84619867.802271.02019893.941265.83159911.097263.4287
9942.655262.00479952.923260.74379963.115258.44639973.307254.40979983.499 249.633
9993.691247.469310003.89 247.41210014.09247.707710024.34250.891510034.71255.4632
10045.07262.351210055.44272.632410065.96281.709410076.66293.147510087.35301.2264
10108.74316.250310119.82322.903610130.96328.4763 10142.1334.959710153.25339.5486
10164.39343.508410175.93 346.39410187.65348.608310199.38349.082910222.38347.3064
#Mann= 3 , 0 , 0
9826.529  0.0715       09826.529  0.0715       010222.38  0.0715       0
#XS Ineff= 2 , 0
       0                               0
Bank Sta=9826.529,10222.38
Exp/Cntr=0.3,0.1

Type RM Length L Ch R = 1 , 25588.7,149.012400,149.012400,149.012400
XS GIS Cut Line= 6
826251.622203676839473.580898483826263.258725902839502.144364638
826278.454218086839571.802933095826278.639567406839804.110672723
826287.887030167839869.342930965826306.340044002839934.491046452
#Sta/Elev= 30
9742.894283.42039766.023282.15729787.052280.11089797.409278.73179807.766277.7086
9818.003277.29219868.382270.99589888.416267.97179908.425264.48869938.439257.5275
9958.449254.10299968.453253.27079978.458250.15239988.463248.06479998.467247.3642
10018.47246.860910028.48250.244210048.49262.5455 10058.5267.5884 10068.5272.0086
10088.57279.912710108.69288.385110118.83293.008510126.63296.877310149.39309.7719
10159.74 316.38110180.44328.610410190.79334.187710201.15339.192910211.29343.3159
#Mann= 3 , 0 , 0
9742.894    0.04       09742.894    0.04       010211.29    0.04       0
#XS Ineff= 2 , 0
       0                               0
Bank Sta=9742.894,10211.29
Exp/Cntr=0.3,0.1

Type RM Length L Ch R = 1 ,25439.69,193.754600,193.754600,193.754600
XS GIS Cut Line= 6
826142.750960596839485.949256327 826144.10198324839564.550067186
826125.107716494839784.809982581826127.883089149839846.631727069
826137.973796855839904.380569067826151.000575906839946.193377555
#Sta/Elev= 30
 9766.44292.12519795.569280.97859815.571276.22959855.628 270.827 9865.68268.6957
9905.888266.9733 9915.94266.09019925.992263.62499946.096254.27059956.148251.4402
  9966.2250.67449986.304245.97179996.346245.056410006.37245.174610016.38246.9403
10036.41255.435110046.42256.990310056.43259.301610066.45262.989210076.46267.9834
10086.47274.578110096.48280.408810106.49287.135410126.51299.229410146.79308.6126
10156.94312.323710167.09315.793510177.24318.422310208.36  325.7410230.56330.3102
#Mann= 3 , 0 , 0
 9766.44  0.0584       0 9766.44  0.0584       010230.56  0.0584       0
#XS Ineff= 2 , 0
       0                               0
Bank Sta=9766.44,10230.56
Exp/Cntr=0.3,0.1

Type RM Length L Ch R = 1 ,25245.93,402.295300,402.295300,402.295300
XS GIS Cut Line= 6
 825952.69717962839495.006437083825951.346070402839569.844273288
825932.951269709839718.612456426825931.497293858839791.131764492
825945.904792929839863.321277519825986.908703618839960.959954784
#Sta/Elev= 30
9804.214304.08139814.209299.5431 9824.21294.06659844.214288.31449854.215283.7975
9894.275268.41929904.311265.8785 9934.43256.28379944.535253.53319954.639251.8315
9974.848249.84759984.953246.43949995.057 244.54710005.16244.472410025.37  246.44
10035.43248.148210045.46252.583610055.49257.901810065.52262.107910075.52265.3298
10095.54268.738210115.72270.8808 10146.1272.700710166.77272.545810198.27269.4383
10208.84267.874710219.73267.689810241.65268.539510263.57270.098810281.43270.0266
#Mann= 3 , 0 , 0
9804.214  0.1087       09804.214  0.1087       010281.43  0.1087       0
#XS Ineff= 2 , 0
       0                               0
Bank Sta=9804.214,10281.43
Exp/Cntr=0.3,0.1

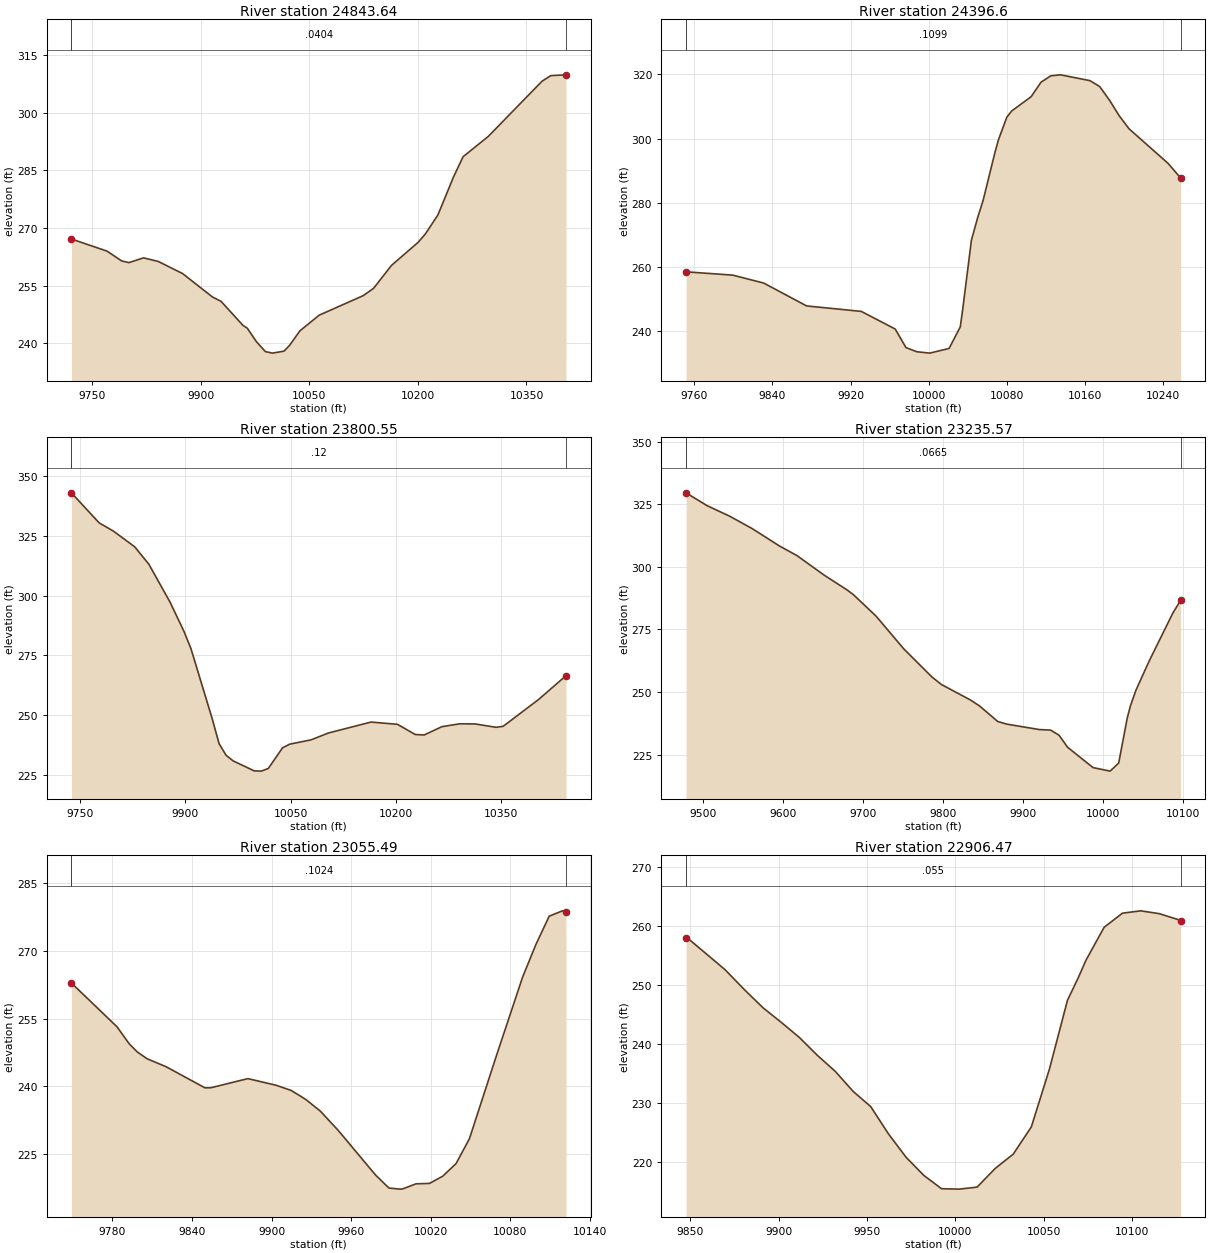
Type RM Length L Ch R = 1 ,24843.64,447.037400,447.037400,447.037400
XS GIS Cut Line= 6
825520.870167613839646.083083272825543.733720005839794.527290285
825559.809174269839831.449068025825615.114505917839909.975799769
 825718.76331374839996.496841371 825932.04832539840146.878271073
#Sta/Elev= 30
9721.486267.13099770.761 263.9769790.907261.4228 9800.98260.98499821.126262.2263
9841.513261.28719875.055258.13779916.347252.03479928.161250.9076 9958.41244.6462
9964.383243.91769976.873 240.4399989.364237.8184    9999237.415510015.11237.9275
 10022.9239.450610037.12243.224510063.72247.297810124.55252.387310138.91254.3007
10163.49260.2413 10200.2266.238710210.44268.463510227.79273.430310249.14283.2408
 10262.5288.574610297.21293.8399 10371.5308.226910383.73309.689410404.59309.8905
#Mann= 3 , 0 , 0
9721.486  0.0404       09721.486  0.0404       010404.59  0.0404       0
#XS Ineff= 2 , 0
       09954.515                       0
Bank Sta=9721.486,10404.59
Exp/Cntr=0.3,0.1

Type RM Length L Ch R = 1 , 24396.6,596.049800,596.049800,596.049800
XS GIS Cut Line= 6
825441.968428463839879.126647934825407.744700462839980.963378012
825379.185574055 840025.37230964825349.182924867840048.205189124
825235.424799234840110.100506514825245.665729135840287.765793994
#Sta/Elev= 30
9751.672258.49139799.543257.45549831.142254.98259875.063247.85819930.949246.1591
9965.677240.66759976.736234.87399987.795233.5821   10001233.151210020.86 234.615
10032.29241.323810034.85 246.93810043.72268.375510050.02275.3049 10055.6280.6747
10068.03295.991210071.33299.617810079.92306.670910084.83308.598810104.87313.0851
10114.88317.5758 10124.9319.580510134.92319.890610164.96318.085310174.98316.2406
   10185 311.98910195.01307.109610205.03303.0694 10245.1292.261110257.88287.7213
#Mann= 3 , 0 , 0
9751.672  0.1099       09751.672  0.1099       010257.88  0.1099       0
#XS Ineff= 2 , 0
       0                               0
Bank Sta=9751.672,10257.88
Exp/Cntr=0.3,0.1

Type RM Length L Ch R = 1 ,23800.55,564.981100,564.981100,564.981100
XS GIS Cut Line= 6
825044.581500279839306.358292389825068.865765077839489.513385428
825054.075083059839638.890950788825086.627988398839726.293422103
825168.221264064839831.396624729825184.715469049839974.012164324
#Sta/Elev= 30
9737.295343.03119776.913330.4548 9797.16327.0303 9827.53320.46149847.776313.1757
9877.851297.37789897.886285.05659907.904277.78199937.943 248.7099947.951238.0783
 9957.96233.23159967.968 230.885 9998.02226.711610008.09226.600610018.16 227.713
10038.42236.338410048.56237.873310079.31239.697810104.09242.569510164.68247.1259
 10202.4246.183310227.72241.916310240.38241.7192 10265.7245.193710291.02246.3978
10312.81246.347410343.02244.930610353.09245.348610403.43256.519710442.71266.5273
#Mann= 3 , 0 , 0
9737.295    0.12       09737.295    0.12       010442.71    0.12       0
#XS Ineff= 2 , 0
       0                10173.21       0
Bank Sta=9737.295,10442.71
Exp/Cntr=0.3,0.1

Type RM Length L Ch R = 1 ,23235.57,180.081200,180.081200,180.081200
XS GIS Cut Line= 6
824656.534619749839702.783495218824872.610039234839917.864225298
824958.495639592839970.318100899825102.247672111 840026.36261487
 825127.70527181840038.978055909825151.869115353840057.653833047
#Sta/Elev= 30
9478.646329.5539  9504.7324.46419532.919320.26369561.138 315.3069595.187308.3769
9617.577304.44169651.886296.57469680.236 290.7419688.125288.84929716.344280.3195
 9751.11267.2057 9786.38255.96319798.346252.94559834.246246.84299845.818244.4342
9868.747238.18249880.211237.13619920.608234.98149934.849234.76629945.477232.7053
9956.106227.90379987.992 219.77910009.32218.370310020.06221.592410030.79239.6018
10034.83244.506510041.65250.686510058.03262.227910087.95281.585610097.65286.5986
#Mann= 3 , 0 , 0
9478.646  0.0665       09478.646  0.0665       010097.65  0.0665       0
#XS Ineff= 2 , 0
       0                               0
Bank Sta=9478.646,10097.65
Exp/Cntr=0.3,0.1

Type RM Length L Ch R = 1 ,23055.49,149.012500,149.012500,149.012500
XS GIS Cut Line= 6
824822.375082102839932.163380901824902.494861197840009.785058933
824937.578551122840066.018724798824947.622109514840095.593050076
824958.825940428840152.435880741824965.152680456840257.654284101
#Sta/Elev= 30
 9749.14262.86749783.564253.16699792.741249.41029798.638247.66139806.105246.1225
9820.432244.36319849.813 239.6799854.292239.70059882.164241.71949903.439  240.25
9914.771239.10519921.777237.85119926.104237.04119936.743234.53999950.337230.2391
 9978.27220.43049988.461217.52259996.753217.27839998.652217.307110008.87218.4489
10019.01218.539110029.04220.145410039.07222.931410049.11228.409610069.17246.5138
10089.24264.194110099.26271.391710109.26277.647910119.26278.827610121.91278.5115
#Mann= 3 , 0 , 0
 9749.14  0.1024       0 9749.14  0.1024       010121.91  0.1024       0
#XS Ineff= 2 , 0
       0                               0
Bank Sta=9749.14,10121.91
Exp/Cntr=0.3,0.1

Type RM Length L Ch R = 1 ,22906.47,149.012500,149.012500,149.012500
XS GIS Cut Line= 6
824783.844970512839965.313819203 824802.69529226840008.023503466
824810.716068724840046.684752426824811.735174812840081.458496314
824807.671979286840124.369440774824779.273511392840236.727316684
#Sta/Elev= 30
9847.518258.0533 9850.17257.52269869.569252.62339880.397249.2766 9891.06246.1652
9901.409243.68389911.622241.13289921.835238.09469932.048235.35459942.087231.9828
9952.091229.38849962.096224.7734 9972.11220.79379982.143217.72119992.176215.4594
10002.22215.390510012.32215.733410022.56218.8977 10032.8221.329410043.03225.9478
10053.27235.739910063.51247.436210069.68251.296210073.86254.157210084.25 259.809
10094.64262.207510105.03 262.60410115.43262.126610125.82261.151410127.61260.9234
#Mann= 3 , 0 , 0
9847.518   0.055       09847.518   0.055       010127.61   0.055       0
#XS Ineff= 2 , 0
       0                               0
Bank Sta=9847.518,10127.61
Exp/Cntr=0.3,0.1

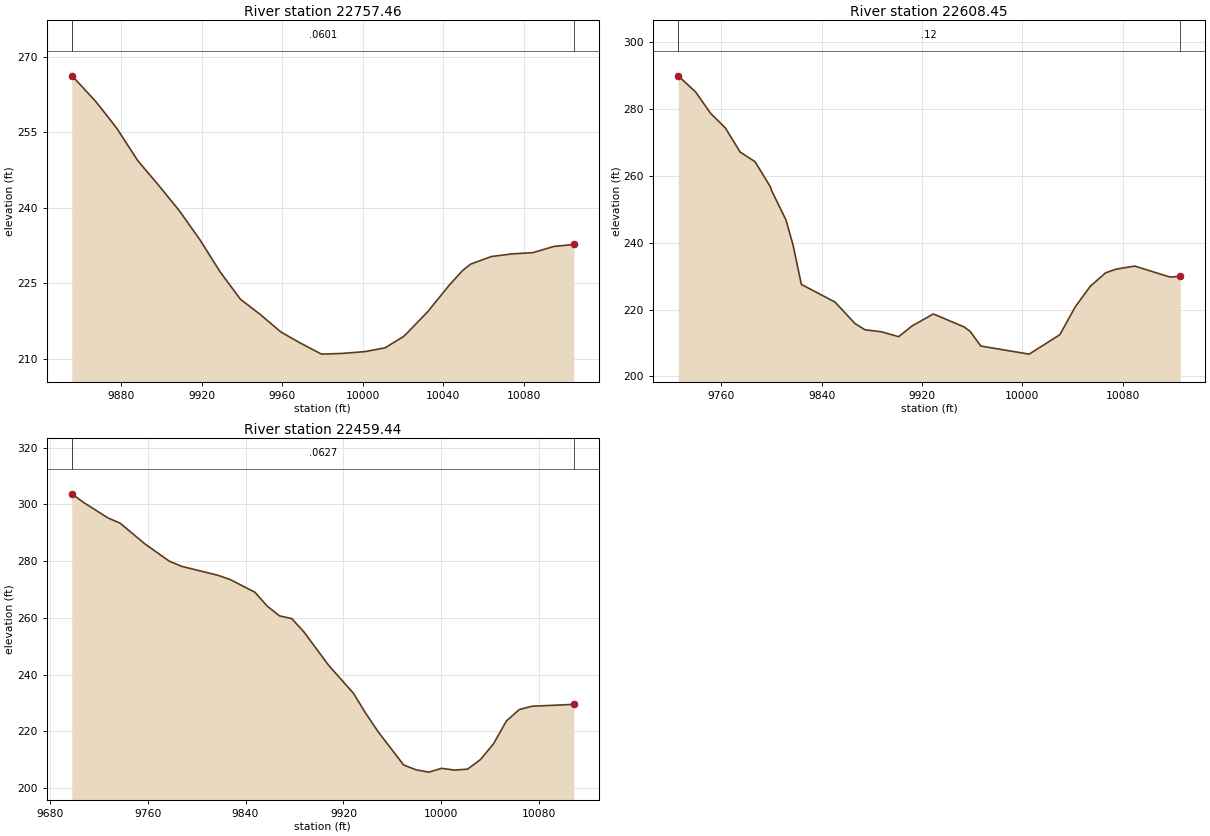
Type RM Length L Ch R = 1 ,22757.46,149.012400,149.012400,149.012400
XS GIS Cut Line= 6
 824650.74575325839954.165183885824665.212257068 839995.06274269
824670.733437994840028.223232459824669.978087461840064.520127877
 824643.20967646840146.240637541824631.723364614840194.856918507
#Sta/Elev= 29
 9855.44266.21979856.346265.89939867.194261.1874 9872.54258.50689877.852255.7714
9888.328 249.3169898.803244.37159908.942239.3797 9919.08233.65759929.218227.2284
9939.264221.80719949.266218.73499959.268 215.3299969.282213.05329979.531210.9037
9989.781211.0444   10001211.399610011.07 212.14910020.16214.3656 10021.7214.9427
10032.33219.338410042.96224.582210049.64227.5181 10053.6228.785610063.97 230.306
 10074.3230.828210084.63 231.07810094.97232.302510104.93232.7066
#Mann= 3 , 0 , 0
 9855.44  0.0601       0 9855.44  0.0601       010104.93  0.0601       0
#XS Ineff= 2 , 0
       0                               0
Bank Sta=9855.44,10104.93
Exp/Cntr=0.3,0.1

Type RM Length L Ch R = 1 ,22608.45,149.012500,149.012500,149.012500
XS GIS Cut Line= 6
824313.188902579839934.633802538824407.012340262839997.467854138
824470.550282964840052.160077992  824521.9111768840111.413415901
824559.323110425    840164.86655824601.396203638840207.137650912
#Sta/Elev= 30
9725.689289.99299739.639285.11899751.449278.78389763.259274.3943 9775.07267.1716
9786.942264.28959799.253256.71779800.141255.63569811.564246.87959817.286239.2773
9823.875227.54639850.686222.26139866.648215.8177 9874.57213.97279887.867213.3473
9901.439211.89919911.952215.05519929.086218.71149953.694214.80669958.497213.4783
9966.974209.089910005.52 206.67510029.99212.496810042.13220.762610054.28227.0087
10066.44231.005310074.72232.107210089.62233.035810117.72229.762210126.03229.9548
#Mann= 3 , 0 , 0
9725.689    0.12       09725.689    0.12       010126.03    0.12       0
#XS Ineff= 2 , 0
       09955.838                       0
Bank Sta=9725.689,10126.03
Exp/Cntr=0.3,0.1

Type RM Length L Ch R = 1 ,22459.44,149.012500,149.012500,149.012500
XS GIS Cut Line= 6
 824195.69860901840254.967871594824293.518422352840262.887230629
824396.345174661840260.193313041824493.912619407 840239.43609376
 824563.49643456840214.968258693824598.556268692840213.764165793
#Sta/Elev= 30
9698.027303.6946  9707.4300.73389727.491295.22919737.517293.36529757.569286.1248
 9777.62279.99259787.646278.17229817.668274.96789827.668273.45069847.668269.0253
9857.673264.15729867.696260.70349877.719259.74319887.742255.0195 9907.87243.2859
9928.105233.45579938.222226.35899948.424219.82699969.104208.19199979.444206.4591
9989.784205.661610000.14207.003110010.71206.378210021.32206.715610031.93210.0939
10042.54215.624210053.14223.712110063.75227.734610074.29228.881610108.18229.5318
#Mann= 3 , 0 , 0
9698.027  0.0627       09698.027  0.0627       010108.18  0.0627       0
#XS Ineff= 2 , 0
       0                               0
Bank Sta=9698.027,10108.18
Exp/Cntr=0.3,0.1