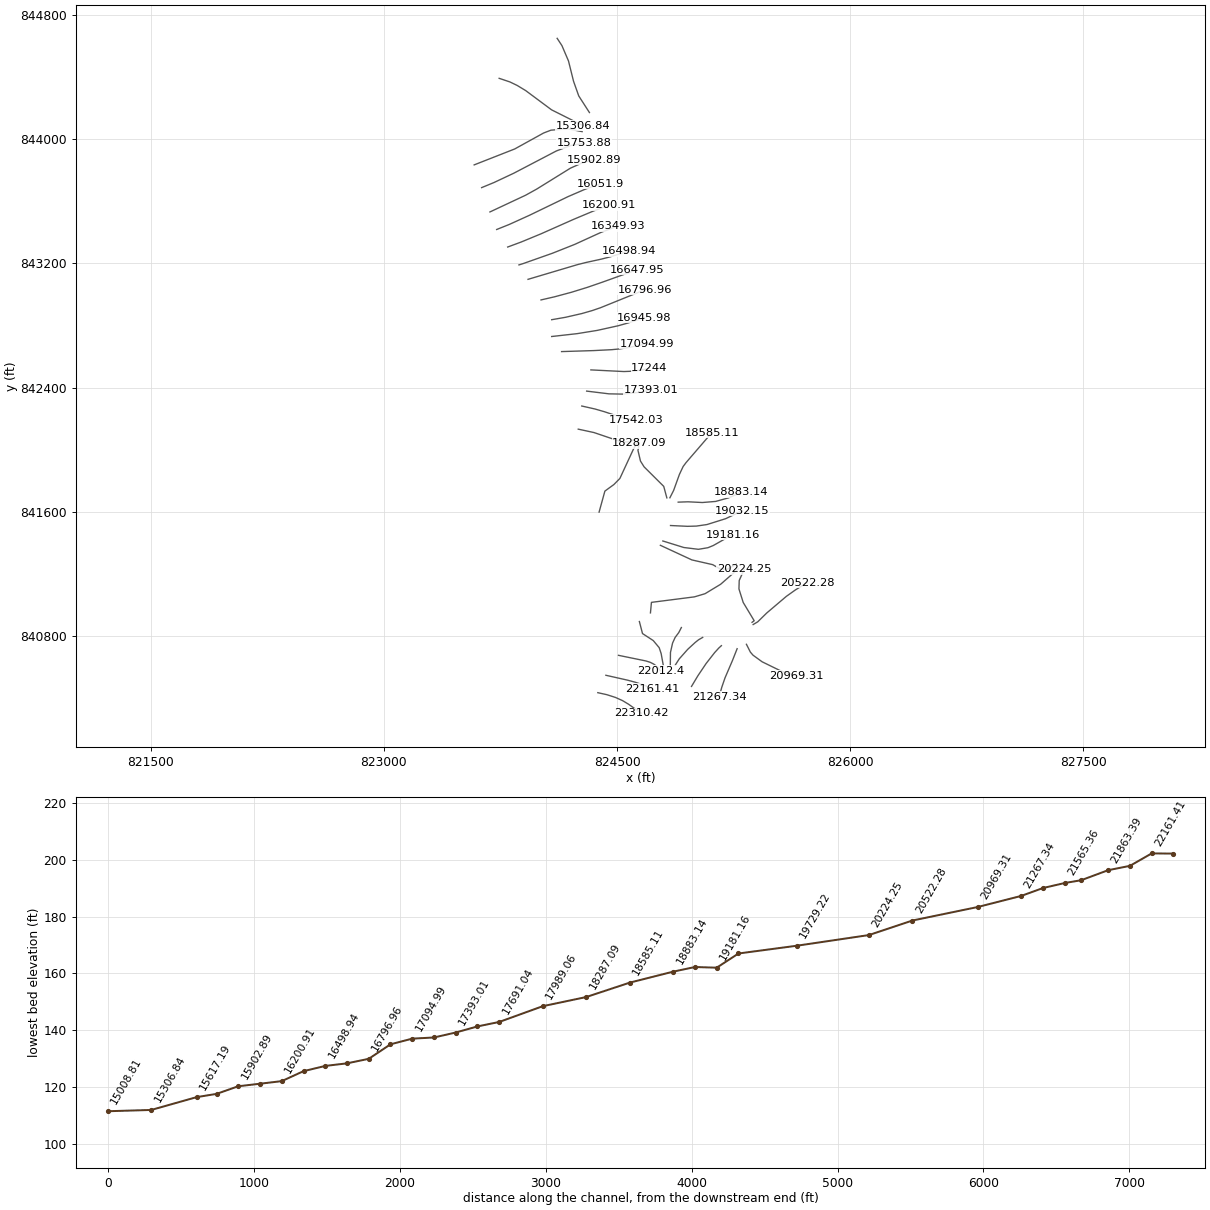
HEC-RAS study 18370_ras.prj: 18370

--- 18370_ras.g01 (geometry) --- (continued)

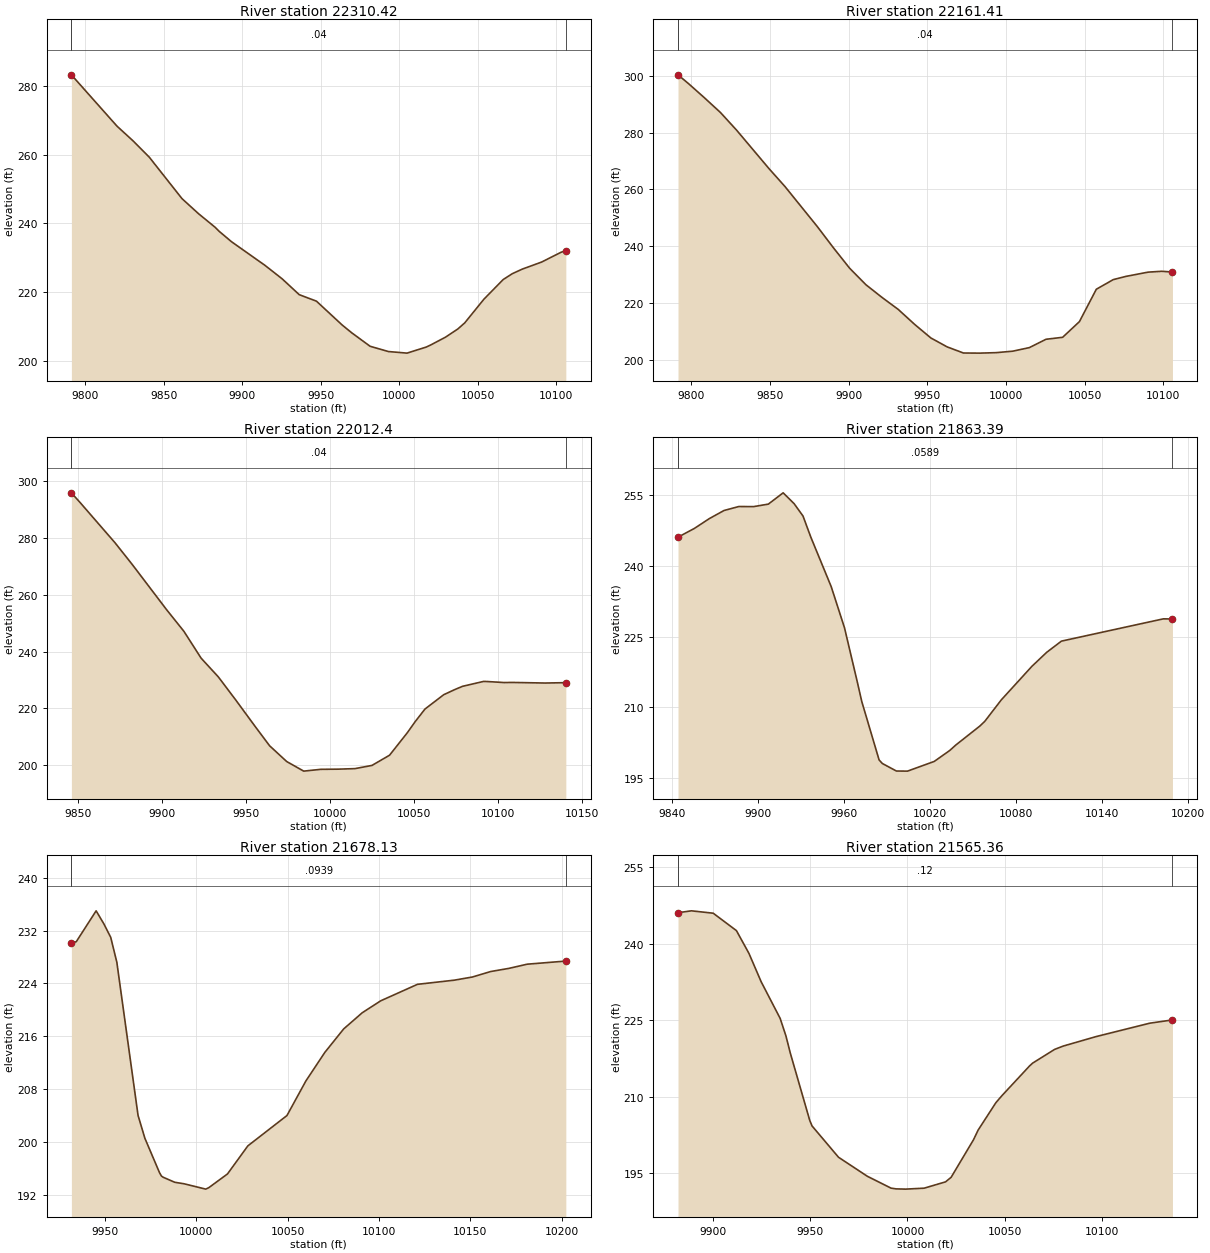
Type RM Length L Ch R = 1 ,22310.42,149.012400,149.012400,149.012400
XS GIS Cut Line= 6
824376.534314394840438.461439844824434.560665484 840425.58810226
824490.350060452840407.694814673824536.222251143840387.104789386
824574.550870015840363.964307696824657.586433247 840305.31857927
#Sta/Elev= 30
  9791.3283.20669820.384268.25599830.657 263.956 9840.93259.22859861.715247.1955
9872.217242.82239882.718238.89789885.421 237.671 9893.22234.66759914.437227.8212
9925.398223.8942 9936.36219.25689947.321217.36729963.736210.41319969.837208.1418
9981.475204.24729993.113202.718310004.95 202.25610017.19204.019810019.94204.6069
10029.44206.890910037.27209.268710041.68211.042310053.92217.945410066.16223.6504
10071.94225.351410078.41226.705710090.65 228.74910102.89231.562110106.06232.0906
#Mann= 3 , 0 , 0
  9791.3    0.04       0  9791.3    0.04       010106.06    0.04       0
#XS Ineff= 2 , 0
       0                               0
Bank Sta=9791.3,10106.06
Exp/Cntr=0.3,0.1

Type RM Length L Ch R = 1 ,22161.41,149.012500,149.012500,149.012500
XS GIS Cut Line= 6
824428.532326046840550.355895312 824566.36108326840519.347169211
824617.643748178840505.500917444 824670.22689985840487.952832363
824699.305616855840476.469523171824728.915157171840461.971250864
#Sta/Elev= 30
9791.677300.34059798.275297.27599808.476292.25099818.677 287.0539828.879280.8598
9849.359267.38579859.635260.99049880.188246.88219890.464239.3807 9900.74 232.199
9911.017226.42559921.293221.93059931.569217.72049941.916212.48079952.275207.6697
9962.633204.52189972.991202.36419983.349 202.3229993.793202.4907 10004.3203.0071
10014.87204.266610025.44207.2019   10036207.895310046.66213.410410057.41 224.824
10068.16228.214810076.13229.338210090.26230.844910098.87231.143610105.76230.9001
#Mann= 3 , 0 , 0
9791.677    0.04       09791.677    0.04       010105.76    0.04       0
#XS Ineff= 2 , 0
       0                               0
Bank Sta=9791.677,10105.76
Exp/Cntr=0.3,0.1

Type RM Length L Ch R = 1 , 22012.4,149.012400,149.012400,149.012400
XS GIS Cut Line= 6
824509.658575562840678.646497154824686.175253734840642.473773615
824713.555897005840633.710188078824735.901125076840622.478052062
824756.801832784840606.838127784824778.593828724840580.334603139
#Sta/Elev= 30
9845.921295.85229851.399292.2426 9871.91278.28019882.166270.64629902.677 254.698
9912.933247.13389923.188 237.6839933.444231.08999943.682 223.0739955.285213.7271
9963.998206.84659974.157201.31289984.315 197.9299994.473198.560410004.62198.6188
10014.79198.807310024.96199.935710035.42203.519510045.92211.360310050.67215.3153
10056.52219.762210067.71224.8204 10074.3226.6253 10078.9227.764210091.28229.4721
10092.39229.493310103.77229.096610108.52 229.13610128.07228.925910140.44229.0562
#Mann= 3 , 0 , 0
9845.921    0.04       09845.921    0.04       010140.44    0.04       0
#XS Ineff= 2 , 0
       0                               0
Bank Sta=9845.921,10140.44
Exp/Cntr=0.3,0.1

Type RM Length L Ch R = 1 ,21863.39,185.258100,185.258100,185.258100
XS GIS Cut Line= 6
824643.933294654840896.033787757824663.966225594840818.759738788
824733.194384933840773.542270273824771.205432951 840728.15226008
824783.824397117840690.436814293824798.762199312840608.777249545
#Sta/Elev= 30
9843.909 246.1189855.308247.96779865.638250.03539875.969251.77549886.299 252.626
 9896.63252.6079 9906.96253.13969917.291255.53739924.938253.23329931.141250.6134
9936.546 246.1639950.831235.60439960.092 226.8699968.735215.74479972.172211.1803
9984.252198.78139986.561  198.029996.331196.430310004.06196.408510022.71198.4655
10033.49200.782910037.78201.954810054.59205.992710058.01206.990310069.52 211.544
10090.87218.670510101.23221.655710111.49224.028910182.65228.763110188.97 228.732
#Mann= 3 , 0 , 0
9843.909  0.0589       09843.909  0.0589       010188.97  0.0589       0
#XS Ineff= 2 , 0
       0                               0
Bank Sta=9843.909,10188.97
Exp/Cntr=0.3,0.1

Type RM Length L Ch R = 1 ,21678.13,112.766900,112.766900,112.766900
XS GIS Cut Line= 6
824913.966893247840857.446880322824897.316410904840825.026331421
824873.969310579840793.987387911824857.417924371840757.534847884
 824843.88469489840697.215607333824842.713297584840603.894397734
#Sta/Elev= 30
9931.487 230.0939934.152230.32379945.043235.00029949.327233.00329953.028230.9919
9956.394 227.2079968.011204.02439971.757200.56129979.738195.37629980.813194.8453
9981.738194.66819988.113193.90099993.243193.673410005.11192.864910006.86193.1037
10016.99195.159910028.17199.416410049.58204.006310059.96209.245910070.34213.5684
10080.65 217.117 10090.8 219.56310100.95221.376410121.08223.871810141.12224.4967
10151.14224.977210161.16225.807310171.18226.2877 10181.2226.920710202.36227.3934
#Mann= 3 , 0 , 0
9931.487  0.0939       09931.487  0.0939       010202.36  0.0939       0
#XS Ineff= 2 , 0
       0                               0
Bank Sta=9931.487,10202.36
Exp/Cntr=0.3,0.1

Type RM Length L Ch R = 1 ,21565.36,149.012400,149.012400,149.012400
XS GIS Cut Line= 6
825051.112285464840793.827848078825024.818783637840778.864469172
825003.246771476840761.763816939824955.067544236840717.472877732
824900.248473088840655.738117991824874.028494783840614.805413788
#Sta/Elev= 30
9881.855246.08689888.775 246.4549899.968245.98789911.932 242.5749918.362238.1199
9924.671232.5438 9934.46 225.3489937.432221.90489939.669218.55619949.685205.3475
9950.851204.27339964.492198.12459979.299 194.4049991.529192.06979994.106191.9248
    9999191.874710008.56192.059610019.59193.298510022.47194.194310033.98201.5529
10036.38203.460810045.53208.839210048.64210.214410062.87216.042410064.44216.5893
10075.78219.285110080.24219.937410097.18221.798410124.75224.419710136.41225.0563
#Mann= 3 , 0 , 0
9881.855    0.12       09881.855    0.12       010136.41    0.12       0
#XS Ineff= 2 , 0
       0                               0
Bank Sta=9881.855,10136.41
Exp/Cntr=0.3,0.1

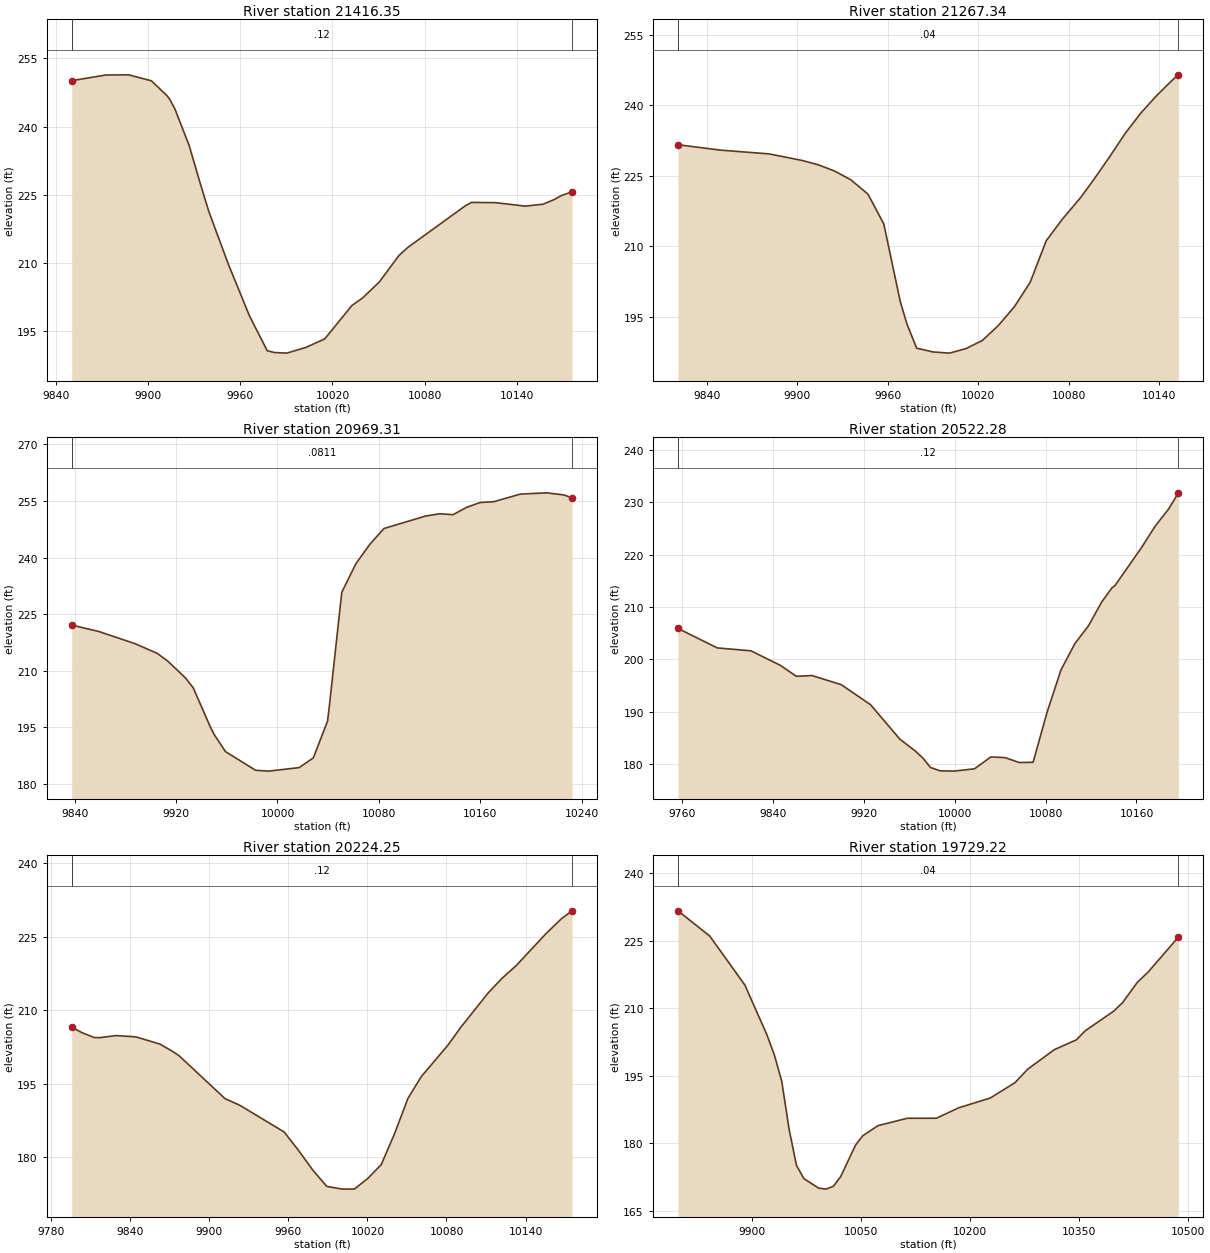
Type RM Length L Ch R = 1 ,21416.35,149.012500,149.012500,149.012500
XS GIS Cut Line= 6
825171.472358203840740.855644976825155.307471025840726.143690293
825128.134296157840696.376282494825073.427923584840626.348353835
825020.423971382840547.503622776824979.241333795840478.728617226
#Sta/Elev= 30
9849.973250.10739872.286251.35439887.119251.39389901.952250.07649912.135246.7853
9913.884246.01329917.213243.92879926.594235.79189933.415227.90349939.304221.3749
9952.014209.77439965.819  198.359977.433190.6474 9982.02190.23949990.143 190.104
10002.66191.357110014.95193.237610032.68200.597310039.54202.227410050.52205.7715
10063.37211.620610069.04213.362610106.59222.548610110.61223.294910126.06223.2476
10145.58 222.48610157.23222.891210164.99 223.99410168.89224.7612 10176.2225.6386
#Mann= 3 , 0 , 0
9849.973    0.12       09849.973    0.12       0 10176.2    0.12       0
#XS Ineff= 2 , 0
       0                               0
Bank Sta=9849.973,10176.2
Exp/Cntr=0.3,0.1

Type RM Length L Ch R = 1 ,21267.34,298.024900,298.024900,298.024900
XS GIS Cut Line= 6
825272.665398831840721.262288131 825242.32108142840644.621841571
825204.668099844 840556.80035137825194.820691016 840533.96393891
825174.013141043840473.459750393825156.601814005840411.009161135
#Sta/Elev= 30
9821.018231.61069849.264 230.461 9881.53229.6554 9903.04228.28729913.916227.3539
9924.796226.02469935.677224.13589946.557221.21759947.403 220.8359957.437214.7739
9968.318198.3263 9972.78193.51469979.198188.38189990.078187.5748   10001187.3236
10011.87 188.28310022.74190.011510033.35 193.18710043.92197.1542 10054.5202.3989
10065.07211.196610075.65215.733610087.85220.368610096.64224.220410107.02228.9994
 10117.4234.008910127.78238.328910138.16242.018810148.54245.306510152.69246.4653
#Mann= 3 , 0 , 0
9821.018    0.04       09821.018    0.04       010152.69    0.04       0
#XS Ineff= 2 , 0
       0                               0
Bank Sta=9821.018,10152.69
Exp/Cntr=0.3,0.1

Type RM Length L Ch R = 1 ,20969.31,447.037400,447.037400,447.037400
XS GIS Cut Line= 6
825332.469435272840749.608195578825357.781112496840699.452460252
825374.823620917840679.658331841825433.658467163840636.926282718
825551.090554496840579.511282888 825654.51935224840546.268690283
#Sta/Elev= 30
9837.553222.11299859.218220.3864  9887.5217.18989905.025214.61439913.033212.6664
9927.209208.16389933.526205.46369946.738195.31669949.994193.13129958.943188.5914
9982.694183.64669992.976183.414810017.05184.343710028.28186.924410039.51196.6625
10040.75200.089910050.74 230.79610061.97238.419310073.05243.579810084.05247.6964
10117.03251.0058 10127.9251.600310138.58 251.35710149.25253.288910159.92254.5777
 10170.6254.778410191.64 256.799 10212.4 257.14310225.91256.592410232.52255.8044
#Mann= 3 , 0 , 0
9837.553  0.0811       09837.553  0.0811       010232.52  0.0811       0
#XS Ineff= 2 , 0
       0                               0
Bank Sta=9837.553,10232.52
Exp/Cntr=0.3,0.1

Type RM Length L Ch R = 1 ,20522.28,298.024900,298.024900,298.024900
XS GIS Cut Line= 6
825375.759295997840876.701902544825405.263243295840894.264471909
825463.055713391840950.912408248825589.211760033841057.969870597
825647.155258671841099.165383304825722.328464415 841145.80022495
#Sta/Elev= 30
9756.337205.90279790.901202.18579820.523201.63359846.543198.85129860.546196.7585
 9874.33196.90459900.084195.16629925.838191.34719951.666184.76139965.127 182.521
 9972.16181.09819978.588179.34959987.099178.7085    9999178.651110017.32179.0901
10031.81181.359210044.44181.229710056.71 180.29310068.98180.338310081.25189.8682
10093.52197.974210105.79203.017410117.67206.385410129.43210.967910138.47213.6711
 10141.2214.128610164.74221.445410176.41225.419210188.27228.7051 10196.9231.8056
#Mann= 3 , 0 , 0
9756.337    0.12       09756.337    0.12       0 10196.9    0.12       0
#XS Ineff= 2 , 0
       0                               0
Bank Sta=9756.337,10196.9
Exp/Cntr=0.3,0.1

Type RM Length L Ch R = 1 ,20224.25,495.030500,495.030500,495.030500
XS GIS Cut Line= 6
825368.639159305840890.942175935825382.318347368840901.294557867
825311.722353413841018.743721691825284.359166044841105.743341626
825286.066935628841160.055574949825318.356207178841231.922740905
#Sta/Elev= 30
9795.651206.55579803.628205.42139812.806204.44789817.248204.43159829.234204.8481
9844.219204.58829862.357203.13959871.834201.68919877.032200.7601    9912191.9804
9923.257190.62239956.766185.19659967.624181.47089978.482177.44919989.146174.0845
   10001173.524210010.12173.543310020.37175.721510030.56178.547910040.75 184.935
10050.78192.0454 10060.8196.445610080.89202.823710090.95206.562110111.64213.5507
10122.08216.512810132.92 219.13410155.46225.635910167.18228.6739 10175.3230.2968
#Mann= 3 , 0 , 0
9795.651    0.12       09795.651    0.12       0 10175.3    0.12       0
#XS Ineff= 2 , 0
       0                               0
Bank Sta=9795.651,10175.3
Exp/Cntr=0.3,0.1

Type RM Length L Ch R = 1 ,19729.22,399.044300,399.044300,399.044300
XS GIS Cut Line= 6
 824715.11317569840951.529989094824721.532652915841019.339401722
824997.899591446841054.710424647825066.120772332841074.973527208
825166.493110955841135.681139529825280.111132801841234.942088902
#Sta/Elev= 30
9798.518231.60659842.182226.00599890.437215.1308 9920.87204.03029931.015199.5891
9941.159193.76159951.304183.06859961.448175.03739971.593172.10149991.882169.9822
10002.03 169.75410012.17170.385910022.31172.5523 10042.6179.535610052.75181.6343
10073.57183.864610113.67185.498610153.85 185.51110184.71187.837410228.09190.0135
10262.08193.437810279.48196.421410315.97200.750810346.15 202.91710358.72204.9688
10397.55209.296610409.82211.189510429.93215.672410444.99218.0011 10486.6225.7587
#Mann= 3 , 0 , 0
9798.518    0.04       09798.518    0.04       0 10486.6    0.04       0
#XS Ineff= 2 , 0
       0                               0
Bank Sta=9798.518,10486.6
Exp/Cntr=0.3,0.1

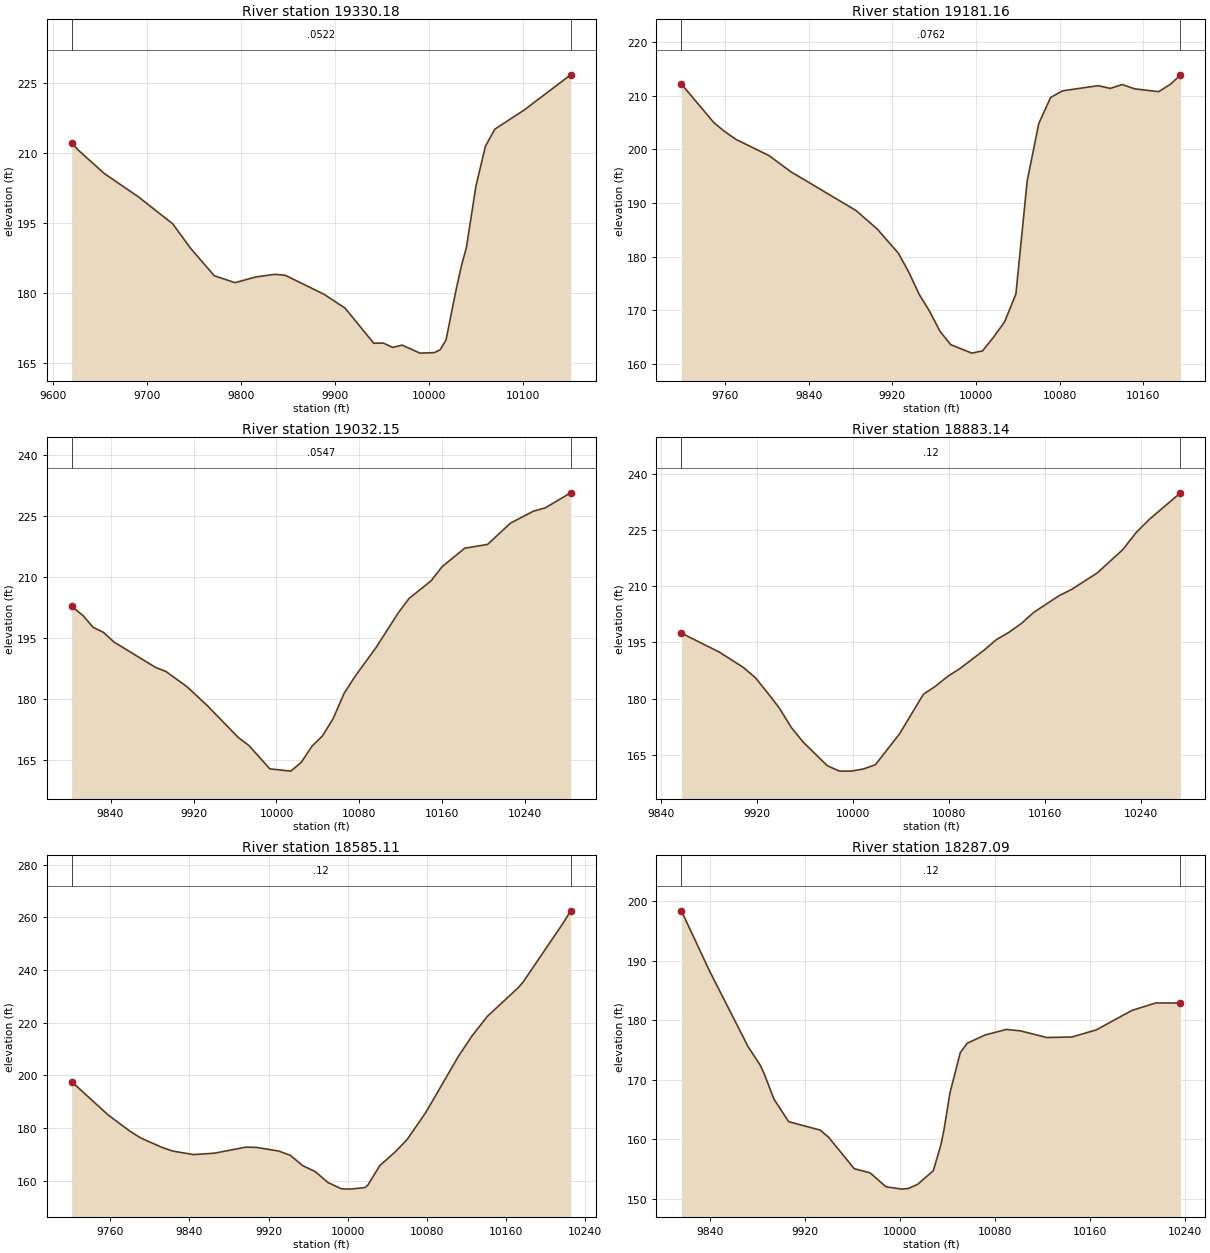
Type RM Length L Ch R = 1 ,19330.18,149.012500,149.012500,149.012500
XS GIS Cut Line= 6
824778.994428648841386.316837778824981.871970495841292.254913048
825115.595495612841261.851103858825166.680828072841232.532667941
 825211.05453303841233.143149177825267.174949156841263.747120338
#Sta/Elev= 30
9619.783212.29199626.088210.80699654.513205.63379690.842200.61399727.384194.7993
9746.244 189.5659771.493183.65489793.548182.16529815.602183.39569836.001183.9615
9847.075183.74719888.556179.63069910.565176.69499941.106169.14069951.144169.1936
9961.183168.24899971.221168.74819990.186167.019510005.46 167.123 10011.7167.7424
10017.87169.826310028.78180.808910034.53186.006810039.51189.645910049.68202.8934
10059.73211.449110065.12213.4635 10069.8215.161910100.74219.246210150.44226.8478
#Mann= 3 , 0 , 0
9619.783  0.0522       09619.783  0.0522       010150.44  0.0522       0
#XS Ineff= 2 , 0
       0                               0
Bank Sta=9619.783,10150.44
Exp/Cntr=0.3,0.1

Type RM Length L Ch R = 1 ,19181.16,149.012400,149.012400,149.012400
XS GIS Cut Line= 6
824794.919026473841414.112499433824930.138044884 841372.10665318
825023.727673351841360.610360554825084.966420784841370.902519904
 825119.35641123841384.992493834825242.918801095841454.910654003
#Sta/Elev= 30
9718.109212.14929749.334204.91869759.834203.25559770.333201.83459801.832198.8298
 9822.83 195.8099885.168188.59199905.597185.12629925.699180.64919935.707177.1207
9945.708172.95119955.717169.78599965.793166.03119975.868163.58949996.092162.0116
10006.34 162.42410016.62164.922410027.46167.840610038.27173.030510049.07194.0961
10060.19204.809510071.55209.652210082.91210.883610116.99211.840910128.55211.3343
10140.15212.051610151.76 211.26110174.98210.724210186.59212.160910195.78 213.864
#Mann= 3 , 0 , 0
9718.109  0.0762       09718.109  0.0762       010195.78  0.0762       0
#XS Ineff= 2 , 0
       0                               0
Bank Sta=9718.109,10195.78
Exp/Cntr=0.3,0.1

Type RM Length L Ch R = 1 ,19032.15,149.012500,149.012500,149.012500
XS GIS Cut Line= 6
824844.191084722841513.600460339824953.764381405841508.413062132
825010.145155396841509.930574668825078.668794419841519.863521016
825199.036651107841557.599626826825306.700176208841609.524039221
#Sta/Elev= 30
9802.458202.76379813.279200.57039823.291197.60699833.302196.35839843.313194.0056
9883.358187.77549893.369186.76719913.391183.08379933.398178.33799963.409170.4677
9973.438168.55489993.553162.814910013.79162.249810023.95164.417710034.11168.3492
 10044.4 170.91910054.76175.244310065.13181.332410075.49185.443810096.22 192.729
10117.15201.077510127.81204.704910149.13209.0746 10159.8212.559310181.62217.1014
10203.56218.012710225.51223.232110247.83226.208610259.14227.003510283.69230.7093
#Mann= 3 , 0 , 0
9802.458  0.0547       09802.458  0.0547       010283.69  0.0547       0
#XS Ineff= 2 , 0
       0                               0
Bank Sta=9802.458,10283.69
Exp/Cntr=0.3,0.1

Type RM Length L Ch R = 1 ,18883.14,298.024900,298.024900,298.024900
XS GIS Cut Line= 6
824893.501790429841663.931901452824956.341438676841666.158796035
825048.934577182841661.564483567825134.404125426841668.550486286
825218.252822228841691.696272209825298.463410805841726.669147309
#Sta/Elev= 30
9857.059197.45389888.685192.39619908.686 188.3139918.686185.57229928.698 181.615
9938.713177.46869948.727172.26359958.742168.3285 9978.77162.05959988.785160.6341
9998.799160.6231 10008.8 161.19710018.81162.332410038.83 170.51810058.84181.1395
10068.89183.2868   10079185.8868 10089.1187.964110109.43192.905710119.66195.7212
10129.98197.635610140.43200.017810150.88203.009610171.79207.420410182.25209.1039
10203.69213.495710225.24219.799510236.15224.275410247.22227.8272 10273.2234.9156
#Mann= 3 , 0 , 0
9857.059    0.12       09857.059    0.12       0 10273.2    0.12       0
#XS Ineff= 2 , 0
       0                               0
Bank Sta=9857.059,10273.2
Exp/Cntr=0.3,0.1

Type RM Length L Ch R = 1 ,18585.11,298.024900,298.024900,298.024900
XS GIS Cut Line= 6
824840.160038553841692.102168546824864.138407445841739.134788587
824901.396600127841842.243743775824925.301856758841893.058325815
824944.208526068841918.419459449825110.000465191842110.872820838
#Sta/Elev= 30
9720.931197.56159757.948184.88129780.079178.69599790.884 176.1479812.494172.5582
9823.049 171.1999844.145169.8565 9865.24170.38439897.165172.69959907.933172.5795
9930.497 171.1859942.111169.54559954.584 165.6469967.057163.42589980.149 159.224
9993.563156.879410002.33156.7361 10017.4157.309710020.49158.311610032.46165.6843
10047.83170.805310060.07175.579610078.98185.883210112.24207.378410125.28214.7201
10141.28 222.40510172.43233.273610177.46235.469910217.43257.596210225.39262.4503
#Mann= 3 , 0 , 0
9720.931    0.12       09720.931    0.12       010225.39    0.12       0
#XS Ineff= 2 , 0
       0                               0
Bank Sta=9720.931,10225.39
Exp/Cntr=0.3,0.1

Type RM Length L Ch R = 1 ,18287.09,298.025000,298.025000,298.025000
XS GIS Cut Line= 6
 824820.58208694841691.394531742824800.642659662841765.302809423
824674.136084524841891.100864675824650.960724064841928.197381269
824634.842149585841996.374758115824643.780995196842044.772844551
#Sta/Elev= 30
9815.552198.35259839.251188.26949871.864175.54549882.023172.46759885.215171.1116
9893.573166.77779906.036 162.976 9932.56161.57129939.689160.37359961.375155.0852
9974.762154.39089988.149152.055610001.48151.662810007.09151.784610014.76152.4585
10028.05154.752410034.49159.128510037.16161.744710042.07167.7776 10050.8174.5583
10056.78176.152410071.49177.504110089.72178.459210101.56178.214910123.76177.0967
10144.92177.185110165.53178.376110195.69181.651710215.92182.903810236.54182.8876
#Mann= 3 , 0 , 0
9815.552    0.12       09815.552    0.12       010236.54    0.12       0
#XS Ineff= 2 , 0
       0                               0
Bank Sta=9815.552,10236.54
Exp/Cntr=0.3,0.1

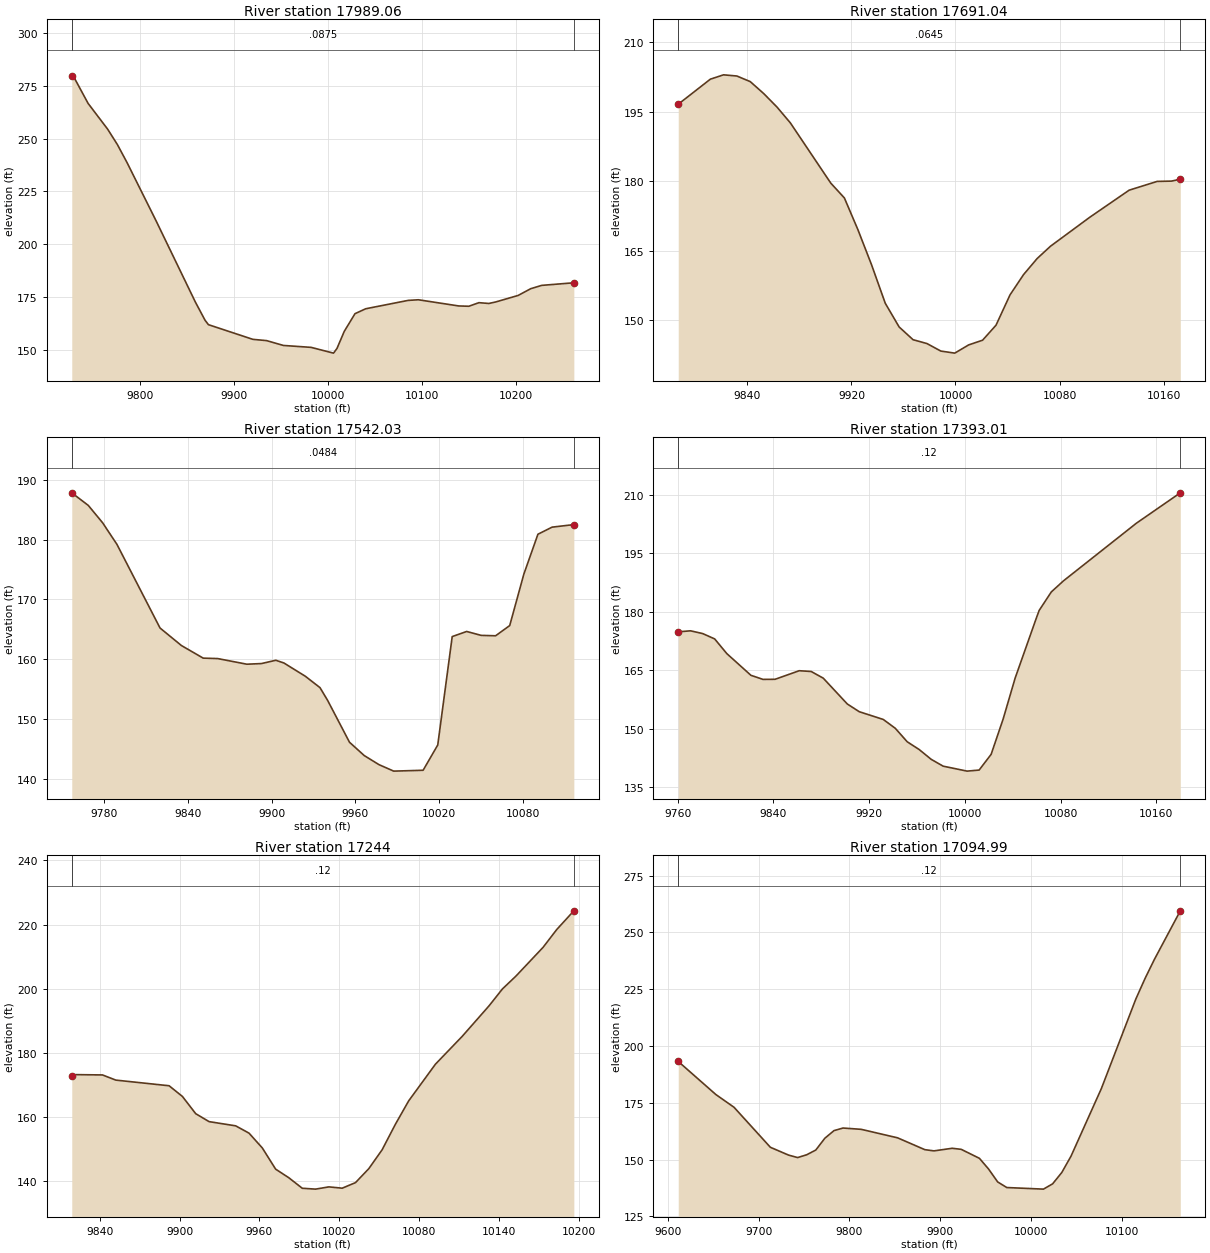
Type RM Length L Ch R = 1 ,17989.06,298.024900,298.024900,298.024900
XS GIS Cut Line= 6
824384.778253513841599.872797434824422.042753756841734.996508107
824480.126786262841777.315474659824518.469405025841816.347025827
824606.647477329842006.762623772824635.496992588842053.902153596
#Sta/Elev= 30
 9727.04 279.7629727.947280.1457 9744.42266.6217 9765.14254.4666  9775.5247.1965
 9785.86 238.598 9816.94210.8522 9858.38172.72919868.742164.05269872.395161.9012
9919.688 154.9519934.258154.35779952.185152.06369981.591151.157910005.48148.4311
10009.13150.6215 10016.9158.723110028.31167.095110039.73169.429610084.85 173.385
10095.77173.681410138.74170.755910149.43170.610710160.12172.309610170.82171.9391
10178.03172.648410201.88175.733910215.34178.941410226.91180.494510261.12181.7284
#Mann= 3 , 0 , 0
 9727.04  0.0875       0 9727.04  0.0875       010261.12  0.0875       0
#XS Ineff= 2 , 0
       0                               0
Bank Sta=9727.04,10261.12
Exp/Cntr=0.3,0.1

Type RM Length L Ch R = 1 ,17691.04,149.012400,149.012400,149.012400
XS GIS Cut Line= 6
824250.694110639842133.466338427824352.140036562842111.496523745
824518.321778614842055.107265488824557.832231367842050.674816415
824579.765953209 842052.95628947824620.861869267842070.030656785
#Sta/Elev= 30
9786.811196.63229811.493 202.0419821.648202.98369831.892202.72699842.176201.5195
9852.459198.95679862.743196.02479873.027192.60199904.105 179.5949914.566176.3927
9925.026169.49999935.486161.93819946.004153.64379956.686148.51839967.368145.7724
 9978.05144.94249988.732143.31949999.418142.873710010.13144.647810020.83145.6656
10031.15148.899510041.94155.460210052.36159.842310062.78163.300610073.02165.9568
10103.24172.216610133.53178.068710155.07179.963110166.08 180.02710172.87180.4367
#Mann= 3 , 0 , 0
9786.811  0.0645       09786.811  0.0645       010172.87  0.0645       0
#XS Ineff= 2 , 0
       0                               0
Bank Sta=9786.811,10172.87
Exp/Cntr=0.3,0.1

Type RM Length L Ch R = 1 ,17542.03,149.012500,149.012500,149.012500
XS GIS Cut Line= 6
824273.349808004842282.275034881824359.420353692842262.772605572
824418.649263659842245.613475062824524.189011957842210.437325165
824564.872133572842199.466966431824620.552822584842193.057191805
#Sta/Elev= 30
9757.007187.8125 9768.85185.70629779.113182.80029789.383179.18529820.193 165.219
9835.495162.29329851.082160.18419861.493160.10819882.316 159.1699892.727 159.273
9903.138 159.8269908.861159.37459924.189157.1609 9934.74155.2481 9940.22153.1068
9955.841 146.1269966.392143.89949976.943 142.3829987.494141.297110008.55141.4408
10019.03145.667310029.38163.786510039.74164.6386 10050.1163.986710060.45163.9189
10070.55165.628410080.65174.211310090.75180.891110100.86182.075110116.46182.5012
#Mann= 3 , 0 , 0
9757.007  0.0484       09757.007  0.0484       010116.46  0.0484       0
#XS Ineff= 2 , 0
       0                               0
Bank Sta=9757.007,10116.46
Exp/Cntr=0.3,0.1

Type RM Length L Ch R = 1 ,17393.01,149.012500,149.012500,149.012500
XS GIS Cut Line= 6
 824304.81696443842378.136030646824448.383474428842360.546574725
824534.929116747  842358.8797384824647.717898661842370.801908693
824695.046351012842380.594132081824720.377590857842388.274614657
#Sta/Elev= 30
9760.447174.88559770.722175.14899780.812174.44769790.902173.06999800.992169.3175
9821.172163.73669831.262162.68679841.352162.70759861.506164.90859871.556164.7115
9881.606163.00559901.705156.37969911.732154.39349931.761152.40949941.776150.1475
9951.781146.67769961.781144.68999971.782142.18239981.783140.424310001.83139.1499
10011.86139.4229 10021.9143.461710031.94 152.52610041.98163.0466 10059.8178.5223
10062.07180.400910072.15185.113610082.24187.944210143.23202.748610179.96210.5515
#Mann= 3 , 0 , 0
9760.447    0.12       09760.447    0.12       010179.96    0.12       0
#XS Ineff= 2 , 0
       0                               0
Bank Sta=9760.447,10179.96
Exp/Cntr=0.3,0.1

Type RM Length L Ch R = 1 ,   17244,149.012400,149.012400,149.012400
XS GIS Cut Line= 6
824331.927609339842514.536462871824544.154234639842503.941562771
824585.463749461842505.511203647824628.000130227842509.721078789
824663.665097289842515.105739007824707.623058925  842524.2110733
#Sta/Elev= 30
9818.941172.84329822.018173.1326 9842.05173.04059852.066171.42639892.131169.6633
9902.147166.32379912.163160.9421 9922.18158.46749942.207157.1482 9952.22154.8744
9962.234 150.2429972.247143.6369 9982.26140.91799992.273137.665910002.28137.3947
10012.29138.096910022.29137.687310032.29139.4217 10042.3143.779910052.31149.6666
10062.31157.650810072.32164.963910092.42176.400210112.51185.069810132.72194.6074
10142.83199.902910152.96 203.89910173.39212.8888 10183.6218.416710196.49224.2698
#Mann= 3 , 0 , 0
9818.941    0.12       09818.941    0.12       010196.49    0.12       0
#XS Ineff= 2 , 0
       0                               0
Bank Sta=9818.941,10196.49
Exp/Cntr=0.3,0.1

Type RM Length L Ch R = 1 ,17094.99,149.012500,149.012500,149.012500
XS GIS Cut Line= 6
 824143.58252627842632.290602356824350.307319129842638.791049683
824465.648973584842644.569495155824515.068892912842649.213667373
824572.491964183842658.066599759824692.688327504842683.383868587
#Sta/Elev= 30
9611.425193.19989652.863178.63779672.873173.01899712.893155.40969732.903151.9757
9742.908150.88239752.913 152.1159762.918154.19869772.923159.40099782.928162.7388
9792.932163.88779812.942163.31139852.988159.57239883.026154.35839893.039153.8248
9913.064154.96779923.076154.50949943.131150.54549953.175145.85049963.219140.1556
9973.263137.686310013.65136.986310023.77139.321710033.89144.340610044.03151.5246
10077.45181.292710115.37220.672210125.56229.759510135.75238.072110164.36259.5138
#Mann= 3 , 0 , 0
9611.425    0.12       09611.425    0.12       010164.36    0.12       0
#XS Ineff= 2 , 0
       09904.161                       0
Bank Sta=9611.425,10164.36
Exp/Cntr=0.3,0.1

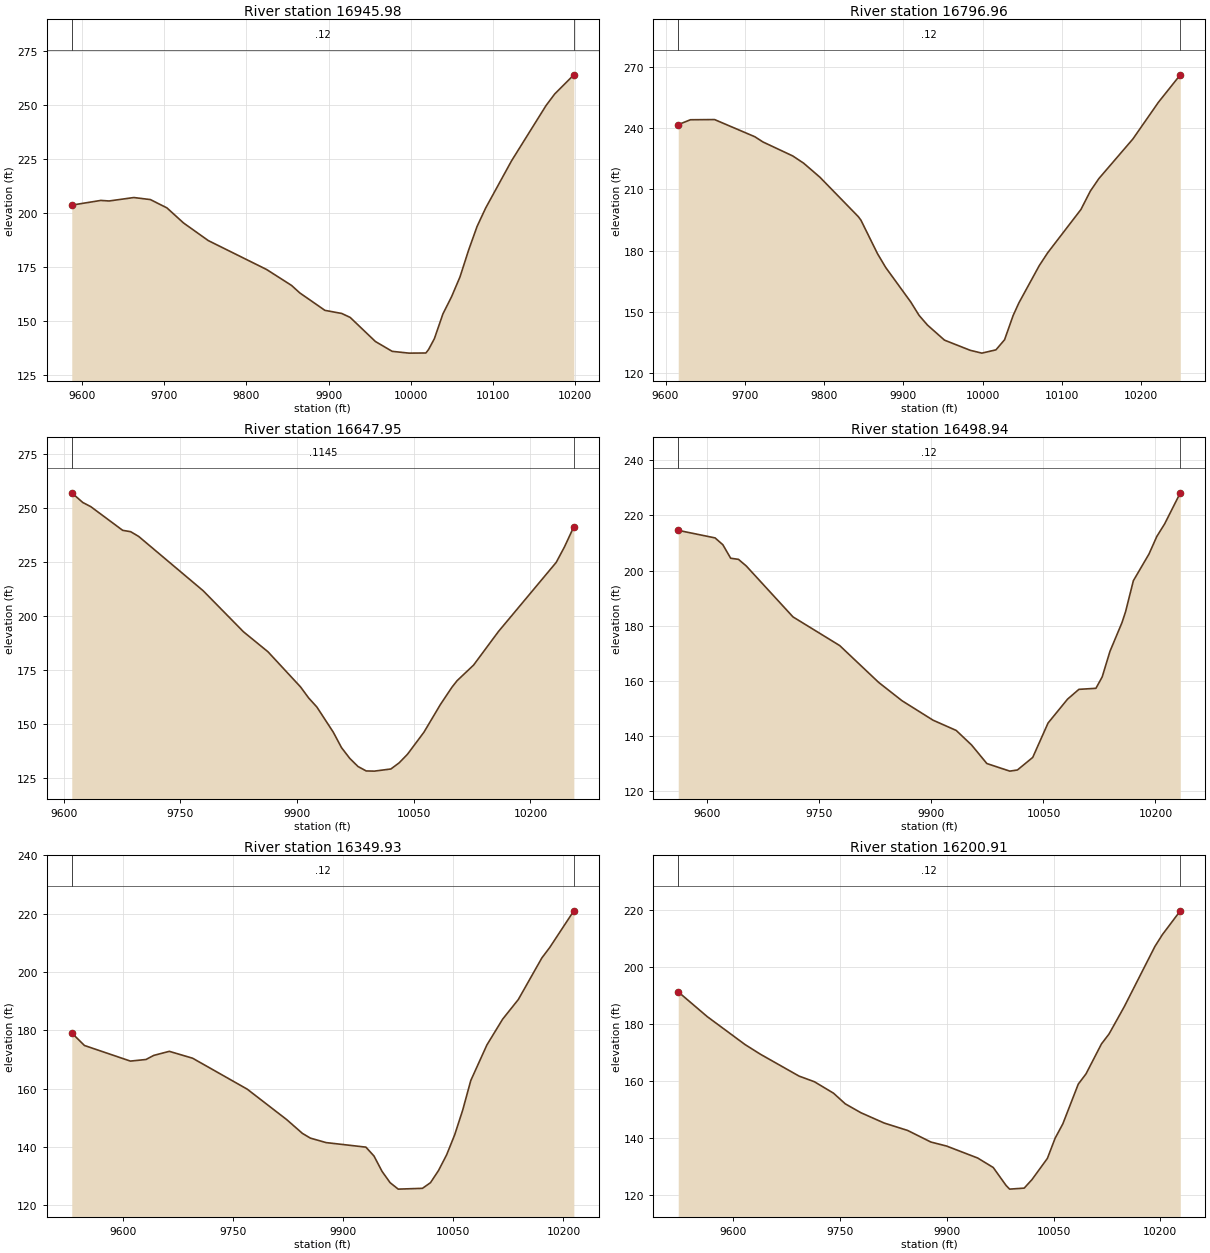
Type RM Length L Ch R = 1 ,16945.98,149.012500,149.012500,149.012500
XS GIS Cut Line= 6
824079.849942178842729.303520041824243.257660624842747.662224218
824373.051152546842768.668798733824508.184568068842798.615940314
824571.352515597842816.339038957824676.946736329842851.156090189
#Sta/Elev= 30
9587.457 203.549 9622.79205.71959632.856205.46749663.055207.06199683.187206.1096
 9703.32202.26099723.452195.29519753.662187.11379824.573 173.7379854.963166.3526
9865.093162.85789895.608154.80029916.076153.3604 9926.31151.53949957.012 140.386
 9977.48135.81489997.948134.987810018.52135.0499 10021.8136.672910028.87141.7121
10039.26153.180810049.65161.024110060.03170.302110070.42182.608310080.81193.6793
10091.23202.177510122.74224.053210164.74249.666410175.33255.0471 10198.6263.9029
#Mann= 3 , 0 , 0
9587.457    0.12       09587.457    0.12       0 10198.6    0.12       0
#XS Ineff= 2 , 0
       0                               0
Bank Sta=9587.457,10198.6
Exp/Cntr=0.3,0.1

Type RM Length L Ch R = 1 ,16796.96,149.012400,149.012400,149.012400
XS GIS Cut Line= 6
824079.849942178842837.352467605824169.135264466 842852.97908566
 824273.66124839842876.907189137824340.482803579842896.103663666
824393.714780967842914.391552513824680.736826843843030.507877117
#Sta/Elev= 30
9615.989241.7067 9631.37244.08759661.826244.18399712.648 235.7729722.907233.2103
9760.502 226.367  9774.2222.82999794.718215.96299843.172196.65979846.468194.9324
9867.277178.59739877.681171.7991 9909.31154.89239919.883148.29829930.457143.5751
9951.862136.22289984.266131.2585    9999129.869510016.76131.476810027.62136.4071
10038.47148.3065 10045.7154.456810071.39172.6958 10081.9178.912910123.98200.1853
10135.84209.181610146.57215.2804 10189.5234.6837 10221.7 252.64110249.32266.0792
#Mann= 3 , 0 , 0
9615.989    0.12       09615.989    0.12       010249.32    0.12       0
#XS Ineff= 2 , 0
       0                               0
Bank Sta=9615.989,10249.32
Exp/Cntr=0.3,0.1

Type RM Length L Ch R = 1 ,16647.95,149.012500,149.012500,149.012500
XS GIS Cut Line= 6
 824011.22398744842964.568549011824098.218604019842984.663066495
824207.458010454843014.037285915824309.910248712 843045.71109597
824404.342234092843078.244145471 824626.30991937843157.975223196
#Sta/Elev= 30
9610.385257.12829624.523252.65719634.787250.7342 9675.84239.75799686.103239.1281
9696.366236.94919779.179211.82899831.151192.77499862.552183.5519 9904.42167.2742
9914.887162.15199925.406157.97879946.545146.30339957.115139.15819967.685134.1974
9978.254130.43529988.824128.35929999.395128.2764 10020.6129.267810031.23132.1178
10041.86136.055910063.11 146.31910084.36159.193710099.05167.111210105.61170.1192
10126.86 177.36710158.74192.862110233.12224.936110243.74232.115910255.76241.4292
#Mann= 3 , 0 , 0
9610.385  0.1145       09610.385  0.1145       010255.76  0.1145       0
#XS Ineff= 2 , 0
       0                               0
Bank Sta=9610.385,10255.76
Exp/Cntr=0.3,0.1

Type RM Length L Ch R = 1 ,16498.94,149.012400,149.012400,149.012400
XS GIS Cut Line= 6
823927.690041054843097.099039051824246.954457463843191.962592262
824301.340327082843205.622655698824399.103687005 843226.99283126
824453.412959026843240.952122265824574.976964166843278.196559847
#Sta/Elev= 30
9560.829214.59859610.183 211.8579620.615209.37299631.047204.49489641.479204.0917
9651.912201.69529714.504183.24399777.097172.84859829.257159.50599860.554152.8662
9902.184145.80249933.116142.10619953.709136.82739974.177130.111310004.88127.3602
10015.12127.7781 10035.6132.327410056.12144.7847 10082.2153.425210097.42156.9846
10120.24157.374210128.64161.497310139.08170.792910155.13181.159310159.96185.1232
10170.39196.358510191.29206.011210201.79212.385110212.29216.952310233.26 228.193
#Mann= 3 , 0 , 0
9560.829    0.12       09560.829    0.12       010233.26    0.12       0
#XS Ineff= 2 , 0
       0                               0
Bank Sta=9560.829,10233.26
Exp/Cntr=0.3,0.1

Type RM Length L Ch R = 1 ,16349.93,149.012500,149.012500,149.012500
XS GIS Cut Line= 6
823869.350861991843189.787454395823895.581646802 843198.09599236
824085.106216296843265.003076826824228.075114742843321.826605943
824395.810134946843398.439508082824505.814762285843440.173837853
#Sta/Elev= 30
9529.788 179.108 9547.05174.8049 9609.71169.4478 9630.92 169.9959641.525171.3984
9662.734172.79889694.549170.43279768.937 159.8269822.742149.37819844.264144.6295
9855.024143.02179876.546141.4811 9930.77139.92139941.779136.87619952.788131.5976
9963.796127.71969974.805 125.51610007.84125.790910018.81127.732610029.79131.9235
10040.77137.274410051.75 144.14210062.72152.6457 10073.7 162.77710095.65174.9702
 10117.1183.820410138.52190.583310170.65204.863910181.36208.438210214.21221.0097
#Mann= 3 , 0 , 0
9529.788    0.12       09529.788    0.12       010214.21    0.12       0
#XS Ineff= 2 , 0
       0                               0
Bank Sta=9529.788,10214.21
Exp/Cntr=0.3,0.1

Type RM Length L Ch R = 1 ,16200.91,149.012500,149.012500,149.012500
XS GIS Cut Line= 6
823796.927903406843304.851968047  823884.1163529843337.227309402
 824011.48936373 843389.87918112824221.459754865843483.098703763
824344.327132511843534.661704688824448.595434797843574.181007429
#Sta/Elev= 30
9522.811191.35549563.423182.68449616.772172.81579638.413169.40949692.517161.7465
9714.158159.7526 9740.87155.75029757.483151.98549779.366 148.8739812.189145.2326
9845.013142.63779877.837138.55069899.719137.15379943.484132.94069965.367129.5983
9983.376123.29239988.369122.000110008.85122.3573 10019.7125.3344 10041.4132.8005
10052.25139.8852 10063.1144.9472 10084.8158.922910095.65162.513710117.35173.0465
 10128.1  176.5810149.59186.231810192.51207.349110203.12211.536910228.15219.8536
#Mann= 3 , 0 , 0
9522.811    0.12       09522.811    0.12       010228.15    0.12       0
#XS Ineff= 2 , 0
       0                               0
Bank Sta=9522.811,10228.15
Exp/Cntr=0.3,0.1

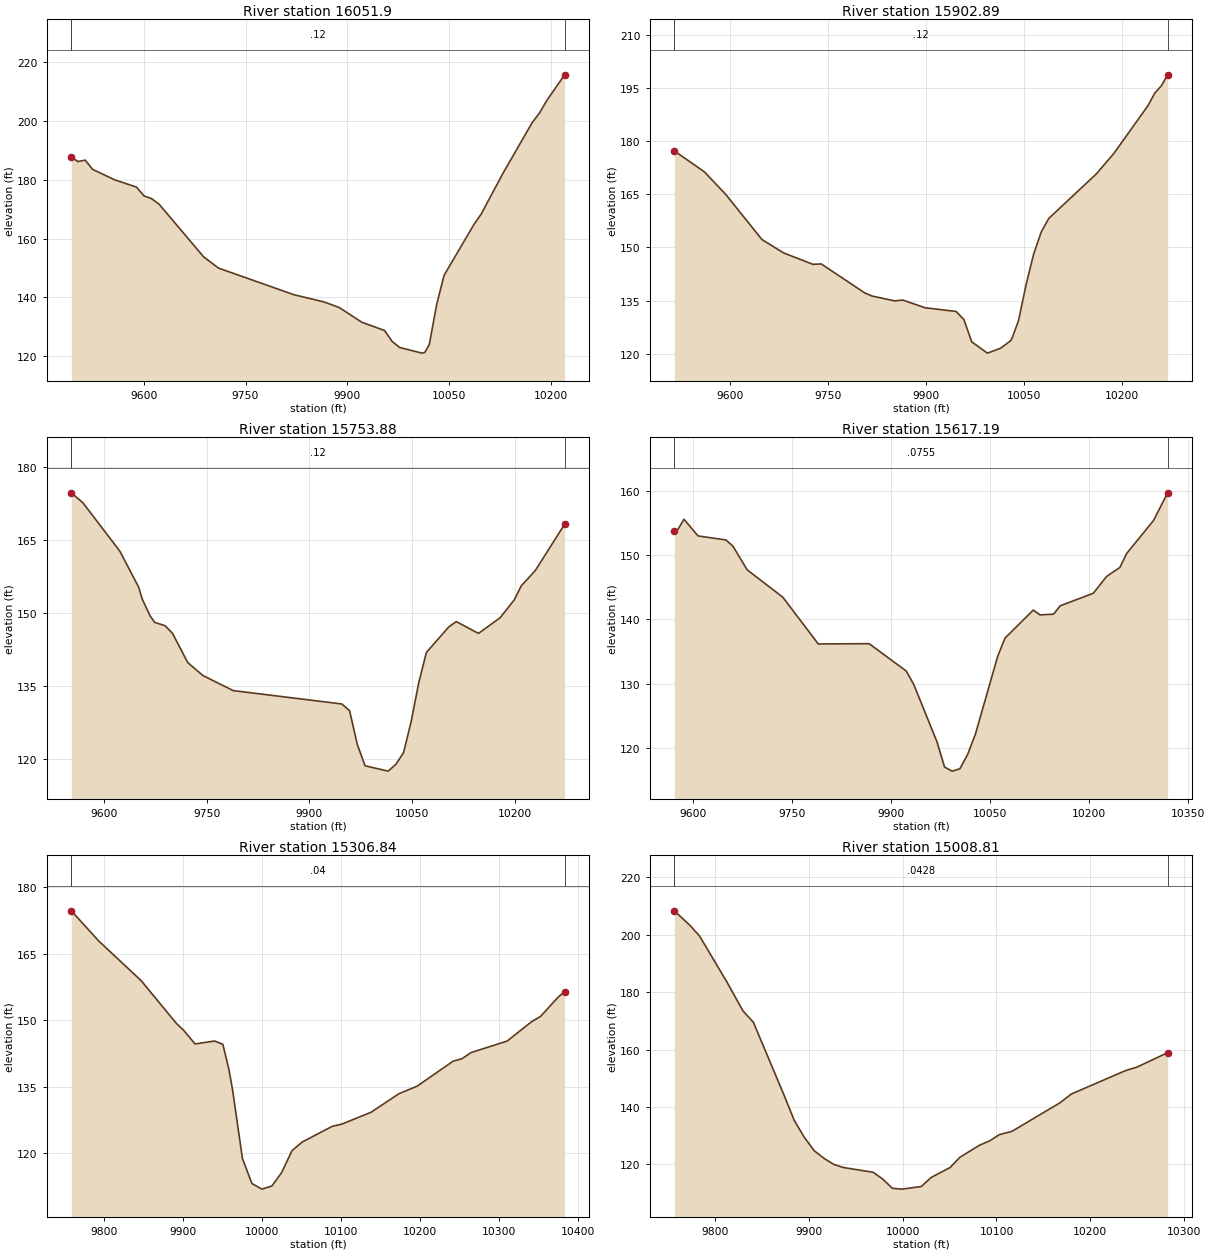
Type RM Length L Ch R = 1 , 16051.9,149.012400,149.012400,149.012400
XS GIS Cut Line= 6
823725.990866581843417.555671426 823807.49206773843450.283690259
823936.698109016 843508.89630918824185.110833383843629.022960709
824293.066006115843675.720785439824390.034171442843711.330979188
#Sta/Elev= 30
 9493.35187.71469503.059186.15589513.835186.63899524.611183.51549556.939 179.978
9589.421177.46859600.402174.48619611.383173.58569622.364171.74359688.249153.7925
9710.211149.95669821.295140.92199865.796138.46359888.046136.57019921.422131.5511
9954.798128.77629965.918125.05499976.905123.014510009.77121.082910014.07121.3211
10020.67123.994110031.56137.639510042.46147.513210086.04164.633310096.94168.2505
10129.44182.264110172.35199.430610182.92 202.60310193.49206.807310219.95215.6157
#Mann= 3 , 0 , 0
 9493.35    0.12       0 9493.35    0.12       010219.95    0.12       0
#XS Ineff= 2 , 0
       0                               0
Bank Sta=9493.35,10219.95
Exp/Cntr=0.3,0.1

Type RM Length L Ch R = 1 ,15902.89,149.012500,149.012500,149.012500
XS GIS Cut Line= 6
823682.678875592843530.445444368823912.401386448843638.140343642
823983.486995878843677.523249565824200.601217985843812.180303362
824274.626580641843845.180503864824354.169857614843867.509545323
#Sta/Elev= 30
9515.481177.22179561.532171.27869594.263164.89829649.368152.23449682.517148.4431
9727.354145.23059740.191145.34029806.545137.18549817.977136.27919852.313134.9292
9864.956 135.1519899.102132.97749946.315131.94249958.282129.66169970.249 123.384
9994.183120.190210014.19121.541610029.96123.719810032.58124.706910041.88129.3886
10053.53139.591710065.06148.156510076.58154.348110088.11158.170110160.52170.6679
10187.58176.466810239.88189.990810250.16193.494810260.45195.604410269.87198.6602
#Mann= 3 , 0 , 0
9515.481    0.12       09515.481    0.12       010269.87    0.12       0
#XS Ineff= 2 , 0
       0                               0
Bank Sta=9515.481,10269.87
Exp/Cntr=0.3,0.1

Type RM Length L Ch R = 1 ,15753.88,136.688700,136.688700,136.688700
XS GIS Cut Line= 6
 823629.34795003843686.921896291823708.885001486843719.754555857
823836.497454506843779.794687096824110.167651585843922.859283898
824203.005733195843957.907213432824287.506068936843972.066434942
#Sta/Elev= 30
9551.948174.78089568.881172.73519622.974162.75489650.316155.37489655.805152.8534
9666.856149.51819673.806148.11329688.959147.43289700.011145.82529722.114139.8423
9744.217137.18019788.664134.06829947.365 131.318  9958.7129.93959970.036122.9518
9981.372118.588510015.21117.496410026.36118.902210037.51121.273110048.66127.6623
10059.81135.689610070.95141.9218 10103.9147.209310114.71 148.27610147.13145.8448
 10178.8 149.07610199.48152.759510209.73155.651410230.17158.782410272.97 168.298
#Mann= 3 , 0 , 0
9551.948    0.12       09551.948    0.12       010272.97    0.12       0
#XS Ineff= 2 , 0
       09893.709                       0
Bank Sta=9551.948,10272.97
Exp/Cntr=0.3,0.1

Type RM Length L Ch R = 1 ,15617.19,310.348700,310.348700,310.348700
XS GIS Cut Line= 6
823581.261893215843833.176574395823842.325216345843935.690367821
824028.310085973844038.409117382824075.264336226844056.450904958
824183.967886147 844065.17763119824275.516736613844047.093195103
#Sta/Elev= 30
9572.248153.80129577.698154.02759586.827155.5938 9608.05152.99789650.496152.3586
9661.108151.36629682.448147.70849736.272143.46039790.097136.16079867.028136.2077
9923.424131.92849934.981129.75889969.653120.9364 9981.21116.98319992.767116.3494
 10004.4116.715510016.05118.927810027.82122.086210061.65 134.235 10072.7137.0768
10115.46141.441110125.69140.689210146.12140.803710156.29  142.1110206.39144.0616
10226.42146.678910246.64 148.08910256.75150.2457 10297.5155.401210318.83159.7094
#Mann= 3 , 0 , 0
9572.248  0.0755       09572.248  0.0755       010318.83  0.0755       0
#XS Ineff= 2 , 0
       0                               0
Bank Sta=9572.248,10318.83
Exp/Cntr=0.3,0.1

Type RM Length L Ch R = 1 ,15306.84,298.024900,298.024900,298.024900
XS GIS Cut Line= 6
 823741.99473861844389.936870699823811.298881735844366.627586047
823857.428830408 844344.40633816823912.504426336844311.122017885
824079.279152109844187.159591048824282.713725357844085.157039746
#Sta/Elev= 30
9758.255174.66199792.797167.88239846.652158.89679891.493149.20139900.833147.6106
9914.862144.61399939.501145.27349950.059144.53019957.578138.99199962.321 134.286
9974.858118.73979986.844113.11159999.451111.837610012.17112.5532 10024.4 115.547
10037.56120.508910050.25122.442410088.33126.002110101.03126.538710137.59129.1823
10172.97133.379610195.97135.080710241.74140.742710252.69141.262810264.23142.6639
10309.91145.258210341.27149.685610352.24150.824510374.17155.115710382.63156.4202
#Mann= 3 , 0 , 0
9758.255    0.04       09758.255    0.04       010382.63    0.04       0
#XS Ineff= 2 , 0
       0                               0
Bank Sta=9758.255,10382.63
Exp/Cntr=0.3,0.1

Type RM Length L Ch R = 1 ,15008.81,298.024900,298.024900,298.024900
XS GIS Cut Line= 6
824115.139622521844647.144432394824145.825072184844600.200915514
824187.903774221844501.722875031824220.524158921844370.871547307
824253.886786506844276.768027134824322.625539028844169.818462711
#Sta/Elev= 30
9756.699208.34029773.737203.13759783.714199.48069812.831183.47269829.769173.5031
9840.911169.50149873.734144.03319884.433135.35699895.132129.48699905.831124.7378
 9916.53122.02399927.029119.92959937.431118.87769968.593117.25689978.849114.8745
9989.105 111.665 9999.36111.382310019.89112.298610030.61115.496810050.69118.9334
 10061.1122.498210082.09126.712710092.58128.167110103.07130.3552 10116.6131.5262
   10168141.525210179.83144.518310237.82152.707710249.72 153.88110282.44158.9214
#Mann= 3 , 0 , 0
9756.699  0.0428       09756.699  0.0428       010282.44  0.0428       0
#XS Ineff= 2 , 0
       0                               0
Bank Sta=9756.699,10282.44
Exp/Cntr=0.3,0.1