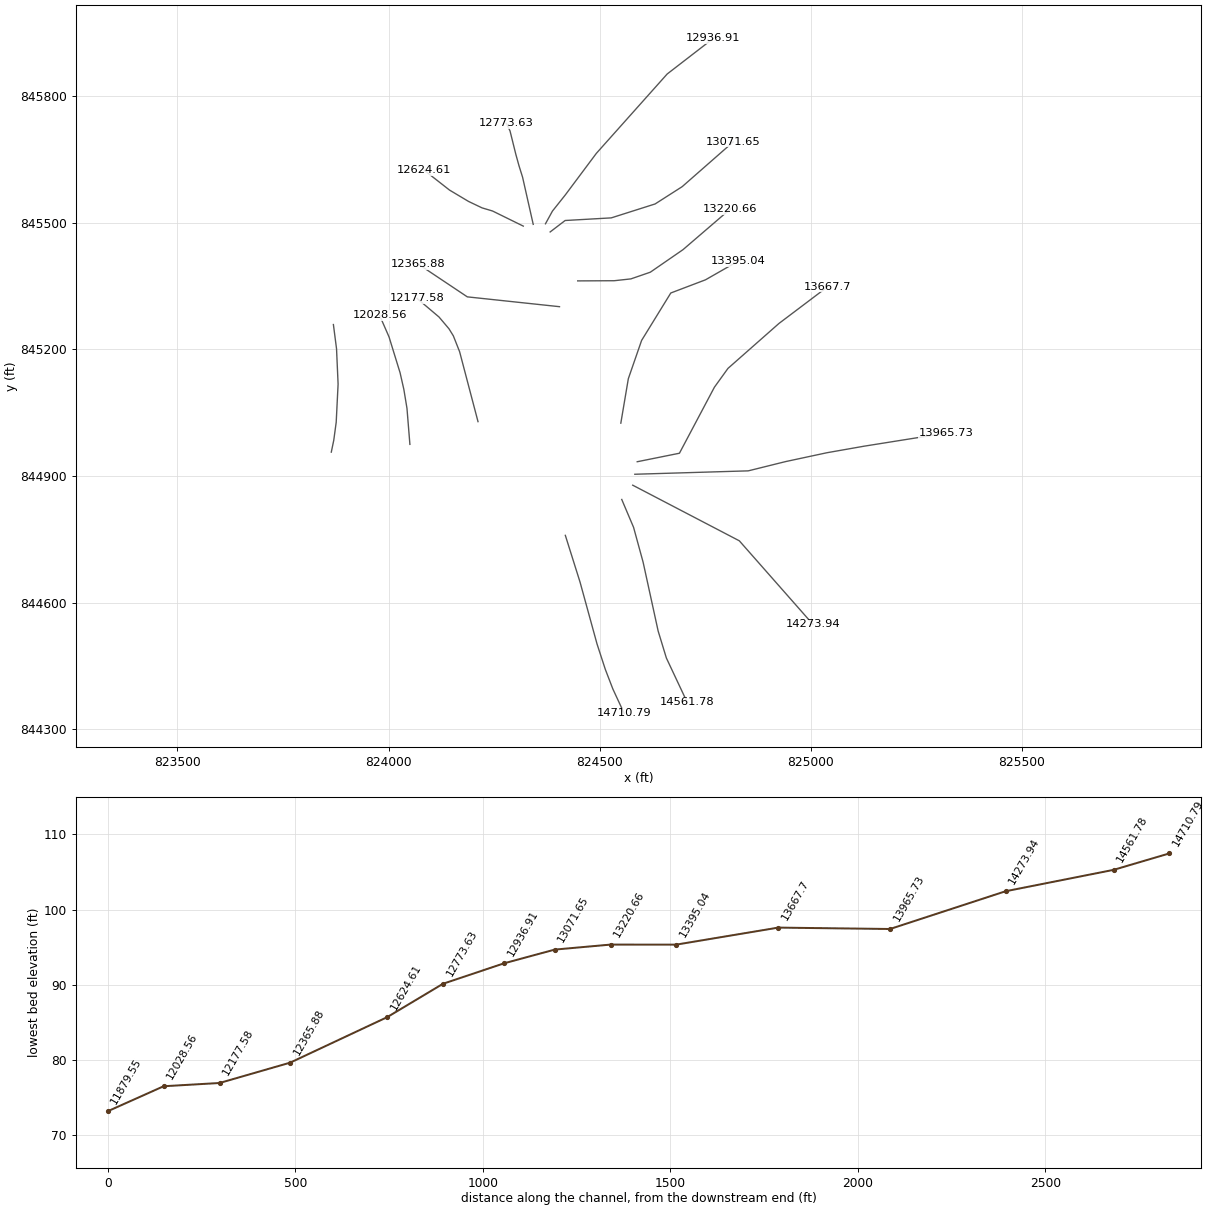
HEC-RAS study 18370_ras.prj: 18370

--- 18370_ras.g01 (geometry) --- (continued)

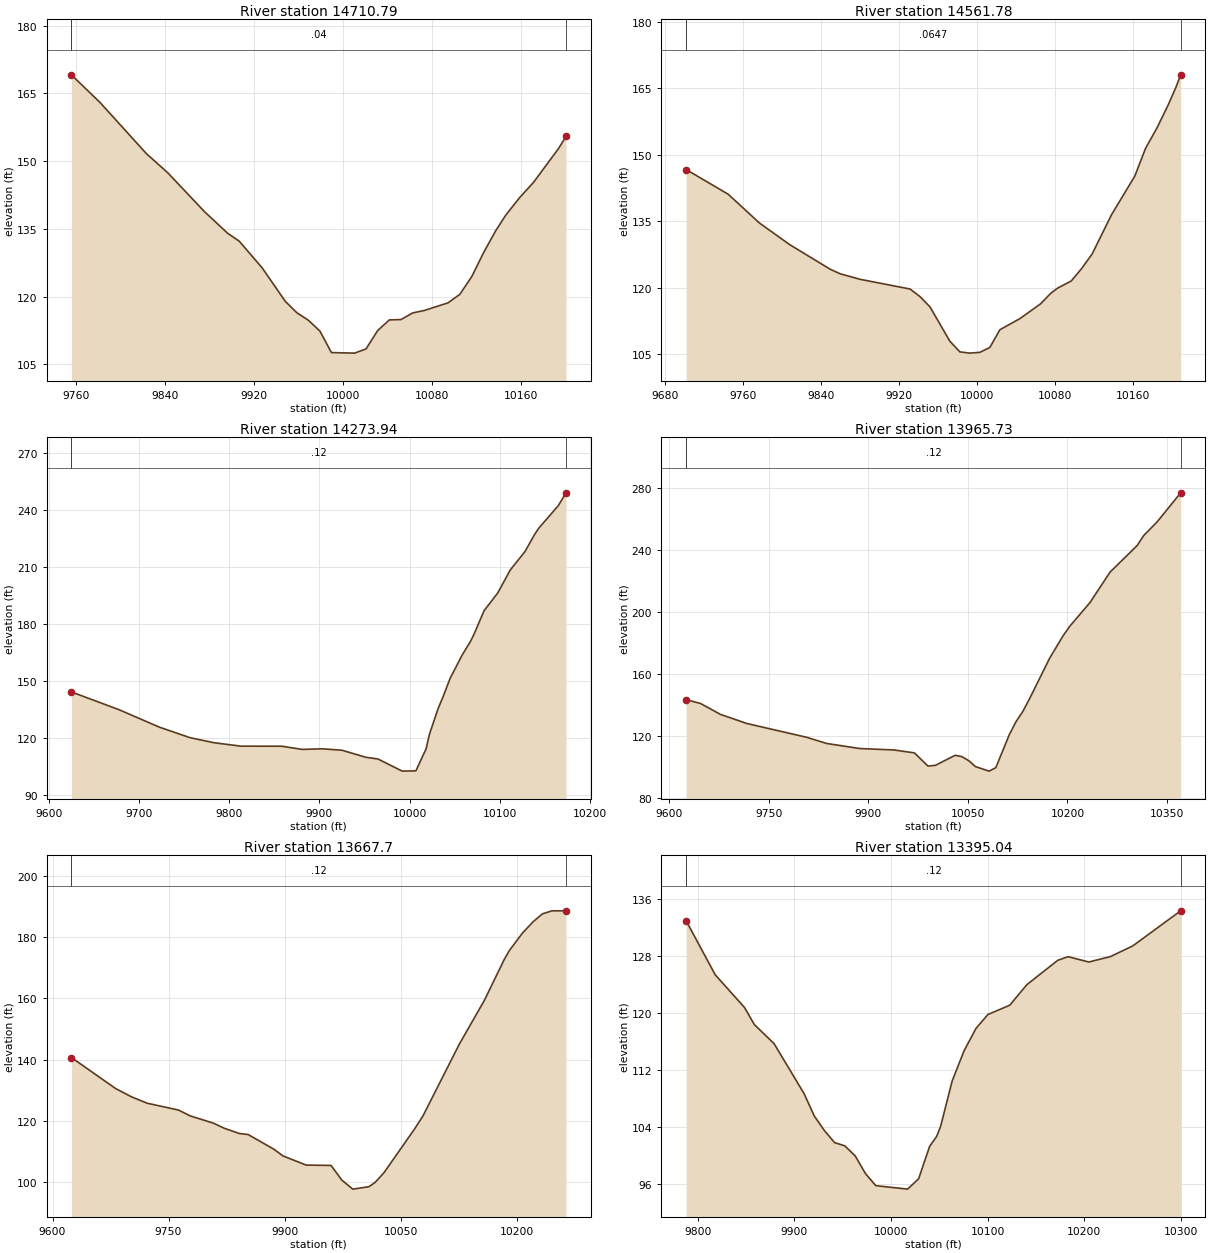
Type RM Length L Ch R = 1 ,14710.79,149.012500,149.012500,149.012500
XS GIS Cut Line= 6
824418.661390965 844759.28512517824453.498924351844648.594322126
824493.755054948844501.956318664824513.380095492844441.815268673
824531.144894217844395.578986241824558.018776286844337.626035933
#Sta/Elev= 30
9755.746169.12729781.439163.01599823.366151.62859842.212 147.4819875.539138.7925
9896.277134.02829906.645132.28739927.383126.34429948.121118.9468 9958.49116.4306
9968.859114.76339979.227112.37529989.596107.598810010.34107.473410020.72108.3986
10031.19112.469510041.71114.831810052.23114.911610062.75116.384410073.27116.9293
10094.44118.610710105.15120.508710115.86124.441210126.58129.7906 10137.3134.5594
10146.32138.010410159.12141.995710171.34 145.28710194.01152.844210200.58155.4654
#Mann= 3 , 0 , 0
9755.746    0.04       09755.746    0.04       010200.58    0.04       0
#XS Ineff= 2 , 0
       0                               0
Bank Sta=9755.746,10200.58
Exp/Cntr=0.3,0.1

Type RM Length L Ch R = 1 ,14561.78,287.838300,287.838300,287.838300
XS GIS Cut Line= 6
824552.291293869844844.299927793824580.324575276844778.180060357
824602.867929998844695.813362614824638.517997641844532.598298115
824657.976176974844468.778929314824707.416429846844363.650143321
#Sta/Elev= 30
 9701.76 146.6569745.058141.07489776.998134.60169808.101129.72299849.573124.1893
9859.929123.15279880.391  121.919931.545119.72819941.776118.01789952.007115.7025
9972.468107.94879982.699105.5603 9992.93105.280910003.17 105.45810013.43106.5539
 10023.7 110.54210044.56113.098110065.47116.389110075.92118.757310082.68119.8927
10096.94121.536910107.69124.360610118.44127.647210138.39136.500910162.17145.1696
10173.26151.463710184.74155.948810196.21161.107810204.31165.151510209.24167.9898
#Mann= 3 , 0 , 0
 9701.76  0.0647       0 9701.76  0.0647       010209.24  0.0647       0
#XS Ineff= 2 , 0
       0                               0
Bank Sta=9701.76,10209.24
Exp/Cntr=0.3,0.1

Type RM Length L Ch R = 1 ,14273.94,308.211500,308.211500,308.211500
XS GIS Cut Line= 3
824578.283242526844878.109714623824830.784666151844746.354284182
825005.034712642 844548.59431082
#Sta/Elev= 30
9624.945144.15729677.639134.81619722.757125.54939756.596120.04199782.982117.4023
9812.993115.58589858.111115.5611 9880.67113.88719903.229114.18479924.887113.4518
9951.543109.71739964.871108.82599991.762102.435610006.89102.599610018.18114.1123
10022.01121.982110031.51135.326910037.14141.728510044.84151.301610058.17163.5345
10067.39170.7169 10071.5174.692210082.52186.938210097.65196.280210111.48208.3483
 10127.9218.131710138.14226.796410143.02 230.31510164.79242.277210173.33249.0337
#Mann= 3 , 0 , 0
9624.945    0.12       09624.945    0.12       010173.33    0.12       0
#XS Ineff= 2 , 0
       0                               0
Bank Sta=9624.945,10173.33
Exp/Cntr=0.3,0.1

Type RM Length L Ch R = 1 ,13965.73,298.025000,298.025000,298.025000
XS GIS Cut Line= 6
824583.238965273844904.009088099824851.939936787844912.056546837
824940.171379864844933.951180503825038.079536676 844954.93552056
825126.804301322844970.561802581825319.980941117845001.331872404
#Sta/Elev= 30
9625.067143.49019646.838141.01689676.851133.98239716.869128.0848 9806.91119.2108
9836.923115.23619886.945111.97479938.255111.05369969.164109.17579989.739100.6649
   10001101.158710030.65107.612410040.88106.7388 10051.1104.162810061.33100.3195
10081.7897.4102810091.9599.6193510112.26120.873410122.42129.284510132.57135.8004
10142.72143.977810173.19170.267810193.44184.697310203.57190.831910233.95206.0814
10264.33225.762610304.83242.716910314.96 249.28910335.21258.106910370.63276.7857
#Mann= 3 , 0 , 0
9625.067    0.12       09625.067    0.12       010370.63    0.12       0
#XS Ineff= 2 , 0
       0                               0
Bank Sta=9625.067,10370.63
Exp/Cntr=0.3,0.1

Type RM Length L Ch R = 1 , 13667.7,272.663400,272.663400,272.663400
XS GIS Cut Line= 6
824588.926794826 844933.65874623824688.930676733844953.800368122
824771.765699773845110.168433045824803.875182615845154.731879333
824924.630653935845261.173025066 825039.69747277845347.982295041
#Sta/Elev= 30
9624.422140.67669681.621130.51559702.022127.81949722.424125.71259762.827123.4884
9777.541121.6111 9808.07119.18699821.913117.53069841.678115.7942 9852.88115.4656
9886.488110.6082 9897.69108.49339927.811105.47129960.065105.34929974.084100.5232
9988.10397.5958310009.0298.3877510016.9999.79517 10028.4102.953310067.67117.1671
10078.98121.618110125.71144.992310158.28159.412410183.79172.7149 10190.5175.6913
10207.47181.416210220.91185.042410233.29 187.71610245.67 188.69510263.72188.6937
#Mann= 3 , 0 , 0
9624.422    0.12       09624.422    0.12       010263.72    0.12       0
#XS Ineff= 2 , 0
       0                               0
Bank Sta=9624.422,10263.72
Exp/Cntr=0.3,0.1

Type RM Length L Ch R = 1 ,13395.04,174.374000,174.374000,174.374000
XS GIS Cut Line= 6
824550.097059196845025.043595419824567.900538278845130.377502031
824599.341356232845221.037708424824668.468132571845333.336529231
 824750.57432732845364.527068019824828.018792391845408.781048074
#Sta/Elev= 30
9787.799132.94729818.009125.35499848.262120.78789858.467118.39489878.973115.7057
9910.091108.68929920.589105.57339931.088103.52929941.587101.84669952.226 101.388
9962.93199.988739973.63597.499349984.33995.8105210017.2295.3265710028.6296.77229
10040.03101.306210047.28102.704510051.43104.1199 10063.4110.487910075.74 114.716
10088.08117.850710100.42119.795710123.04 121.09910140.73123.974610172.82127.3964
10183.52127.900710204.91127.149210227.49127.920910250.52129.414710300.07134.3239
#Mann= 3 , 0 , 0
9787.799    0.12       09787.799    0.12       010300.07    0.12       0
#XS Ineff= 2 , 0
       0                               0
Bank Sta=9787.799,10300.07
Exp/Cntr=0.3,0.1

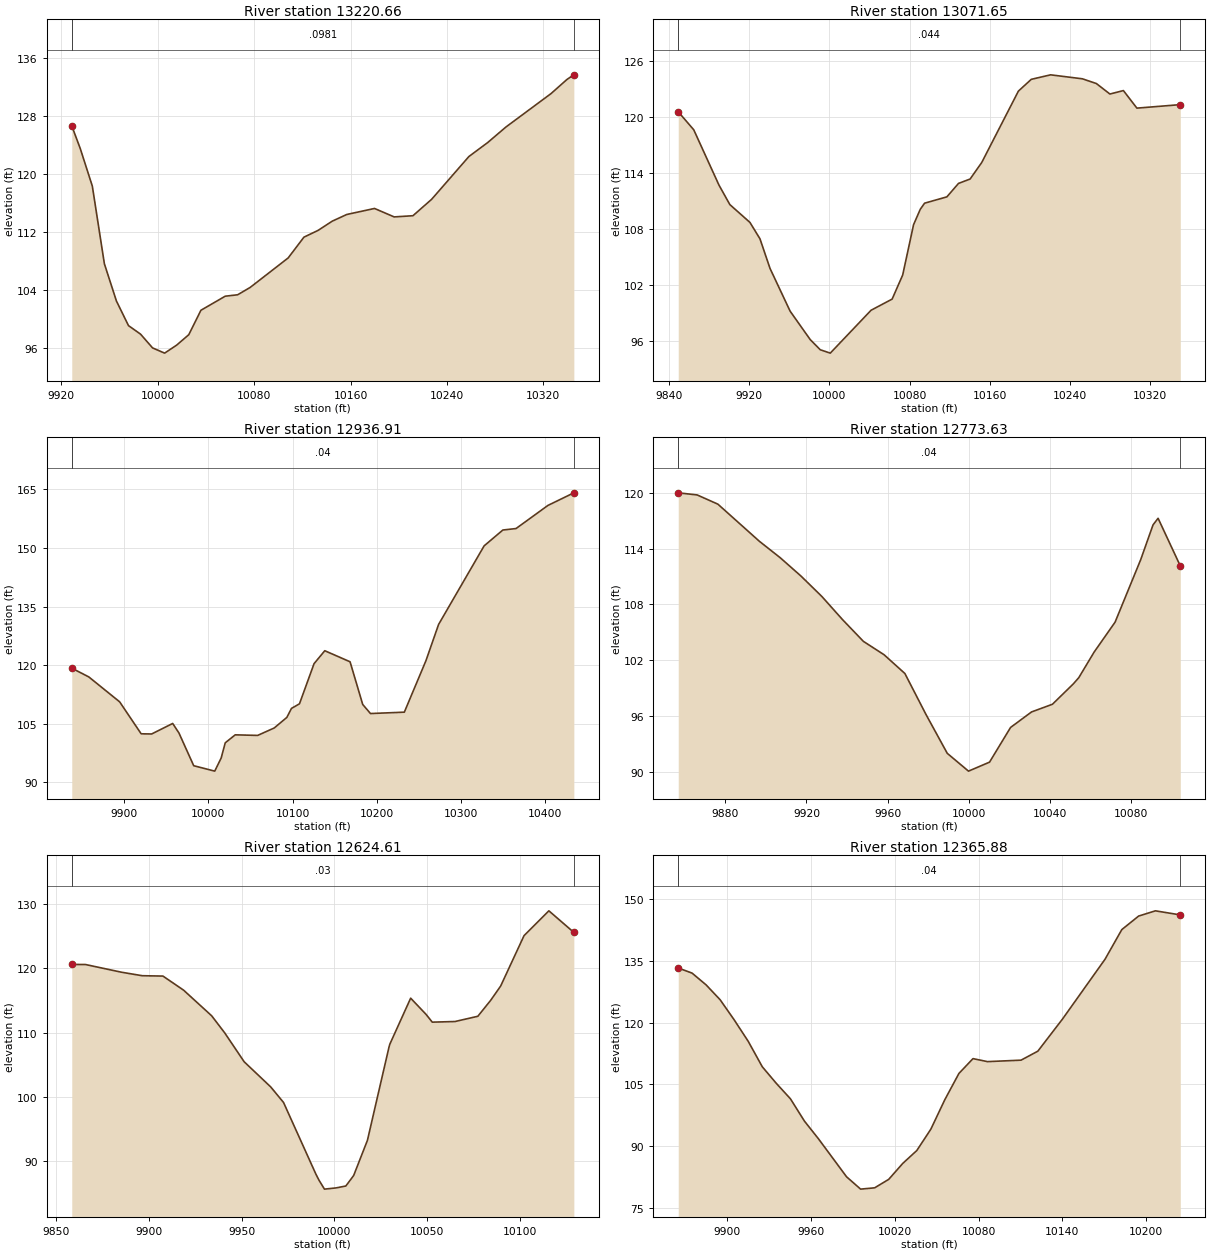
Type RM Length L Ch R = 1 ,13220.66,149.012400,149.012400,149.012400
XS GIS Cut Line= 6
824447.929759746845361.996437032824534.478679388845362.409494972
 824573.93115979845366.737282216824619.927473425845382.573481002
824697.420350619845436.024629716824809.257300874 845532.10417997
#Sta/Elev= 30
9928.653126.67459935.723123.53189945.723118.35769955.723107.65639965.723102.5212
9975.72499.129129985.724  97.9559995.72496.0550410005.7295.3351810015.7396.44074
10025.7997.8794510035.85101.2441   10056103.183110066.37103.382810076.74104.3956
10108.27108.461710121.35111.3244 10133.1112.258210144.85113.530210156.89114.4508
10179.93115.280710196.24114.116810211.82114.280310227.31116.539310258.29122.4471
10273.78124.357910289.02126.514310326.42 131.11810339.71 133.07510345.36133.7065
#Mann= 3 , 0 , 0
9928.653  0.0981       09928.653  0.0981       010345.36  0.0981       0
#XS Ineff= 2 , 0
       0                               0
Bank Sta=9928.653,10345.36
Exp/Cntr=0.3,0.1

Type RM Length L Ch R = 1 ,13071.65,134.741300,134.741300,134.741300
XS GIS Cut Line= 6
824382.713118136 845477.92789188824418.204980135845505.041613758
824527.446695954845511.245674074824631.289032936845544.223070711
824695.380660564845585.172042057824816.348331749845691.240857631
#Sta/Elev= 30
9849.233120.58799864.695118.65459889.863112.71299900.702110.62089920.733108.7068
9930.749106.94549940.764103.76699960.79599.177999980.82796.128159990.84295.03258
10000.8694.6694610041.5499.2743110062.54100.470710073.06103.053310083.92108.4623
10090.64 110.12110094.91110.769610117.13111.450510128.72112.892510140.32113.3661
10151.92 115.14310188.47122.805910201.28124.069510220.59 124.55510252.27124.1282
10266.25123.617710279.72122.493110293.18122.863710306.64120.978610349.93121.3537
#Mann= 3 , 0 , 0
9849.233   0.044       09849.233   0.044       010349.93   0.044       0
#XS Ineff= 2 , 0
       0                               0
Bank Sta=9849.233,10349.93
Exp/Cntr=0.3,0.1

Type RM Length L Ch R = 1 ,12936.91,163.283600,163.283600,163.283600
XS GIS Cut Line= 6
824371.649623126 845497.28900817 824388.10121724845527.289061308
824418.365652412845565.305970043824492.132163644845664.057912543
824659.891487658845852.043538034 824769.35147211845936.518091261
#Sta/Elev= 30
9837.781119.2266 9857.98116.98389894.634110.60319920.197102.41139932.688102.3653
9957.652105.05899965.094102.61169982.61694.2357710007.5892.8498210015.2296.20519
10020.06100.101310031.93102.145810058.52101.996710078.19103.895310093.21106.6093
10098.72108.916710108.23110.099510125.53120.377710138.27123.688710168.31120.8585
10183.33 109.92610192.54   107.610232.75107.951810258.42121.141710273.44130.4212
10327.52150.550510349.75154.605610365.42154.988210403.31160.910210434.07164.1358
#Mann= 3 , 0 , 0
9837.781    0.04       09837.781    0.04       010434.07    0.04       0
#XS Ineff= 2 , 0
       0                10118.62       0
Bank Sta=9837.781,10434.07
Exp/Cntr=0.3,0.1

Type RM Length L Ch R = 1 ,12773.63,149.012500,149.012500,149.012500
XS GIS Cut Line= 6
 824342.60794872 845495.90607129824317.388029873845607.676525623
824309.097335815845634.081826091824301.478884161845661.518658489
824287.639113963845717.257477671824279.175362829845734.880285792
#Sta/Elev= 26
9856.743119.97939866.066119.75439876.317 118.762 9896.82114.77389907.071113.0142
9917.323111.04579927.574108.86579937.826106.37119948.077104.04649958.329 102.604
 9968.58100.5909    997996.190729989.48192.028659999.95490.1201410010.3391.08266
10020.7194.8048610031.0696.4705110041.3797.2951510051.67 99.478410054.36 100.145
10061.97102.901910072.28106.103310084.91112.8042   10091 116.539 10093.5117.2489
10104.46112.1357
#Mann= 3 , 0 , 0
9856.743    0.04       09856.743    0.04       010104.46    0.04       0
#XS Ineff= 2 , 0
       0                               0
Bank Sta=9856.743,10104.46
Exp/Cntr=0.3,0.1

Type RM Length L Ch R = 1 ,12624.61,258.730200,258.730200,258.730200
XS GIS Cut Line= 6
824319.098021835845491.757260665824246.239916027845527.549753278
824221.487636477 845534.92264013 824189.47835952845550.162011668
 824144.26071018845577.161483407 824084.94598949845623.612216845
#Sta/Elev= 30
9858.527120.57439865.881120.56739885.376119.36569896.517118.82679907.659  118.77
  9918.8  116.589933.919112.59939940.996109.9285 9951.43105.45899965.717101.5584
9972.64999.135769989.98388.068219991.711 87.08389994.70985.67229   1000185.86332
10006.2286.1588210010.4487.7829510017.8693.2516610029.51107.763610029.94108.1927
10041.16115.337410049.45112.8232 10052.8 111.61210065.06111.709610077.36112.5246
10084.29115.005210089.66117.220810102.26125.051310115.65128.9063 10129.1125.5567
#Mann= 3 , 0 , 0
9858.527    0.03       09858.527    0.03       0 10129.1    0.03       0
#XS Ineff= 2 , 0
       0                               0
Bank Sta=9858.527,10129.1
Exp/Cntr=0.3,0.1

Type RM Length L Ch R = 1 ,12365.88,188.307200,188.307200,188.307200
XS GIS Cut Line= 3
824404.840108186845300.911971688 824186.51429075845324.173919633
824070.169384062845401.866363689
#Sta/Elev= 30
9865.002133.22339874.898131.98679884.954129.13279895.011125.52269905.067120.6512
9915.124115.44129925.181 109.2799935.237105.25049945.294101.5298 9955.3596.11363
9965.40791.81163 9985.5282.605079995.57779.6158410005.6379.9313310015.6981.98172
10025.7585.85037 10035.888.9722710045.86 94.149510055.92101.332110065.97107.6627
10076.03111.253610086.38110.526210110.43 110.87910122.46113.059910140.07120.8286
10170.56135.344310182.58142.534110194.61145.810510206.63147.083610224.46146.0947
#Mann= 3 , 0 , 0
9865.002    0.04       09865.002    0.04       010224.46    0.04       0
#XS Ineff= 2 , 0
       0                               0
Bank Sta=9865.002,10224.46
Exp/Cntr=0.3,0.1

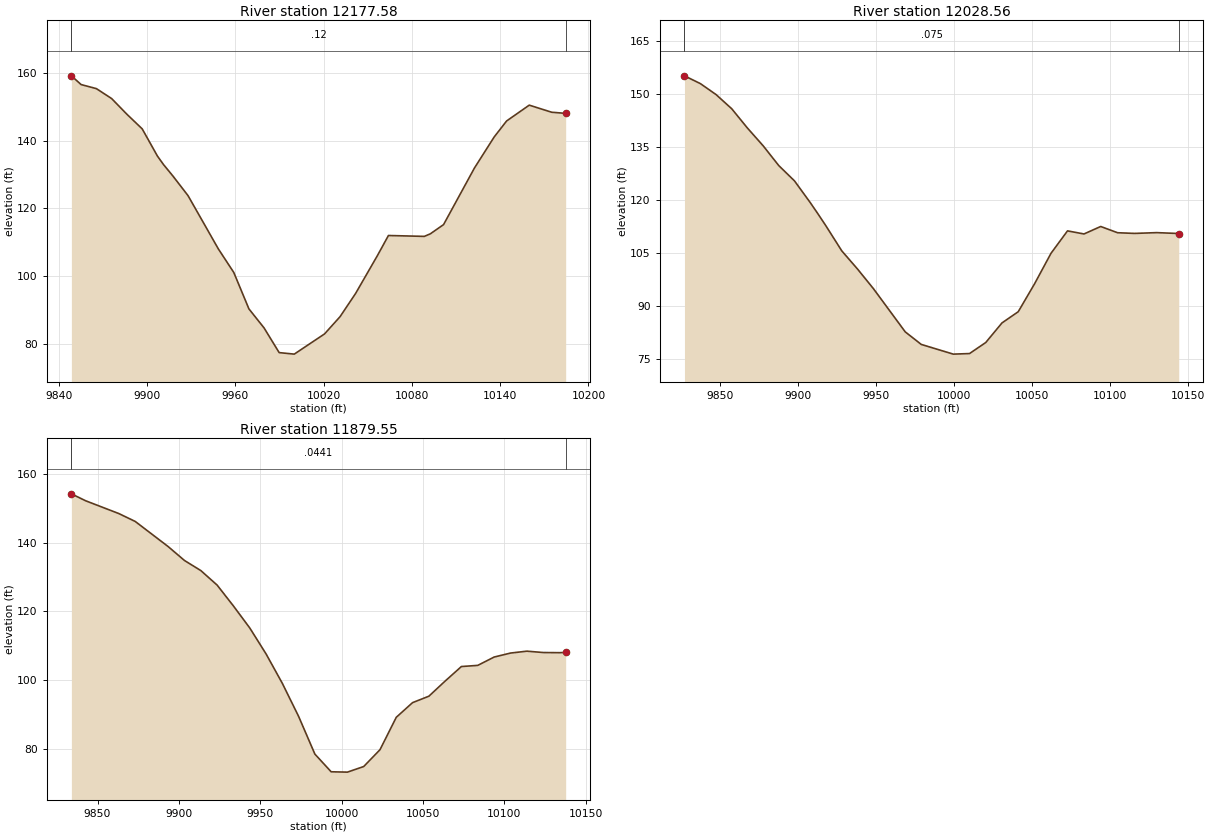
Type RM Length L Ch R = 1 ,12177.58,149.012500,149.012500,149.012500
XS GIS Cut Line= 6
 824211.83502779845028.628503949824168.248870754  845194.2834019
824153.411886708845231.795117215824143.101649512845248.499955974
824119.476353661845276.464645164824067.562276974845320.318666991
#Sta/Elev= 30
 9848.58159.25229855.194156.66699865.576155.46599875.957152.52029886.339147.8743
9896.721143.55419907.102135.48679911.253132.96689917.484129.66739927.865123.8048
 9948.48108.03559958.975101.06389969.25390.294729979.53184.673629989.80977.36007
10000.0876.9102610020.6682.89581 10031.287.9920810041.7694.8621110056.57106.0505
10064.08112.006310088.45111.7475 10092.5112.490210101.54115.229910122.55131.9868
10135.95141.1636 10144.4145.895910159.78150.576610175.07148.474310184.54148.1476
#Mann= 3 , 0 , 0
 9848.58    0.12       0 9848.58    0.12       010184.54    0.12       0
#XS Ineff= 2 , 0
       0                               0
Bank Sta=9848.58,10184.54
Exp/Cntr=0.3,0.1

Type RM Length L Ch R = 1 ,12028.56,149.012400,149.012400,149.012400
XS GIS Cut Line= 6
824050.510219774 844974.76707004 824043.58891124845060.048667819
824036.189274826845104.924814935824027.231906994845144.439868758
824001.077723528845229.337749615823978.592480367845280.686666696
#Sta/Elev= 30
9827.401155.07189837.644152.86349847.654149.77729857.663145.78069867.703140.3448
9877.759135.33719887.814129.72189897.869 125.4079907.924119.2973    9913116.0307
9918.018112.69689928.154105.64569938.289100.48379948.42494.967439968.81382.75575
9979.06779.216949999.57876.4777710009.9776.6378410020.37 79.760810030.7785.29356
10041.1788.45252 10051.696.3210910062.16104.953710072.72111.285110083.28110.4126
10093.98112.524810104.79110.7604 10115.6110.568810129.89110.788910143.96110.5403
#Mann= 3 , 0 , 0
9827.401   0.075       09827.401   0.075       010143.96   0.075       0
#XS Ineff= 2 , 0
       0                               0
Bank Sta=9827.401,10143.96
Exp/Cntr=0.3,0.1

Type RM Length L Ch R = 1 ,11879.55,149.012500,149.012500,149.012500
XS GIS Cut Line= 6
 823864.33264687844956.432074642823870.169476434844984.582654236
823875.947548466845027.159655896 823880.43988112845117.574443947
823876.734095715845201.252136811823869.304006085 845258.61182422
#Sta/Elev= 30
9833.916154.23489842.666152.21469863.086 148.4869873.178146.18419893.361138.8875
9903.453134.81139913.495131.87579923.525127.64129933.554121.55569943.583115.1533
9953.603107.59439963.60699.017999973.60989.397419983.61278.406829993.61573.25202
10003.6273.1513610013.63 74.783510023.6479.6813610033.6589.1226410043.6693.39722
10053.67 95.265510063.6899.6760110073.69103.916210083.73104.250510093.82106.6806
 10103.9107.843910113.98 108.39110124.07107.994710134.15107.950410137.79108.0429
#Mann= 3 , 0 , 0
9833.916  0.0441       09833.916  0.0441       010137.79  0.0441       0
#XS Ineff= 2 , 0
       0                               0
Bank Sta=9833.916,10137.79
Exp/Cntr=0.3,0.1