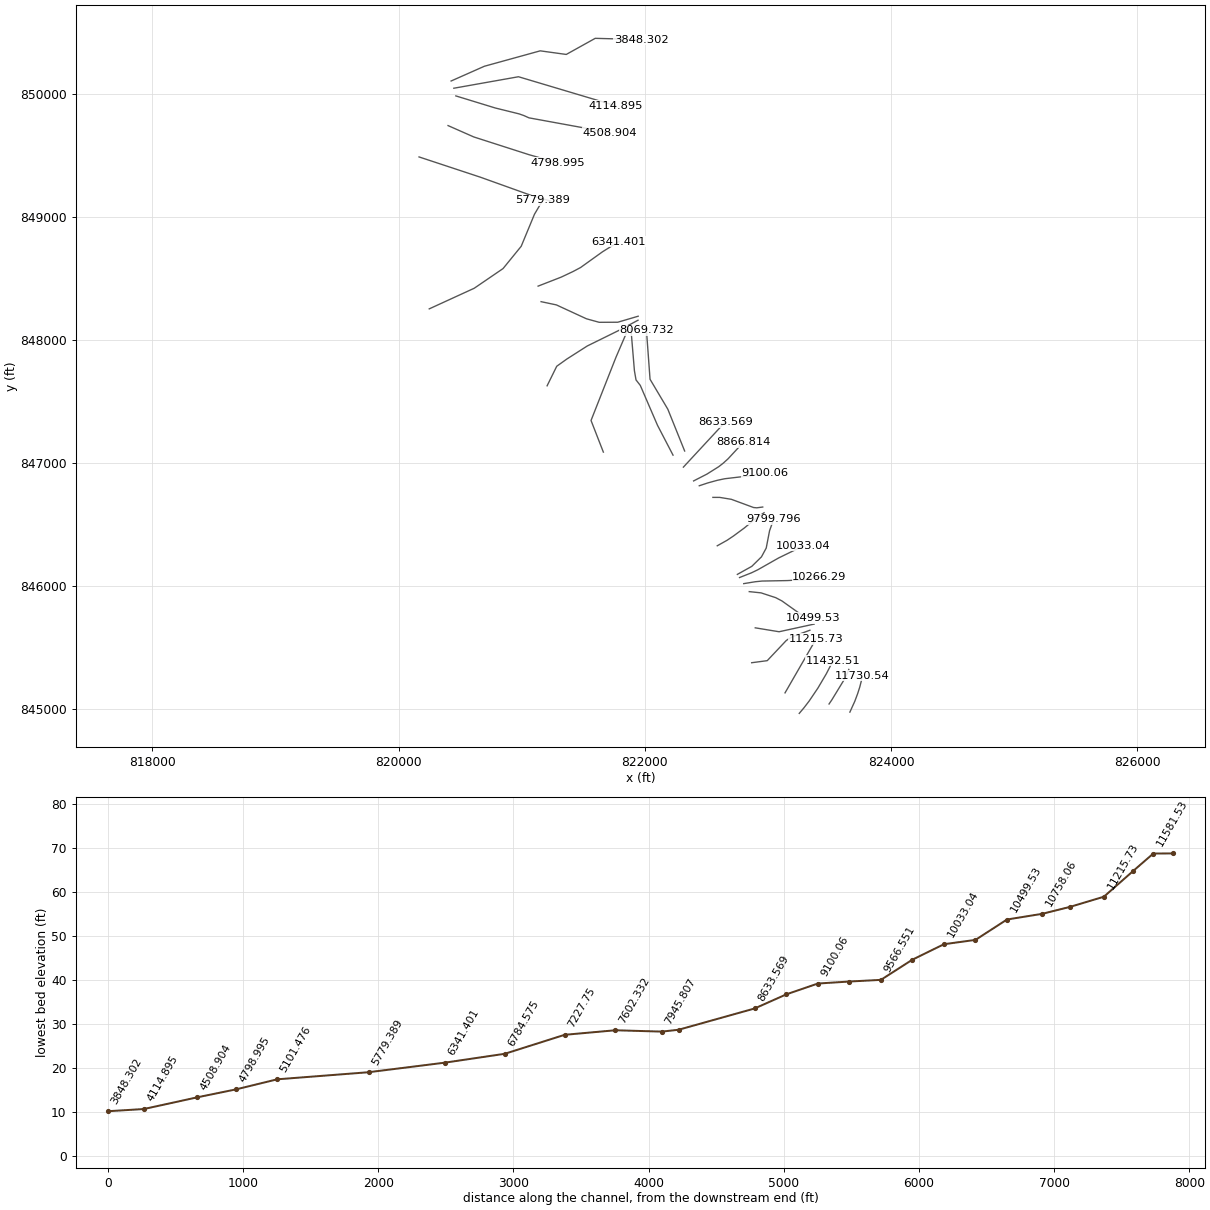
HEC-RAS study 18370_ras.prj: 18370

--- 18370_ras.g01 (geometry) --- (continued)

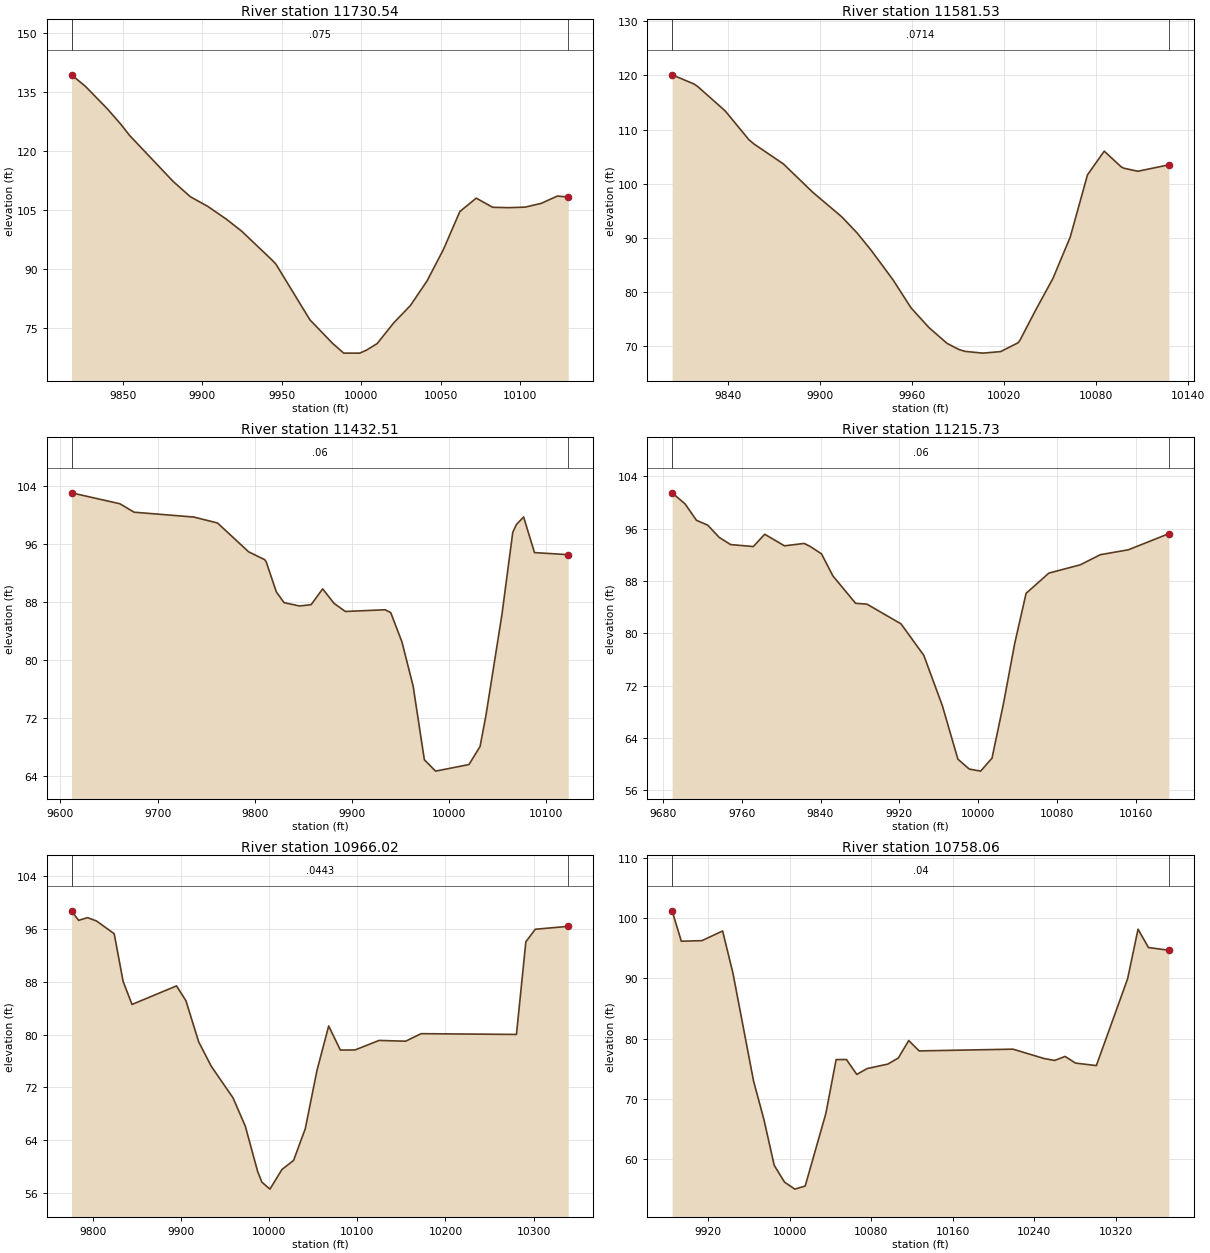
Type RM Length L Ch R = 1 ,11730.54,149.012400,149.012400,149.012400
XS GIS Cut Line= 6
823664.806306713844977.201190014823705.048203303845065.900075056
823728.281534366845128.254414338823745.327215009845181.622302565
823757.660264524845230.098455215823764.618197213845271.765488068
#Sta/Elev= 30
9817.828139.37479826.549136.45889840.602130.64379848.915126.78959854.273124.0263
9881.678112.3301 9892.55108.42399903.421105.99349915.271102.70739924.98299.62385
9943.77492.400929946.32591.329679967.66877.201759981.81371.262559988.93368.72685
    999968.7234810003.0269.4269810009.96  71.13310020.4476.4256810030.9180.82684
10041.3387.0407510051.6495.0356510061.96104.668610072.28108.0701 10082.6105.7439
10092.83105.654810102.97105.785810113.11106.737810123.25108.593510130.11108.3452
#Mann= 3 , 0 , 0
9817.828   0.075       09817.828   0.075       010130.11   0.075       0
#XS Ineff= 2 , 0
       0                               0
Bank Sta=9817.828,10130.11
Exp/Cntr=0.3,0.1

Type RM Length L Ch R = 1 ,11581.53,149.012500,149.012500,149.012500
XS GIS Cut Line= 6
823495.541213696 845043.25239301823516.787250987 845074.49701686
823611.975593591845230.353715179823634.802010096845273.610499653
823652.539312775845313.683869344823655.982613183845323.875239748
#Sta/Elev= 30
9803.459120.11539817.665118.4343 9820.28117.92419838.064113.45559853.577108.1146
9856.908107.32679875.982103.66439895.05598.443689914.12993.867599924.03790.91685
9933.203 87.71499947.52382.231619959.26777.05768 9971.0173.393159982.75370.49618
9990.42569.369919994.49769.0162710006.1368.6933910017.6968.9777310029.1370.61676
10030.3671.1142710040.4476.6017110051.7882.4922410063.05  90.12610074.31 101.633
10085.24106.014210096.18103.135810097.98102.868110107.11102.298410127.37103.4826
#Mann= 3 , 0 , 0
9803.459  0.0714       09803.459  0.0714       010127.37  0.0714       0
#XS Ineff= 2 , 0
       0                               0
Bank Sta=9803.459,10127.37
Exp/Cntr=0.3,0.1

Type RM Length L Ch R = 1 ,11432.51,216.780700,216.780700,216.780700
XS GIS Cut Line= 6
823253.625621129844967.009486833823290.329839214845010.365554911
823333.651210229845066.699837247823404.883237186845172.083933137
823473.200590907845287.986877611823528.864821854845396.070944359
#Sta/Elev= 30
 9611.36103.07719661.136101.57089675.827100.40669737.088  99.7439761.61998.92185
9793.65594.950479810.21393.867339811.80693.540269822.15789.436139830.09387.94585
9846.046 87.4898 9857.9987.66939 9869.8689.843119881.551 87.84939893.24286.72891
9934.184 86.96899939.92486.569089951.45182.535699962.97976.439539974.50666.30367
9986.03364.7347910020.4265.6416210031.8368.1220710037.8472.3673310054.3286.26928
 10065.597.6429510069.2398.7075310076.6899.7473310087.8694.84204 10122.6 94.5559
#Mann= 3 , 0 , 0
 9611.36    0.06       0 9611.36    0.06       0 10122.6    0.06       0
#XS Ineff= 2 , 0
       0                               0
Bank Sta=9611.36,10122.6
Exp/Cntr=0.3,0.1

Type RM Length L Ch R = 1 ,11215.73,249.710300,249.710300,249.710300
XS GIS Cut Line= 2
823138.069929212845133.576609612823389.764440775845570.584662616
#Sta/Elev= 30
9689.305 101.4889702.48899.790199714.02897.287269725.56896.531919737.10894.67093
9748.64893.570079771.72893.268729783.337  95.1499803.37393.37784 9823.4193.74296
9829.42893.288729840.96892.151559852.50888.783079875.588 84.58119887.12884.45252
9921.74881.429769944.82876.619369963.66568.915099979.44860.728989990.98859.21639
10002.5358.8985710014.0760.8801310025.6169.1458510037.1578.4524610048.6986.11204
10071.7789.1998710103.9290.4827610123.9692.0176210152.5592.7724510193.61 95.2386
#Mann= 3 , 0 , 0
9689.305    0.06       09689.305    0.06       010193.61    0.06       0
#XS Ineff= 2 , 0
       0                               0
Bank Sta=9689.305,10193.61
Exp/Cntr=0.3,0.1

Type RM Length L Ch R = 1 ,10966.02,207.963000,207.963000,207.963000
XS GIS Cut Line= 6
822867.014301389845378.356436774822993.539737284845395.203760922
823147.505220741845558.251967266823169.311140984845573.654446021
823214.836938143845596.399537176823340.107665122845642.424800575
#Sta/Elev= 30
9776.102 98.71789784.15897.273589794.24697.688559804.33597.189719824.51195.25322
9834.59988.039499844.68884.549099895.12987.354499905.83985.113829920.18878.91417
9934.53875.194249959.23670.405769973.17966.110329987.123 59.25829991.93457.65422
10001.0556.5983410014.6259.5667810027.8760.9455110041.1365.7586910054.3874.57306
10067.6381.2891510080.8877.6434510097.5477.6628110124.7579.1023810154.8578.98587
10172.39 80.125210280.4980.0104210291.1594.02705 10301.895.92975 10339.296.36814
#Mann= 3 , 0 , 0
9776.102  0.0443       09776.102  0.0443       0 10339.2  0.0443       0
#XS Ineff= 2 , 0
       0                               0
Bank Sta=9776.102,10339.2
Exp/Cntr=0.3,0.1

Type RM Length L Ch R = 1 ,10758.06,258.528000,258.528000,258.528000
XS GIS Cut Line= 3
822896.055975795845661.858496472823089.667138517845630.050948322
 823374.55213511845692.283107772
#Sta/Elev= 30
9884.473101.19549893.53796.151019913.80596.248439934.07397.853949944.20790.86379
9964.47572.937759974.60966.580579984.74358.960719994.87756.1687710005.0155.00872
10015.1555.5150510035.4167.5277910045.5576.5088510055.6876.5197910065.8274.04711
10075.9575.0132110096.37 75.762310106.6176.7700910116.8579.6693510127.0877.94689
 10219.278.2354710249.9176.6769410260.15 76.363710270.3877.0311910280.6275.92732
10301.0975.51209 10331.889.9257310342.0398.1447810352.2795.1059810372.2894.64824
#Mann= 3 , 0 , 0
9884.473    0.04       09884.473    0.04       010372.28    0.04       0
#XS Ineff= 2 , 0
       0                               0
Bank Sta=9884.473,10372.28
Exp/Cntr=0.3,0.1

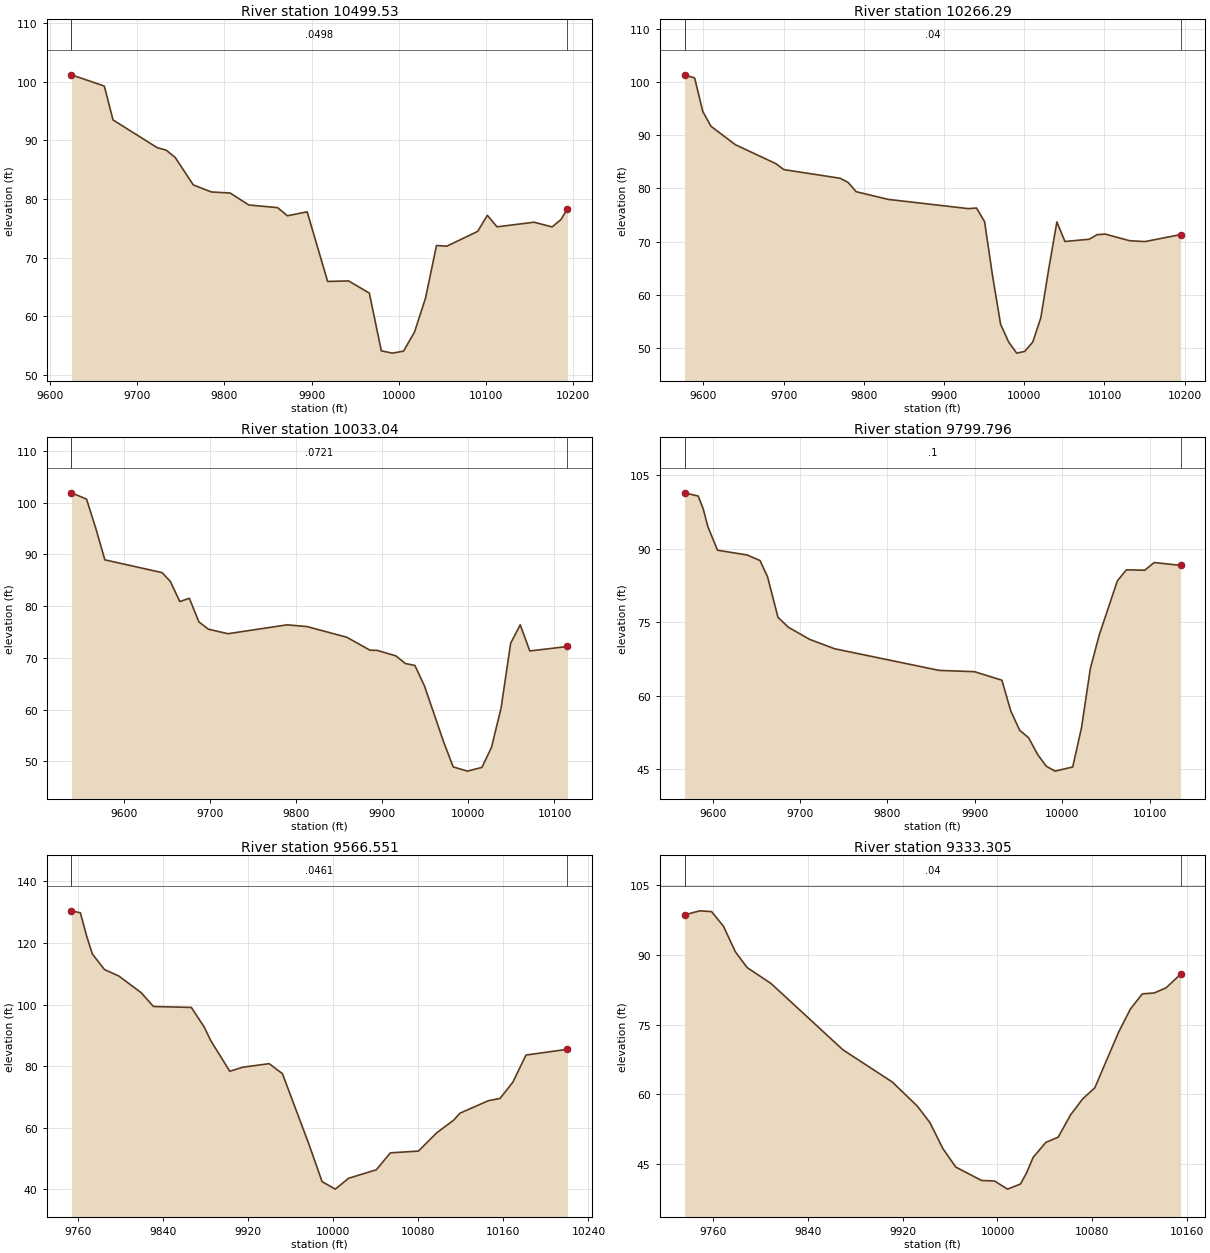
Type RM Length L Ch R = 1 ,10499.53,233.245500,233.245500,233.245500
XS GIS Cut Line= 6
822847.452614861845955.988080276822943.303725096845945.854116442
823062.450954037 845906.84324725823112.563635548845880.520866824
823262.405369254845773.908719986823362.472577778845742.060660011
#Sta/Elev= 30
9624.751101.19759662.36399.28369  9672.493.503889723.03188.77337 9733.3788.34854
 9743.7187.097119764.38982.42329 9785.1581.220289806.63381.039239828.11778.99727
9861.03778.547669872.33377.159989894.92477.835029918.40365.959889942.42466.04506
9966.17663.976769979.95554.126719992.71553.7333410005.3954.0742210017.9957.33366
10030.58 63.107110043.1872.0885310055.1471.9782510090.4174.5002310101.4877.23919
10112.5475.2750810155.1176.0604510175.7575.2569810185.8276.5115510193.3478.38162
#Mann= 3 , 0 , 0
9624.751  0.0498       09624.751  0.0498       010193.34  0.0498       0
#XS Ineff= 2 , 0
       09951.808                       0
Bank Sta=9624.751,10193.34
Exp/Cntr=0.3,0.1

Type RM Length L Ch R = 1 ,10266.29,233.245400,233.245400,233.245400
XS GIS Cut Line= 6
822802.688674403846020.857858379822896.293971432846036.236384942
822950.927354431846041.782999138823158.211874503 846045.72167862
 823296.02960392846053.647507747823417.418734129846073.793596811
#Sta/Elev= 30
9576.577101.31519589.113100.72059599.29594.426919609.47891.666929639.82288.21369
 9690.2684.660519700.31183.538239770.51381.912399780.51881.125979790.51879.38485
 9830.52 77.94749930.52376.213789940.527 76.33189950.53373.770739960.53963.58381
9970.54554.510999980.55151.208739990.557 49.109810000.5649.4310610010.5951.17064
10020.6255.7139410030.6565.0057410040.69 73.728610050.7270.0540510080.8670.46813
10090.9571.3364310101.0471.4351210131.31 70.198610150.4870.0322910194.9371.34585
#Mann= 3 , 0 , 0
9576.577    0.04       09576.577    0.04       010194.93    0.04       0
#XS Ineff= 2 , 0
       0                               0
Bank Sta=9576.577,10194.93
Exp/Cntr=0.3,0.1

Type RM Length L Ch R = 1 ,10033.04,233.245500,233.245500,233.245500
XS GIS Cut Line= 6
822768.550574038846070.329173303822866.356597419846109.037851847
822917.058095186846133.489939766823085.535978754846229.184518964
823248.810394919846308.824933274823283.466450126846327.869848893
#Sta/Elev= 30
9538.628101.91189556.141100.70169566.788 95.11789577.434 88.96039643.84386.49804
 9653.4484.819269664.54280.898939675.64481.528799686.746 76.96059697.84875.55159
9720.54274.685319789.36176.400229812.45676.059089858.64574.001659885.53771.49998
9893.905 71.46719915.54370.40744 9926.6668.930759937.77868.548579948.895 64.5897
9971.12953.797389982.246 48.94879998.77448.1270310015.6448.8461810026.7752.70755
10037.9160.3025910049.0572.8301610060.1976.4066210071.3271.3496610115.1172.21335
#Mann= 3 , 0 , 0
9538.628  0.0721       09538.628  0.0721       010115.11  0.0721       0
#XS Ineff= 2 , 0
       0                               0
Bank Sta=9538.628,10115.11
Exp/Cntr=0.3,0.1

Type RM Length L Ch R = 1 ,9799.796,233.245500,233.245500,233.245500
XS GIS Cut Line= 6
822750.836168103846096.000049693822868.168585001846161.277725089
822946.682321385846238.519626188 822985.23993357846309.586250498
823012.474384196846450.579427489823045.240722543846542.075324549
#Sta/Elev= 30
9567.834101.38569583.464100.72739589.11798.123269594.49994.469749605.53489.67719
9639.31188.714619654.18487.575019662.789 84.2524 9674.7275.98743 9686.6573.96232
 9711.03 71.48959739.54269.581219859.14165.168489899.58764.906129930.91463.16917
9941.11856.890639951.32152.947879961.52551.433119971.617 48.08379981.70245.62499
9991.787 44.622510011.9845.4708410022.0953.5184810032.1965.5806810042.4172.44338
10063.0983.4313310073.4385.6827110094.4185.5998910105.2487.1692210135.4686.59164
#Mann= 3 , 0 , 0
9567.834     0.1       09567.834     0.1       010135.46     0.1       0
#XS Ineff= 2 , 0
       0                               0
Bank Sta=9567.834,10135.46
Exp/Cntr=0.3,0.1

Type RM Length L Ch R = 1 ,9566.551,233.245500,233.245500,233.245500
XS GIS Cut Line= 6
822587.563861595846328.304552948822667.854495302846373.312696798
822719.886228606846408.236641699822808.085762671846473.343758876
 822913.41793908846560.358561838822967.832015983846596.642489308
#Sta/Elev= 30
9753.817130.44059762.218129.78489768.212122.09279773.514116.4083 9784.81111.3743
9798.158109.3039 9819.31103.87439830.94299.358269866.54499.057369878.58792.72875
9884.80988.279349902.67578.327219914.91579.63725 9939.7780.793399952.19777.53921
9977.05254.703229989.47942.48324 10001.940.0397310014.3543.5541410040.5146.32269
10053.7151.82216 10080.152.3993510097.3458.3440310113.1562.4222610119.0864.69469
10146.0568.7892310156.7769.4897910168.7974.7146510181.2683.5966410220.2785.46457
#Mann= 3 , 0 , 0
9753.817  0.0461       09753.817  0.0461       010220.27  0.0461       0
#XS Ineff= 2 , 0
       0                               0
Bank Sta=9753.817,10220.27
Exp/Cntr=0.3,0.1

Type RM Length L Ch R = 1 ,9333.305,233.245500,233.245500,233.245500
XS GIS Cut Line= 6
822552.182969597846721.404786891822607.750060007 846721.32703853
822702.288374178846705.710201681822882.732860752846639.031763846
822908.749387674846636.723566535822956.872033275846643.079149346
#Sta/Elev= 30
9735.67598.540629748.49299.414099758.49299.244159768.49296.111249778.49290.65732
9788.49287.236559808.60283.838079869.49169.567559911.147 62.66369932.24457.50006
9942.89753.956039953.82348.396969964.74844.403869986.59941.520069997.52441.41293
10008.4939.6657910019.4140.7589710024.5443.1302610030.1246.4739810040.8349.69323
10051.3250.8277310061.6455.5649810071.9559.0308310082.21 61.413510102.2973.34509
10112.3278.3421610122.36 81.5826 10132.481.7755910142.48 82.893210154.7185.80629
#Mann= 3 , 0 , 0
9735.675    0.04       09735.675    0.04       010154.71    0.04       0
#XS Ineff= 2 , 0
       0                               0
Bank Sta=9735.675,10154.71
Exp/Cntr=0.3,0.1

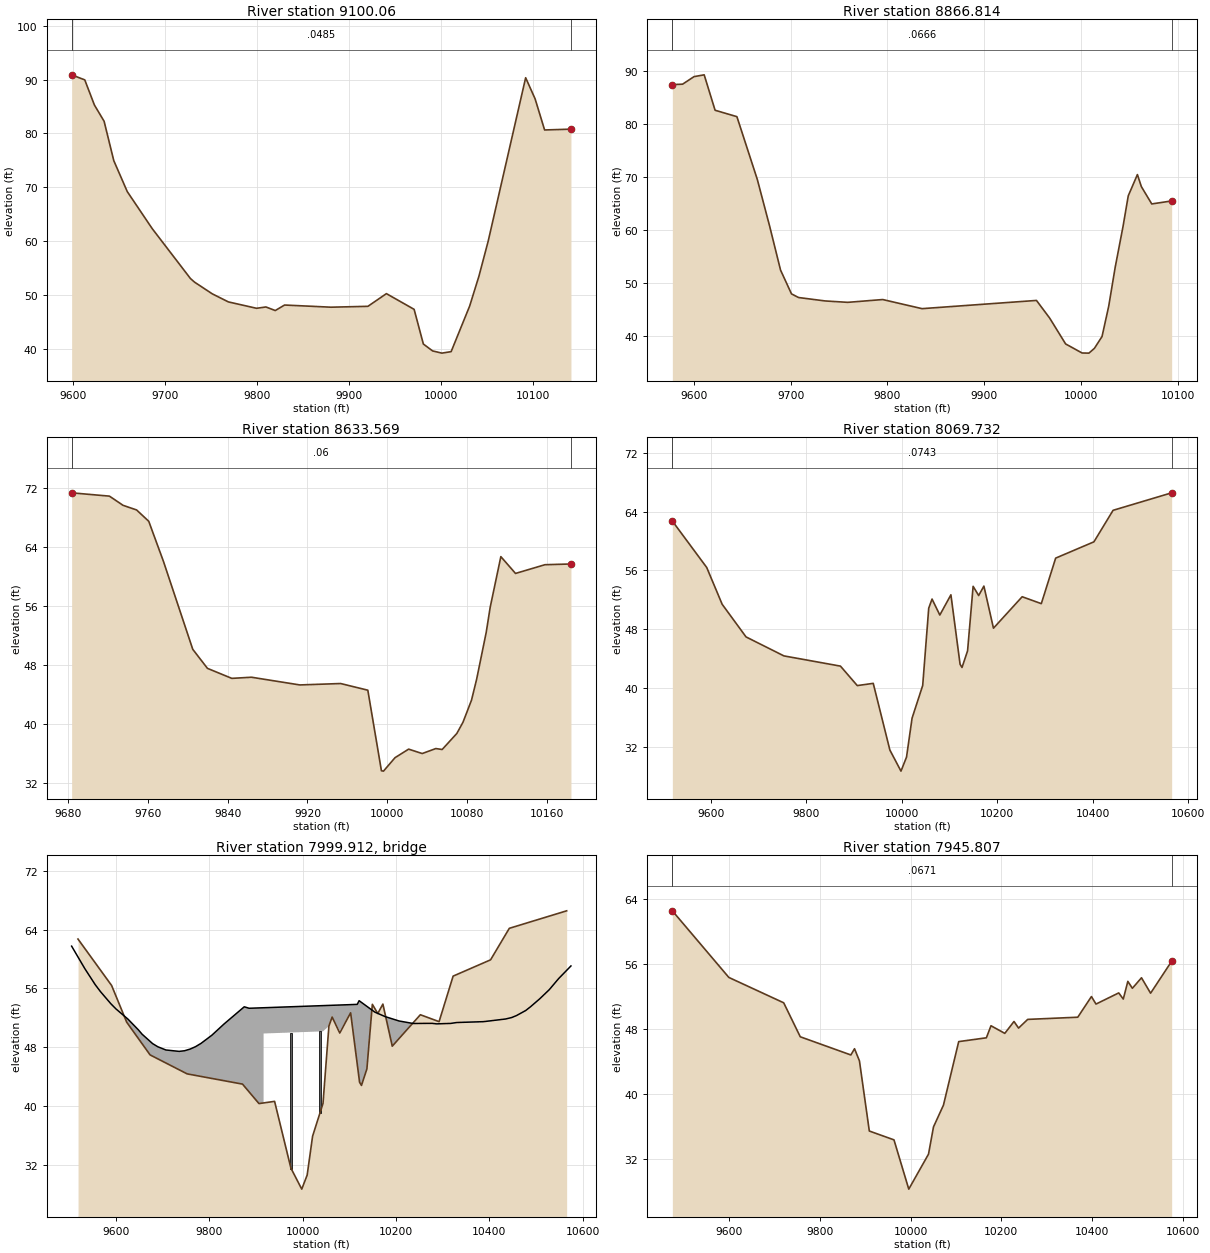
Type RM Length L Ch R = 1 , 9100.06,233.245500,233.245500,233.245500
XS GIS Cut Line= 6
822441.553786266846815.821072665822511.119362348846838.984575463
 822587.85190766846860.100981646822648.146606632846872.863728674
822883.017121999846900.524132726822972.633408677846920.935233269
#Sta/Elev= 30
9598.25890.896699612.54289.958199623.06385.278879633.58482.271619644.105 74.9572
9658.76269.209869685.98162.311029727.46853.066019731.94552.39187 9751.1750.22307
9768.69848.721599799.36247.534149809.58447.777919819.73947.115229829.86448.13913
 9880.3347.737469920.52747.898469940.62650.255369970.77547.337159980.82440.89549
9990.873 39.615110000.9339.2057110011.0239.4798810031.1947.9583710041.2753.50225
10051.3760.0333810092.0890.3571210102.3886.4243110112.6980.6557610141.3480.80579
#Mann= 3 , 0 , 0
9598.258  0.0485       09598.258  0.0485       010141.34  0.0485       0
#XS Ineff= 2 , 0
       09899.079                       0
Bank Sta=9598.258,10141.34
Exp/Cntr=0.3,0.1

Type RM Length L Ch R = 1 ,8866.814,233.245500,233.245500,233.245500
XS GIS Cut Line= 6
822395.501891238846855.123983077822503.787126406846910.630843236
822599.757386182846970.930680055822636.254118777846999.423524536
822675.551599596 847035.02201844822798.877067048847168.097193325
#Sta/Elev= 30
9577.72387.503399588.30487.58379 9600.14  89.0119610.61789.351939621.88782.65515
9644.42881.443989665.52269.567419678.23960.752639689.509 52.44669700.81647.94901
9708.09247.258899735.53646.612729758.97746.347629795.05846.87807 9835.6745.15549
9953.91846.709429967.56343.368289984.02138.48812   1000136.77694 10008.136.74953
10013.7337.6456510021.6539.8890210028.5545.6166110035.1952.9245910043.3760.72493
10048.7466.4802110058.1970.4961910062.2968.2166910073.0264.9472610093.5865.51596
#Mann= 3 , 0 , 0
9577.723  0.0666       09577.723  0.0666       010093.58  0.0666       0
#XS Ineff= 2 , 0
       0 9851.44                       0
Bank Sta=9577.723,10093.58
Exp/Cntr=0.3,0.1

Type RM Length L Ch R = 1 ,8633.569,563.837100,563.837100,563.837100
XS GIS Cut Line= 3
 822312.42802301846967.200015098822629.932930682847309.715447647
822653.796969875847333.370528247
#Sta/Elev= 30
9683.53671.315549721.443 70.86629735.07869.621299748.71468.988729760.86867.45184
9775.57762.022419804.99750.085979819.70647.501959844.16346.142579863.83546.29732
9912.34145.252059953.24845.442449980.519 44.53849994.15433.611179996.223 33.5588
10007.7935.3834310021.4336.5409910035.0635.94519 10048.736.6205910055.0636.49265
10069.7738.6709310075.9740.2023210084.4843.18938 10089.646.0132710099.1952.36235
10103.2455.81046 10113.962.6592510128.6160.3783310158.0861.5620210184.1861.66215
#Mann= 3 , 0 , 0
9683.536    0.06       09683.536    0.06       010184.18    0.06       0
#XS Ineff= 2 , 0
       09888.107                       0
Bank Sta=9683.536,10184.18
Exp/Cntr=0.3,0.1

Type RM Length L Ch R = 1 ,8069.732,123.924700,123.924700,123.924700
XS GIS Cut Line= 4
822322.685049623847098.147148326822185.966299593847437.773884445
822041.652063489847680.829440013822012.504836023848077.454361066
#Sta/Elev= 30
 9518.8862.706339590.94656.392289623.28651.395979673.35246.957829752.644 44.3816
9871.22242.990279906.47240.344829939.91540.648599974.80531.584499998.06528.72081
10009.6930.6298410021.3235.9237410043.5840.3599110056.2150.8620510063.1752.10436
10079.4749.9336410102.7352.6807910121.9343.2393910125.9942.8124610137.6245.06418
10149.2553.8338610160.88 52.584710171.8453.86602 10191.948.1454410252.0652.41896
10292.17 51.481210322.2557.6672210402.4659.8812210442.5764.1631710565.3666.54054
#Mann= 3 , 0 , 0
 9518.88  0.0743       0 9518.88  0.0743       010565.36  0.0743       0
#XS Ineff= 2 , 0
       09902.226        10103.13       0
Bank Sta=9518.88,10565.36
Exp/Cntr=0.3,0.1

Type RM Length L Ch R = 3 ,7999.912,,,
BEGIN DESCRIPTION:
END DESCRIPTION:
Bridge Culvert--1,0,-1,-1, 0
Deck Dist Width WeirC Skew NumUp NumDn MinLoCord MaxHiCord MaxSubmerge Is_Ogee
35.962350,52.000000,2.6,0, 45, 45, , , 0.95, 0, 0,0,,
 9505.29 9533.28 9555.64 9566.82 9589.18 9600.36 9625.81 9648.17 9656.26 9678.62
 9689.80 9707.16 9735.64 9747.27 9758.91 9770.55 9782.18 9805.45 9831.59 9874.94
 9885.36 9916.29 9916.2910096.2910096.2910116.8610120.9010154.4410176.4610206.60
10236.7410276.9210286.9610317.1010329.6010387.4210434.6210447.6910457.7410477.83
10487.8810507.9710528.0610548.1510574.56
   61.74   58.71   56.52   55.58   53.92   53.20   51.83   50.37   49.77   48.50
   48.07   47.63   47.44   47.53   47.75   48.08   48.52   49.63   51.16   53.50
   53.30   53.37   53.37   53.78   53.78   53.83   54.33   52.78   52.17   51.57
   51.23   51.25   51.18   51.24   51.36   51.48   51.84   52.04   52.30   53.00
   53.50   54.60   55.82   57.33   59.05
 -938.26 -941.29 -943.48 -944.42 -946.08 -946.80 -948.17 -949.63 -950.23 -951.50
 -951.93 -952.37 -952.56 -952.47 -952.25 -951.92 -951.48 -950.37 -948.84 -946.50
 -946.70 -946.63   49.87   50.28 -946.22 -946.17 -945.67 -947.22 -947.83 -948.43
 -948.77 -948.75 -948.82 -948.76 -948.64 -948.52 -948.16 -947.96 -947.70 -947.00
 -946.50 -945.40 -944.18 -942.67 -940.95
 9505.29 9533.28 9555.64 9566.82 9589.18 9600.36 9625.81 9648.17 9656.26 9678.62
 9689.80 9707.16 9735.64 9747.27 9758.91 9770.55 9782.18 9805.45 9831.59 9874.94
 9885.36 9909.21 9909.2110089.2110089.2110116.8610120.9010154.4410176.4610206.60
10236.7410276.9210286.9610317.1010329.6010387.4210434.6210447.6910457.7410477.83
10487.8810507.9710528.0610548.1510574.56
   61.74   58.71   56.52   55.58   53.92   53.20   51.83   50.37   49.77   48.50
   48.07   47.63   47.44   47.53   47.75   48.08   48.52   49.63   51.16   53.50
   53.30   53.35   53.35   53.77   53.77   53.83   54.33   52.78   52.17   51.57
   51.23   51.25   51.18   51.24   51.36   51.48   51.84   52.04   52.30   53.00
   53.50   54.60   55.82   57.33   59.05
 -938.26 -941.29 -943.48 -944.42 -946.08 -946.80 -948.17 -949.63 -950.23 -951.50
 -951.93 -952.37 -952.56 -952.47 -952.25 -951.92 -951.48 -950.37 -948.84 -946.50
 -946.70 -946.65   49.85   50.27 -946.23 -946.17 -945.67 -947.22 -947.83 -948.43
 -948.77 -948.75 -948.82 -948.76 -948.64 -948.52 -948.16 -947.96 -947.70 -947.00
 -946.50 -945.40 -944.18 -942.67 -940.95
Pier Skew, UpSta & Num, DnSta & Num=  ,9975.63, 2 ,9968.55, 2 , 0 , 0 , 0 ,,
    4.00    4.00
 -946.49   53.51
    4.00    4.00
 -946.51   53.49
Pier Skew, UpSta & Num, DnSta & Num=  ,10036.96, 2 ,10029.88, 2 , 0 , 0 , 0 ,,
    4.00    4.00
 -946.35   53.65
    4.00    4.00
 -946.37   53.63
BR Coef=-1 , 0 , 0 ,, 0 ,,,0.8,0,1,0,
WSPro=,,,, 1 ,,,, 0 ,,,, 0 ,,,,-1 ,-1 ,-1 , 0 , 0 , 0 , 0 , 0
BC Design=,, 0 ,, 0 ,,,,,,

Type RM Length L Ch R = 1 ,7945.807,343.475200,343.475200,343.475200
XS GIS Cut Line= 6
822228.284007937 847064.50999555822102.415952384847306.480481684
821962.441994041 847630.91624555821927.719771862847675.404092804
821914.698938489847750.273884445821886.213034242 848091.29455851
#Sta/Elev= 30
9474.92262.517659599.46754.329239720.40351.211429756.93547.034049868.45744.79938
9876.53645.566289887.40944.066129909.15535.448629963.51934.363149996.13728.30657
10039.6532.6084610050.6235.9512110072.5838.6316310106.2146.44127 10167.246.90805
10177.3548.39103 10207.847.45414 10228.148.91325 10238.248.1036810258.2849.17058
 10368.749.4405510398.8151.9799310408.8451.05557   10459 52.426110469.0351.67313
10479.0653.84553 10489.152.9960810509.1654.2894710529.2252.3901810575.6756.31917
#Mann= 3 , 0 , 0
9474.922  0.0671       09474.922  0.0671       010575.67  0.0671       0
#XS Ineff= 2 , 0
       09873.535        10122.97       0
Bank Sta=9474.922,10575.67
Exp/Cntr=0.3,0.1

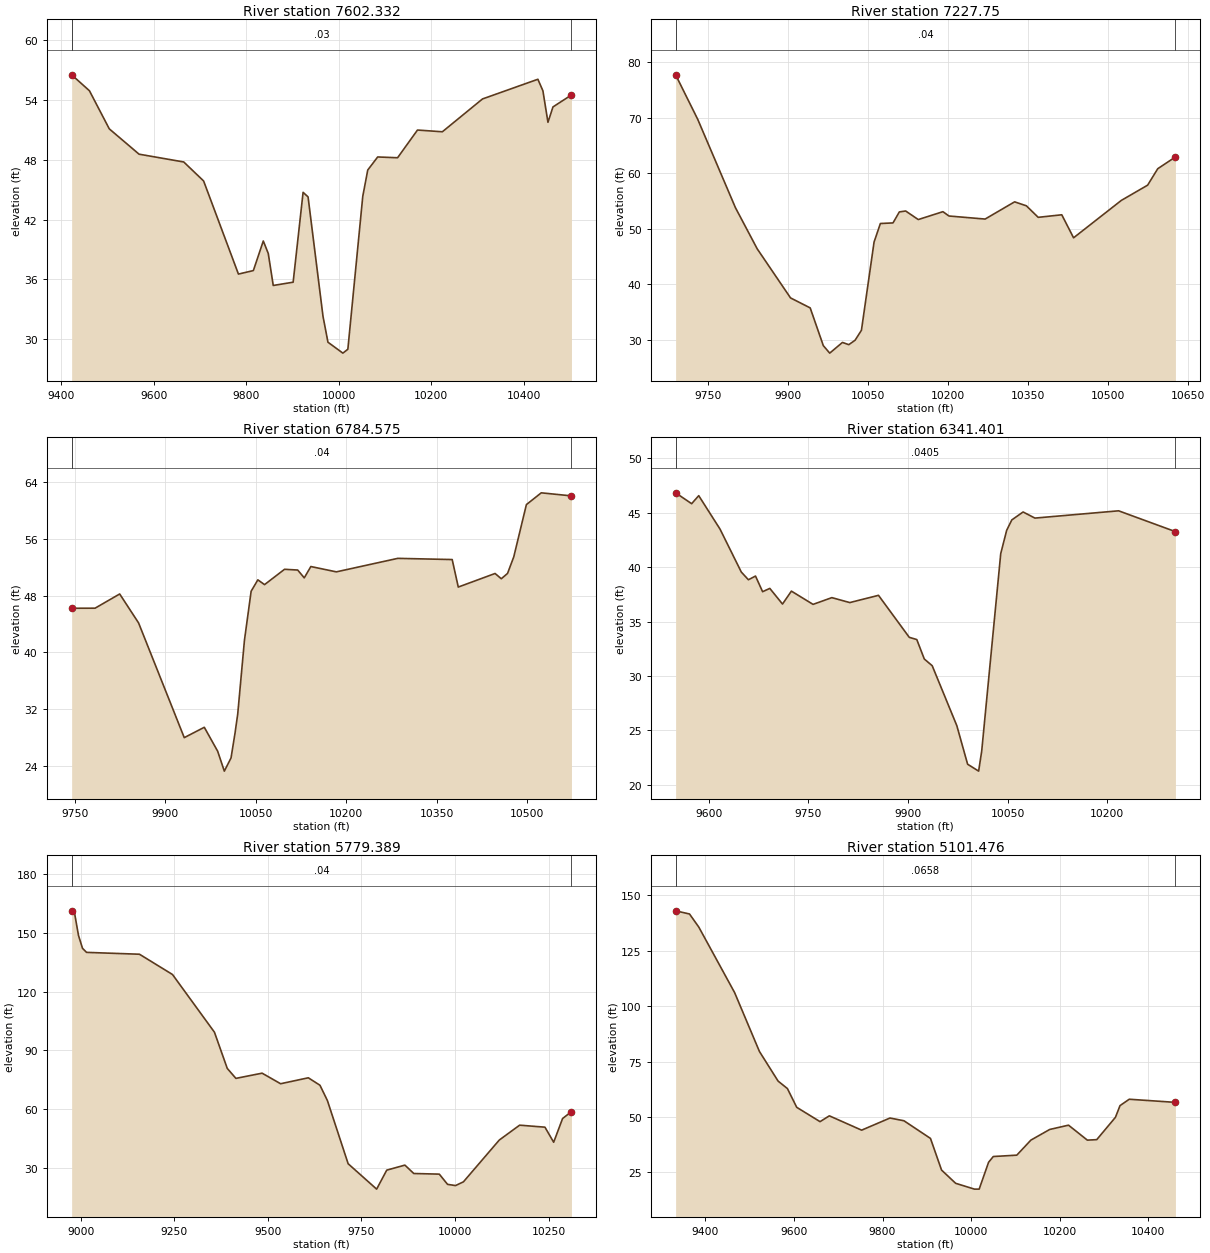
Type RM Length L Ch R = 1 ,7602.332,374.581900,374.581900,374.581900
XS GIS Cut Line= 4
821662.323330313847089.215050653821562.280188352847346.131452113
821764.392994016847858.382873282821864.639985114848091.684961647
#Sta/Elev= 30
9422.87256.510429461.27554.91662  9504.251.094019568.58948.555439665.17147.77364
9708.11445.868739783.36536.535669815.61636.886869837.11739.853779847.867 38.5985
9858.61735.394349901.61835.721429923.11844.729789933.86944.274099966.11932.30919
 9976.8729.7035310009.1228.6110710019.8728.9990810052.1244.3327310062.8746.96461
10084.3748.2763910127.3748.1963210170.3750.9755610224.1350.8009610310.88 54.0915
10430.6156.0651610441.4954.9094810452.3851.7533110463.2653.2932610503.19 54.4924
#Mann= 3 , 0 , 0
9422.872    0.03       09422.872    0.03       010503.19    0.03       0
#XS Ineff= 2 , 0
       09926.635                       0
Bank Sta=9422.872,10503.19
Exp/Cntr=0.3,0.1

Type RM Length L Ch R = 1 , 7227.75,443.174500,443.174500,443.174500
XS GIS Cut Line= 6
821205.495742053847627.732973218 821283.65339148847786.519320652
821366.412419558847845.613410622821531.520756543847951.098508701
821787.217041731848077.158248588821943.958083481 848160.37469995
#Sta/Elev= 30
9688.793  77.721 9730.3369.68882 9800.8953.799019841.78746.37034 9904.2937.52814
9941.15335.726919965.72828.93782 9977.7327.5797810001.6429.5060810013.5429.10385
10025.3829.9080710037.2331.6956410060.92 47.586510072.7650.9312610096.4551.03929
10108.2953.0194910120.1453.1883410143.8351.6443210190.0553.06462 10201.452.28361
10269.1951.7349410324.4854.8361810346.5954.1189610368.7152.0464910412.9452.50493
10435.0548.3560510524.5755.09304 10573.957.8403610592.9160.8051110626.0662.92057
#Mann= 3 , 0 , 0
9688.793    0.04       09688.793    0.04       010626.06    0.04       0
#XS Ineff= 2 , 0
       0                               0
Bank Sta=9688.793,10626.06
Exp/Cntr=0.3,0.1

Type RM Length L Ch R = 1 ,6784.575,443.174500,443.174500,443.174500
XS GIS Cut Line= 6
821156.417167455 848311.16206646821280.535407096848284.954989332
821524.773087459848172.201124437821628.616947049848143.499800002
821779.348405832848144.128685028821945.153358251 848193.00389859
#Sta/Elev= 30
9744.46446.222249783.30846.233219824.11548.235459855.48644.152759931.20127.99129
 9964.4429.450919986.59926.079929997.67923.2734710008.7825.13019 10015.428.62492
 10019.931.3360310031.02 41.704110042.1348.6210910053.25 50.225510064.3749.55304
10097.5351.7131610119.3451.6083310130.2450.5049510141.1452.1022810183.4551.35112
10285.3653.2547310375.57 53.085410385.6449.2099810446.6651.12264   1045750.38124
10467.3351.1289710477.6653.4566110498.6160.8274410523.2862.4880810573.3662.05774
#Mann= 3 , 0 , 0
9744.464    0.04       09744.464    0.04       010573.36    0.04       0
#XS Ineff= 2 , 0
       0                               0
Bank Sta=9744.464,10573.36
Exp/Cntr=0.3,0.1

Type RM Length L Ch R = 1 ,6341.401,562.012000,562.012000,562.012000
XS GIS Cut Line= 6
821132.424659275848437.438425232821320.140676045848510.630188743
821417.130884807 848556.45431496821477.240494321848588.453322962
821655.330453919848716.174501493821787.819029851848798.908439945
#Sta/Elev= 30
9550.34446.838929574.45945.840819585.14146.577799617.18743.505489649.23239.55672
9659.91438.850629670.59639.18991 9681.2837.753389692.11438.056519711.23436.61828
9724.61637.806039757.228  36.5879785.493 37.20799812.528 36.7534 9855.7237.41942
9902.02533.560639913.354 33.35619924.68331.567259936.56630.951239973.63425.44032
9989.85521.9005510006.4621.2647510011.0823.1102110039.7341.2561310048.6343.38641
10056.3644.3475610073.3945.0790810091.2144.5174310217.1545.1858910302.6843.27253
#Mann= 3 , 0 , 0
9550.344  0.0405       09550.344  0.0405       010302.68  0.0405       0
#XS Ineff= 2 , 0
       0                               0
Bank Sta=9550.344,10302.68
Exp/Cntr=0.3,0.1

Type RM Length L Ch R = 1 ,5779.389,677.913400,677.913400,677.913400
XS GIS Cut Line= 6
820248.144896215 848252.69338415820613.736391672848420.286877058
820847.627366051848579.945428257820995.130193839  848761.0710948
821103.001490279 849021.57510153821169.673633762849134.435578743
#Sta/Elev= 30
8976.198161.23068983.598 160.4598994.393148.69349005.188142.08939015.983140.0121
9157.257139.06159245.456128.70669357.47999.224459391.61380.758739414.69475.66122
9484.66978.314589534.13472.923819608.03175.962199639.14772.15198 9658.9764.35188
9714.38632.066599790.46819.100259817.35528.789799865.91431.368269889.64227.07736
9957.74126.757339979.77821.5416810000.9820.9110810022.1922.8273410117.8744.16638
10172.1951.7622110239.83 50.742310263.0943.0386110286.9255.1711310310.59  58.661
#Mann= 3 , 0 , 0
8976.198    0.04       08976.198    0.04       010310.59    0.04       0
#XS Ineff= 2 , 0
       0                               0
Bank Sta=8976.198,10310.59
Exp/Cntr=0.3,0.1

Type RM Length L Ch R = 1 ,5101.476,302.480600,302.480600,302.480600
XS GIS Cut Line= 4
820165.228211313849486.795617521 820663.25718832849322.280781254
821094.695923239849167.614064962821235.533317347849128.327844497
#Sta/Elev= 30
9332.592143.07729363.946141.65419385.009135.72019465.843106.18419521.91979.60796
9564.04466.246739585.10762.86771 9606.1754.400689658.828 47.93769679.89150.56003
9752.77644.09575  9816.849.573689848.39448.332759908.29840.371549933.30426.09062
9965.173 20.111710007.67 17.485210018.2917.4907310039.5429.5886410050.1632.19612
10103.2732.8122410135.1439.6098910177.64 44.407110220.1346.3510610262.6239.59729
10283.8739.8112510326.1149.8896910336.49 55.178210357.2658.0487810461.6356.63756
#Mann= 3 , 0 , 0
9332.592  0.0658       09332.592  0.0658       010461.63  0.0658       0
#XS Ineff= 2 , 0
       09815.893        10129.97       0
Bank Sta=9332.592,10461.63
Exp/Cntr=0.3,0.1

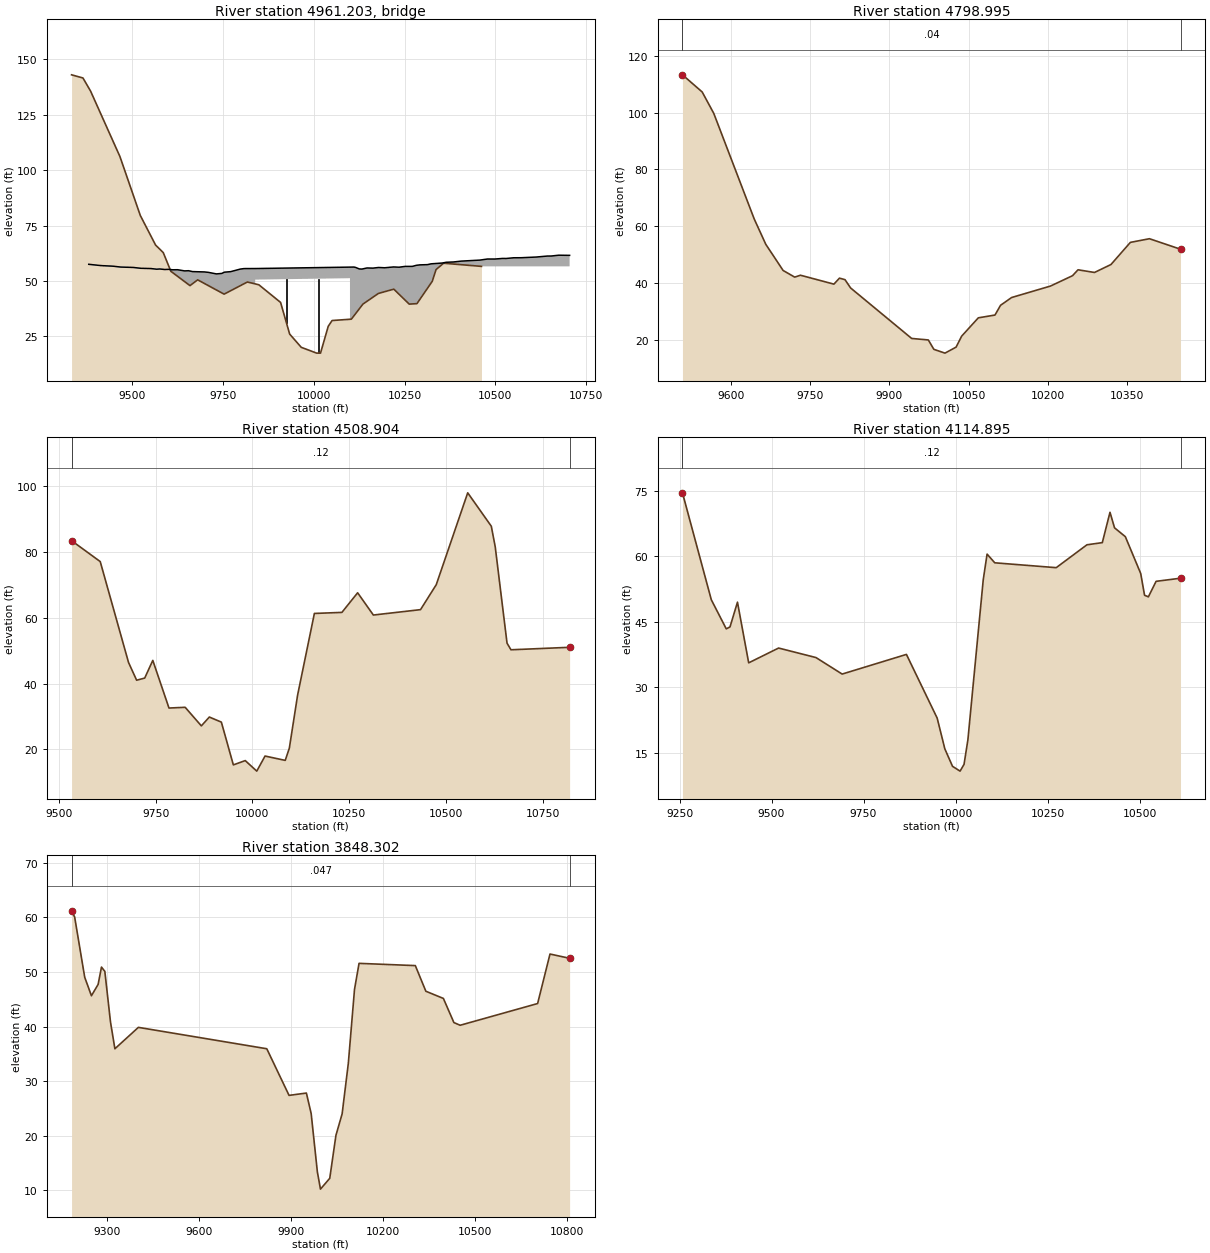
Type RM Length L Ch R = 3 ,4961.203,,,
BEGIN DESCRIPTION:
END DESCRIPTION:
Bridge Culvert--1,0,-1,-1, 0
Deck Dist Width WeirC Skew NumUp NumDn MinLoCord MaxHiCord MaxSubmerge Is_Ogee
85.740300,131.000000,2.6,0, 60, 60, , , 0.95, 0, 0,0,,
 9379.92 9413.60 9446.49 9468.42 9502.47 9523.23 9551.26 9567.09 9575.66 9589.01
 9600.05 9610.94 9624.45 9643.83 9654.79 9665.76 9698.65 9709.61 9731.54 9746.43
 9753.46 9770.82 9797.07 9807.65 9838.42 9838.4210099.4210099.4210110.2010114.60
10125.1810132.2410146.3510162.7610178.1010194.9210219.6710234.5810250.6710271.34
10281.6710292.0010312.6710323.0110353.5410364.3410385.0110405.6810457.3510478.02
10498.6810519.3510529.6910550.3510571.0210612.3610643.3610653.6910674.3610704.39
   57.57   56.99   56.72   56.32   56.15   55.77   55.65   55.36   55.46   55.22
   55.29   55.10   55.13   54.60   54.68   54.28   54.13   53.93   53.24   53.46
   54.02   54.26   55.41   55.64   55.66   55.66   56.30   56.30   56.33   56.18
   55.48   55.42   55.92   55.85   56.14   56.01   56.38   56.26   56.62   56.63
   57.10   57.32   57.42   57.79   58.14   58.48   58.63   59.01   59.47   59.96
   59.95   60.22   60.20   60.52   60.54   60.85   61.30   61.31   61.68   61.61
 -942.43 -943.01 -943.28 -943.68 -943.85 -944.23 -944.35 -944.64 -944.54 -944.78
 -944.71 -944.90 -944.87 -945.40 -945.32 -945.72 -945.87 -946.07 -946.76 -946.54
 -945.98 -945.74 -944.59 -944.36 -944.34   50.66   51.30 -943.70 -943.67 -943.82
 -944.52 -944.58 -944.08 -944.15 -943.86 -943.99 -943.62 -943.74 -943.38 -943.37
 -942.90 -942.68 -942.58 -942.21 -941.86 -941.52 -941.37 -940.99 -940.53 -940.04
 -940.05 -939.78 -939.80 -939.48 -939.46 -939.15 -938.70 -938.69 -938.32 -938.39
 9379.92 9413.60 9446.49 9468.42 9502.47 9523.23 9551.26 9567.09 9575.66 9589.01
 9600.05 9610.94 9624.45 9643.83 9654.79 9665.76 9698.65 9709.61 9720.57 9731.54
 9746.43 9753.46 9770.82 9796.50 9807.65 9854.19 9854.1910110.2010115.1910115.19
10125.1810132.2410146.3510162.7610178.1010194.9210219.6710234.5810250.6710271.34
10281.6710292.0010312.6710323.0110353.5410364.3410385.0110405.6810457.3510478.02
10498.6810519.3510529.6910550.3510571.0210612.3610643.3610653.6910674.3610704.39
   57.57   56.99   56.72   56.32   56.15   55.77   55.65   55.36   55.46   55.22
   55.29   55.10   55.13   54.60   54.68   54.28   54.13   53.93   53.50   53.24
   53.46   54.02   54.26   55.39   55.64   55.70   55.70   56.33   56.14   56.14
   55.48   55.42   55.92   55.85   56.14   56.01   56.38   56.26   56.62   56.63
   57.10   57.32   57.42   57.79   58.14   58.48   58.63   59.01   59.47   59.96
   59.95   60.22   60.20   60.52   60.54   60.85   61.30   61.31   61.68   61.61
 -942.43 -943.01 -943.28 -943.68 -943.85 -944.23 -944.35 -944.64 -944.54 -944.78
 -944.71 -944.90 -944.87 -945.40 -945.32 -945.72 -945.87 -946.07 -946.50 -946.76
 -946.54 -945.98 -945.74 -944.61 -944.36 -944.30   50.70   51.33   51.14 -943.86
 -944.52 -944.58 -944.08 -944.15 -943.86 -943.99 -943.62 -943.74 -943.38 -943.37
 -942.90 -942.68 -942.58 -942.21 -941.86 -941.52 -941.37 -940.99 -940.53 -940.04
 -940.05 -939.78 -939.80 -939.48 -939.46 -939.15 -938.70 -938.69 -938.32 -938.39
Pier Skew, UpSta & Num, DnSta & Num=  ,9924.76, 2 ,9940.53, 2 , 0 , 0 , 0 ,,
    4.00    4.00
 -944.13   55.87
    4.00    4.00
 -944.09   55.91
Pier Skew, UpSta & Num, DnSta & Num=  ,10013.09, 2 ,10028.86, 2 , 0 , 0 , 0 ,,
    4.00    4.00
 -943.91   56.09
    4.00    4.00
 -943.87   56.13
BR Coef=-1 , 0 , 0 ,, 0 ,,,0.8,0,1,0,
WSPro=,,,, 1 ,,,, 0 ,,,, 0 ,,,,-1 ,-1 ,-1 , 0 , 0 , 0 , 0 , 0
BC Design=,, 0 ,, 0 ,,,,,,

Type RM Length L Ch R = 1 ,4798.995,290.090600,290.090600,290.090600
XS GIS Cut Line= 5
820400.852545679849741.420435101820609.788285255849649.163095579
821058.584866554          849505821290.443910629   849439.553737
821291.558190475849439.374865761
#Sta/Elev= 30
 9509.03113.30849546.358107.25839568.22199.729279644.74162.492029666.60453.57736
9699.39944.344499721.26242.010339732.19342.675019795.41839.534349805.921  41.645
9816.42441.107819826.92838.198629942.463   20.399973.97319.860359984.47616.54751
10005.4815.2177910026.4917.3398510036.9921.19765 10068.527.6558410100.0128.63884
10110.5232.0720810131.5234.8209510205.0438.8604810246.6542.5077510257.0444.58959
10288.2143.6492510319.3846.4515810356.0654.2511510392.1255.5421510450.8651.84272
#Mann= 3 , 0 , 0
 9509.03    0.04       0 9509.03    0.04       010450.86    0.04       0
#XS Ineff= 2 , 0
       09842.954        10132.59       0
Bank Sta=9509.03,10450.86
Exp/Cntr=0.3,0.1

Type RM Length L Ch R = 1 ,4508.904,394.009100,394.009100,394.009100
XS GIS Cut Line= 6
820464.169500287849982.448341602820784.947309555849884.200476051
820978.405968326849836.379398838821017.616637387849822.464847167
821058.071716795849804.315007591821714.162908614849684.437960669
#Sta/Elev= 30
9532.36783.505859606.44577.155959679.65546.454459700.57241.051799721.489 41.7065
9742.40647.08575 9784.2432.587399826.07432.810989867.90827.160049888.61629.84825
9919.678 28.30399950.64915.289679981.39416.5954810011.2513.3921710032.6117.98218
10084.7916.65991 10095.420.3641710116.8836.5775710160.1761.3672810231.3361.68965
10271.9967.6572410312.6660.8842810434.6462.52637 10475.370.1263910556.6398.06895
10617.6287.9066810627.7981.6092410658.2852.3308910668.4550.3116310820.0851.06715
#Mann= 3 , 0 , 0
9532.367    0.12       09532.367    0.12       010820.08    0.12       0
#XS Ineff= 2 , 0
       09869.647        10226.68       0
Bank Sta=9532.367,10820.08
Exp/Cntr=0.3,0.1

Type RM Length L Ch R = 1 ,4114.895,266.593300,266.593300,266.593300
XS GIS Cut Line= 3
 820447.83772397 850044.82231985820973.011335075850138.138292044
821758.601612866849903.763292044
#Sta/Elev= 30
9258.04474.504079336.41550.009399377.04143.336989387.19843.780879407.51149.45004
9437.98135.551969519.23438.94291  9620.836.763269691.89732.981169866.56837.48513
9950.05222.901519970.92315.845269991.79411.8491410012.2910.74503 10023.112.29416
10033.5417.9039710075.2854.5979810085.7160.4637310106.59 58.471310273.55 57.3582
10357.0462.5999210398.7863.0931810419.6570.0460810432.0366.4825410461.3964.45821
10503.1456.0160310513.5751.0369110524.0150.6772610544.8854.2257410611.2554.94388
#Mann= 3 , 0 , 0
9258.044    0.12       09258.044    0.12       010611.25    0.12       0
#XS Ineff= 2 , 0
       09840.741        10116.95       0
Bank Sta=9258.044,10611.25
Exp/Cntr=0.3,0.1

Type RM Length L Ch R = 1 ,3848.302,0.000000,0.000000,0.000000
XS GIS Cut Line= 6
820425.776530325850103.549206257820695.788312882850223.245151117
821149.519452572 850348.50834918821361.075076044850319.280269653
821596.291525751850450.110720977821968.322684199850440.316161528
#Sta/Elev= 30
9183.51761.173859193.60660.038379226.422 49.01459248.29945.634639270.17647.71076
9281.11450.876429292.05350.095729310.47340.847179324.86835.930489401.43839.84727
9820.39735.934069893.01627.399879949.57527.828449965.20224.060499985.39213.40169
9995.48710.2465310025.7712.2250310045.9620.0876810066.1524.0212710086.3433.26171
10106.5346.7874510121.3551.5605510304.9451.1499610339.2746.4606310396.4945.13922
10430.8140.7210610451.2140.2330610703.8944.20811 10744.353.2670910808.2752.48729
#Mann= 3 , 0 , 0
9183.517   0.047       09183.517   0.047       010808.27   0.047       0
#XS Ineff= 2 , 0
       09947.876        10127.27       0
Bank Sta=9183.517,10808.27
Exp/Cntr=0.3,0.1